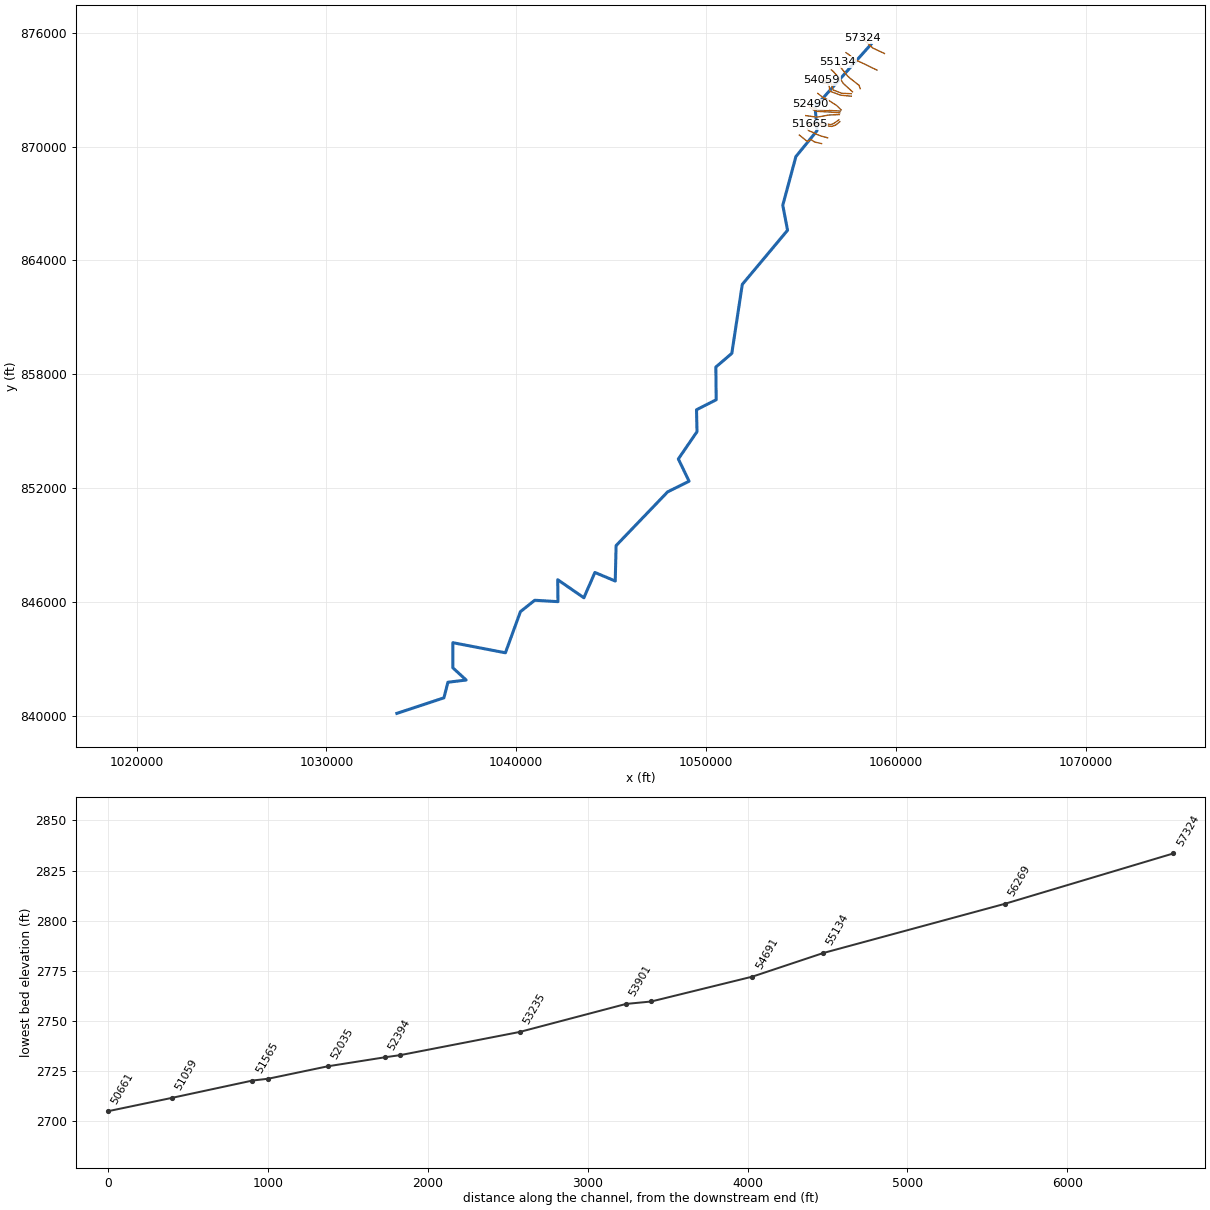
--- lds_big_rock_crk.prj (project) ---

Proj Title=Big Rock Creek Limited Detail Study
Current Plan=p02
Default Exp/Contr=0.3,0.1
English Units
Geom File=g01
Flow File=f02
Plan File=p02
Y Axis Title=Elevation
X Axis Title(PF)=Main Channel Distance
X Axis Title(XS)=Station
BEGIN DESCRIPTION:
Big Rock Creek
END DESCRIPTION:
DSS Export Rating Curves= 0
DSS Export Rating Curve Sorted= 0
DSS Export Volume Flow Curves= 0
DXF OffsetX= 0
DXF OffsetY= 0
DXF ScaleX= 1
DXF ScaleY= 10

--- lds_big_rock_crk.p02 (plan) ---

Plan Title=Floodway Run
Program Version=3.13
Short Identifier=Multiple
Geom File=g01
Flow File=f02
Subcritical Flow
K Sum by GR= 0
Std Step Tol= 0.01
Critical Tol= 0.01
Num of Std Step Trials= 20
Max Error Tol= 0.3
Flow Tol Ratio= 0.001
Split Flow NTrial= 30
Split Flow Tol= 0.02
Split Flow Ratio= 0.02
Log Output Level= 0
Friction Slope Method= 1
Unsteady Friction Slope Method= 2
Unsteady Bridges Friction Slope Method= 1
Parabolic Critical Depth
Global Vel Dist= 0 , 0 , 0
Global Log Level= 0
CheckData=True
Encroach Param=-1 ,10,10, 2
Encroach River=Big Rock Creek
Encroach Reach=Reach-1
Encroach Node=57324
       1    4945    5083
Encroach Node=56269
       4      .7
Encroach Node=55134
       1  4974.5    5100
Encroach Node=54691
       1  4976.5  5108.8
Encroach Node=54059
       1    4911    5100
Encroach Node=53901
       1    4903    5097
Encroach Node=53235
       4      .7
Encroach Node=52490
       1    4850    5029
Encroach Node=52394
       1    4850  5027.5
Encroach Node=52035
       1    4840 5022.45
Encroach Node=51665
       1    4850  5067.7
Encroach Node=51565
       1  4889.9  5114.1
Encroach Node=51059
       1  4962.9  5136.9
Encroach Node=50661
       1    4969    5210
Encroach Node=50549
       1  4971.5    5210
Encroach Node=49961
       1  4914.9    5100
Encroach Node=49398
       1    4900    5057
Encroach Node=48826
       4      .7
Encroach Node=48204
       1 4963.75  5038.8
Encroach Node=47470
       1    4950    5039
Encroach Node=46802
       1    4930 5048.07
Encroach Node=46203
       1    4960    5071
Encroach Node=45770
       1 4954.06 5032.74
Encroach Node=45315
       4      .7
Encroach Node=44929
       1    4960  5034.7
Encroach Node=44436
       1    4947    5029
Encroach Node=43962
       1  4966.5 5030.39
Encroach Node=43510
       1 4961.15  5038.8
Encroach Node=43027
       1 4965.51 5042.21
Encroach Node=42510
       1 4964.83 5032.42
Encroach Node=42103
       1    4950    5060
Encroach Node=42018
       1  4913.9  5056.6
Encroach Node=41486
       1  4973.5    5083
Encroach Node=40879
       1    4958    5044
Encroach Node=40269
       1  4967.5    5100
Encroach Node=39712
       1    4931    5120
Encroach Node=39161
       1    4925  5035.8
Encroach Node=38628
       1    4845    5031
Encroach Node=38025
       1    4900    5100
Encroach Node=37926
       1    4925    5125
Encroach Node=37463
       1    4946    5125
Encroach Node=36979
       1    4875  5029.9
Encroach Node=36489
       4      .7
Encroach Node=36296
       1    4952    5050
Encroach Node=36228
       1  4954.5    5085
Encroach Node=36040
       4      .7
Encroach Node=35940
       1    4919    5060
Encroach Node=35861
       1    4934    5066
Encroach Node=35389
       1    4940    5043
Encroach Node=34682
       1    4974    5075
Encroach Node=34221
       1    4960    5125
Encroach Node=34146
       1  4965.4    5082
Encroach Node=33753
       1    4971    5066
Encroach Node=33295
       1    4891    5035
Encroach Node=32839
       1    4881  5041.5
Encroach Node=32426
       1    4875    5060
Encroach Node=31876
       1    4960    5100
Encroach Node=31275
       1    4946    5100
Encroach Node=30676
       1  4897.5  5066.8
Encroach Node=30583
       1 4937.15    5030
Encroach Node=30186
       4      .1
Encroach Node=29918
       4      .9
Encroach Node=29536
       4      .1
Encroach Node=29010
       4      .1
Encroach Node=28484
       1 4958.52  5075.7
Encroach Node=27747
       1  4886.8  5105.2
Encroach Node=27424
       4      .7
Encroach Node=26947
       1    4900    5041
Encroach Node=26541
       1  4934.5    5175
Encroach Node=26475
       1    4950    5075
Encroach Node=26148
       1    4926    5080
Encroach Node=25862
       1    4930    5057
Encroach Node=25505
       1    4930    5075
Encroach Node=25072
       1    4937    5071
Encroach Node=25001
       1    4940    5050
Encroach Node=24615
       1    4944    5048
Encroach Node=24186
       1    4935    5055
Encroach Node=23813
       1    4887  5037.3
Encroach Node=23433
       1 3483.67    3621
Encroach Node=23311
       1 3478.33 3592.53
Encroach Node=22859
       1 4945.03  5038.8
Encroach Node=22286
       4      .7
Encroach Node=21812
       4      .7
Encroach Node=21418
       4      .7
Encroach Node=20868
       4      .7
Encroach Node=20523
       1 4976.71  5102.1
Encroach Node=20157
       1    4928    5084
Encroach Node=19697
       1 4899.37    5060
Encroach Node=19347
       1  4948.7 5072.27
Encroach Node=18868
       4      .1
Encroach Node=18491
       4      .7
Encroach Node=18146
       4      .4
Encroach Node=17661
       4      .7
Encroach Node=17245
       1    4922    5060
Encroach Node=16922
       1    4920    5045
Encroach Node=16430
       1    4800    5050
Encroach Node=16043
       1    4958    5059
Encroach Node=15612
       1    4944    5069
Encroach Node=15149
       1    4971    5092
Encroach Node=14797
       1    4937    5059
Encroach Node=14388
       1    4930    5070
Encroach Node=14018
       1    4850    5037
Encroach Node=13572
       1    4925    5054
Encroach Node=13234
       4      .7
Encroach Node=12718
       1    4955    5047
Encroach Node=12357
       1    4931  5068.5
Encroach Node=12272
       1    4946  5059.5
Encroach Node=11835
       4      .7
Encroach Node=11490
       4      .7
Encroach Node=11113
       1    4942    5100
Encroach Node=10742
       1    4942    5100
Encroach Node=10337
       1  4961.2    5100
Encroach Node=10026
       4      .7
Encroach Node=9704
       4      .7
Encroach Node=9325
       1    4934    5044
Encroach Node=9257
       4      .7
Encroach Node=8835
       4      .7
Encroach Node=8351
       4      .7
Encroach Node=7980
       4      .7
Encroach Node=7666
       1    4941    5075
Encroach Node=7408
       1 4900.93  5052.5
Encroach Node=7356
       1    4880    5059
Encroach Node=6806
       1 4881.45  5014.1
Encroach Node=6520
       1    4971  5113.4
Encroach Node=6250
       1    4910    5055
Encroach Node=5969
       1    4875    5042
Encroach Node=5787
       1    4890    5042
Encroach Node=5523
       1    4920    5037
Encroach Node=5198
       4      .7
Encroach Node=4895
       4      .7
Encroach Node=4559
       1    4971    5127
Encroach Node=4320
       4      .7
Encroach Node=3977
       4      .7
Encroach Node=3775
       4      .7
Encroach Node=3363
       4      .7
Encroach Node=3127
       1    4961    5055
Encroach Node=2714
       4      .7
Encroach Node=2273
       1  4960.6  5150.3
Encroach Node=1872
       1  4889.5    5054
Encroach Node=1575
       1  4878.9 5050.78
Encroach Node=1197
       1  4939.3 5114.34
Encroach Node=874
       1    4954  5097.1
Encroach Node=556
       1    4946    5100
Encroach Node=279
       1 4961.54 5061.87
Encroach Node=214
       1  4956.5  5117.9
Encroach Node=132
       1    4908    5200
BEGIN DESCRIPTION:
Multiple Run
END DESCRIPTION:
Computation Interval=1HOUR
Output Interval=1HOUR
Run HTab= 0
Run UNet= 0
Run PostProcess= 0
UNET Theta= 1
UNET Theta Warmup= 1
UNET ZTol= 0.02
UNET ZSATol= 0.05
UNET MxIter= 20
UNET MaxInSteps= 0
UNET DtIC= 0
UNET DtMin= 0
UNET MaxCRTS= 20
UNET WFStab= 2
UNET SFStab= 1
UNET WFX= 1
UNET SFX= 1
UNET DSS MLevel= 4
UNET DZMax Abort= 100
UNET Convert EG Bridges=-1
UNET Use Existing IB Tables=-1
UNET Froude Reduction=False
UNET Froude Limit= 1
UNET Froude Power= 10
Instantaneous Interval=1HOUR
Write IC File= 0
Echo Input=False
Echo Output=False
Write Detailed= 0
Detailed Automatic Start=False, 10

--- lds_big_rock_crk.f02 (steady flow) ---

Flow Title=Floodway
Program Version=3.13
Number of Profiles= 2
Profile Names=100-year,100-FW
River Rch & RM=Big Rock Creek,Reach-1         ,57324
    4330    4330
River Rch & RM=Big Rock Creek,Reach-1         ,54059
    4540    4540
River Rch & RM=Big Rock Creek,Reach-1         ,53235
    6070    6070
River Rch & RM=Big Rock Creek,Reach-1         ,52490
    6280    6280
River Rch & RM=Big Rock Creek,Reach-1         ,48826
    6490    6490
River Rch & RM=Big Rock Creek,Reach-1         ,46203
    6720    6720
River Rch & RM=Big Rock Creek,Reach-1         ,45315
    7040    7040
River Rch & RM=Big Rock Creek,Reach-1         ,40879
    7590    7590
River Rch & RM=Big Rock Creek,Reach-1         ,38628
    7770    7770
River Rch & RM=Big Rock Creek,Reach-1         ,36040
    9180    9180
River Rch & RM=Big Rock Creek,Reach-1         ,34682
    9340    9340
River Rch & RM=Big Rock Creek,Reach-1         ,27747
   13050   13050
River Rch & RM=Big Rock Creek,Reach-1         ,25505
   13320   13320
River Rch & RM=Big Rock Creek,Reach-1         ,24615
   13320   13320
River Rch & RM=Big Rock Creek,Reach-1         ,24186
   13390   13390
River Rch & RM=Big Rock Creek,Reach-1         ,21418
   13510   13510
River Rch & RM=Big Rock Creek,Reach-1         ,19347
   13590   13590
River Rch & RM=Big Rock Creek,Reach-1         ,12357
   13850   13850
River Rch & RM=Big Rock Creek,Reach-1         ,8835
   14000   14000
Boundary for River Rch & Prof#=Big Rock Creek,Reach-1         , 1
Up Type= 0
Dn Type= 3
Dn Slope=0.001
Boundary for River Rch & Prof#=Big Rock Creek,Reach-1         , 2
Up Type= 0
Dn Type= 3
Dn Slope=0.001
DSS Import GetInterval= 0
DSS Import GetPeak= 0
DSS Import FillOption= 0

--- lds_big_rock_crk.g01 (geometry) ---

Geom Title=Existing Conditions
Program Version=3.13

River Reach=Big Rock Creek  ,Reach-1
Reach XY= 30
      1058689.05       875395.35      1055742.72        872091.8
      1055843.98       870838.13      1054732.51       869478.77
      1054040.09       866910.26      1054292.28       865592.47
      1051907.44       862737.52      1051356.18       859103.41
      1050515.47       858383.72      1050532.76       856659.07
      1049496.57       856130.77      1049522.47       854975.11
      1048539.52       853537.38      1049105.11       852364.45
      1047975.36       851803.17      1045260.91       848971.88
      1045215.77       847102.96      1044144.59       847556.08
      1043563.86       846221.01      1042185.39       847173.27
      1042198.41       846016.15      1040976.18        846090.8
      1040220.98       845488.37      1039430.77       843320.39
      1036662.89       843854.41      1036660.38       842530.64
      1037362.38       841886.31      1036402.15       841768.48
      1036191.55       840946.13      1033713.26       840127.82

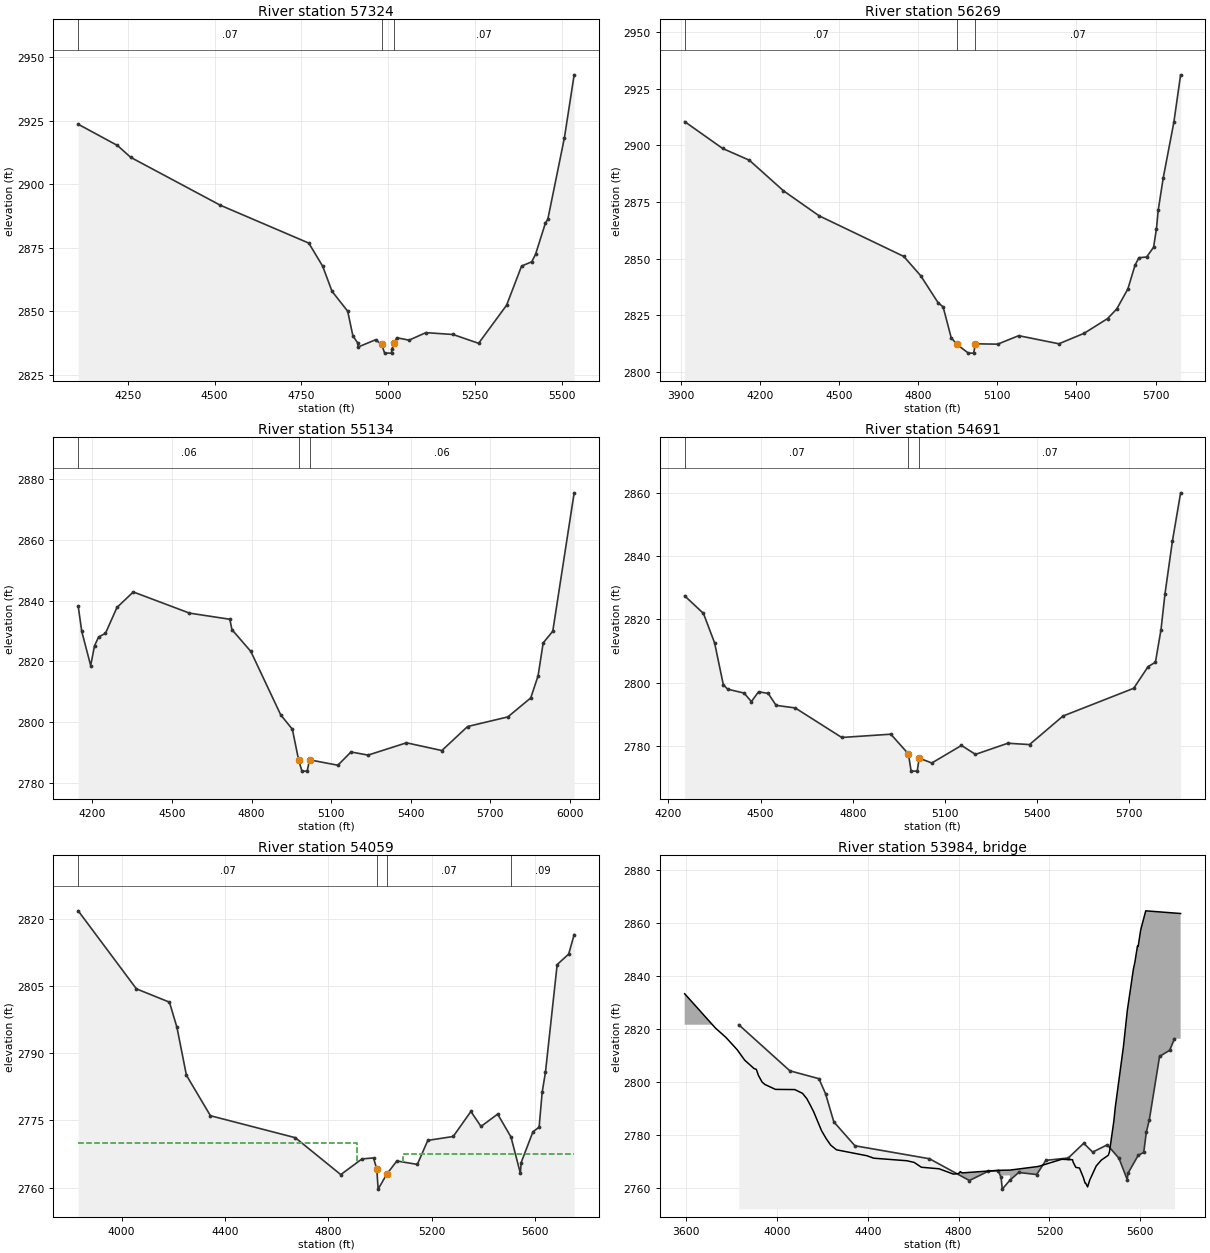
Type RM Length L Ch R = 1 ,57324   ,1055,1055,1055
BEGIN DESCRIPTION:
XS 164
END DESCRIPTION:
XS GIS Cut Line= 4
      1059396.77       874909.06      1058779.42       875197.75
      1058539.58       875428.71      1058233.13       875708.51
#Sta/Elev= 30
  4106.9 2923.71    4220 2915.34  4258.3 2910.66  4516.3 2891.82  4771.5 2876.89
  4811.6 2867.76  4838.4 2857.91  4883.6 2850.06  4898.6 2840.35  4912.5 2837.55
  4913.6 2835.96  4963.9 2838.81 4981.32 2836.98  4990.1 2833.55  5009.9 2833.55
  5010.5 2835.06 5017.51 2837.39    5025 2839.61  5060.5 2838.66    5109 2841.62
  5187.3 2840.89  5260.9 2837.42  5341.5 2852.41  5384.8 2867.84  5413.9 2869.53
  5424.9 2872.42  5453.5 2884.79  5460.3 2886.22  5508.2 2918.36  5536.3 2943.17
#Mann= 3 , 0 , 0
  4106.9     .07       0 4981.32     .05       0 5017.51     .07       0
Bank Sta=4981.32,5017.51
Exp/Cntr=0.3,0.1

Type RM Length L Ch R = 1 ,56269   ,1135,1135,1135
BEGIN DESCRIPTION:
XS 163
END DESCRIPTION:
XS GIS Cut Line= 5
      1059001.49       874034.11      1058148.74       874447.16
       1057886.7       874562.64       1057522.5       874846.88
       1057371.5       874953.48
#Sta/Elev= 30
  3914.2 2910.53  4058.2 2898.69  4159.3 2893.51  4288.9    2880  4424.2 2868.96
    4745 2851.06  4809.2 2842.54  4875.7 2830.53  4894.3 2828.78  4924.8 2815.21
  4946.1 2812.27  4990.1 2808.38  5009.9 2808.38    5017 2812.49  5101.3 2812.34
  5180.9 2816.08  5333.3  2812.5  5429.2 2817.14  5517.9 2823.63  5552.6 2827.86
  5594.8 2836.68  5622.2 2847.24  5636.9 2850.48    5666 2850.79  5692.5 2855.13
  5703.3 2863.32  5710.1 2871.53  5728.9 2885.67  5769.2 2910.22  5794.9 2931.18
#Mann= 3 ,-1 , 0
  3914.2     .07       0  4946.1     .05       0    5017     .07       0
Bank Sta=4946.1,5017
Exp/Cntr=0.3,0.1

Type RM Length L Ch R = 1 ,55134   ,443,443,443
BEGIN DESCRIPTION:
XS 162
END DESCRIPTION:
XS GIS Cut Line= 6
      1058117.65         873057.      1058059.91       873230.22
      1057602.45       873589.97      1057455.88       873723.21
      1057087.25       874180.68      1056940.68       874464.92
#Sta/Elev= 30
  4146.5 2838.16  4159.8  2829.9  4193.5  2818.6    4208 2825.12  4223.4 2828.03
  4249.2 2829.22  4292.6 2837.75  4354.2 2842.86    4566 2835.89  4718.3 2833.86
  4726.1 2830.46  4797.5 2823.25  4910.1 2802.37    4954 2797.64  4977.5 2787.55
  4990.1 2783.84  5009.9 2783.84  5018.7 2787.57  5125.5 2785.78  5175.1 2790.15
  5239.4 2789.12  5384.2 2793.17  5517.7 2790.62  5614.6 2798.53  5766.5  2801.7
  5852.8 2807.95  5880.4  2815.2  5899.7 2826.07  5935.9 2829.93  6016.5 2875.51
#Mann= 3 ,-1 , 0
  4146.5     .06       0  4977.5     .05       0  5018.7     .06       0
Bank Sta=4977.5,5018.7
Exp/Cntr=0.3,0.1

Type RM Length L Ch R = 1 ,54691   ,632,632,632
BEGIN DESCRIPTION:
XS 161
END DESCRIPTION:
XS GIS Cut Line= 6
      1057713.48       872888.23      1057558.04       873030.35
      1057224.93       873332.37      1057131.66       873483.38
      1056709.73       873949.72      1056598.69       874047.43
#Sta/Elev= 30
  4252.9 2827.43    4314 2821.89  4350.3 2812.58  4378.7 2799.37  4392.8 2797.95
  4446.1 2796.73  4470.1 2794.03  4493.4 2797.13  4524.8 2796.62  4550.5 2792.84
  4612.6 2792.03  4764.3 2782.69    4924 2783.73  4981.2  2777.5  4990.1 2772.06
  5009.9 2772.06  5016.4 2776.16  5057.4 2774.63    5154 2780.18  5199.5 2777.35
  5304.9 2780.87  5375.5 2780.45  5484.6 2789.47  5714.8 2798.24  5761.5 2805.08
  5785.4 2806.46  5803.6 2816.79  5816.5 2828.08  5840.8  2844.8  5867.4 2859.99
#Mann= 3 ,-1 , 0
  4252.9     .07       0  4981.2     .05       0  5016.4     .07       0
Bank Sta=4981.2,5016.4
Exp/Cntr=0.5,0.3

Type RM Length L Ch R = 1 ,54059   ,158,158,158
BEGIN DESCRIPTION:
XS 160
END DESCRIPTION:
XS GIS Cut Line= 6
      1057650.97       872789.52      1057144.98       872813.61
      1056688.65       872988.98      1056600.98       873307.17
      1056490.59       873466.26      1056091.69       873488.27
#Sta/Elev= 30
  3832.2 2821.73  4057.3 2804.33  4185.1 2801.36  4214.2 2795.73  4250.8 2785.06
  4343.8 2776.03    4672 2771.13  4847.9  2762.9  4930.1  2766.4  4974.7 2766.62
  4987.3 2764.09  4992.5 2759.66    5026 2763.01  5064.9 2765.94  5144.1 2765.17
  5184.6 2770.53  5282.9  2771.4  5351.3 2776.98  5390.4 2773.64  5454.9 2776.39
  5506.4 2771.29  5542.8 2763.19  5545.8 2765.59  5591.3 2772.44  5615.3 2773.49
  5627.1 2781.28  5639.8 2785.73  5685.1 2809.75  5729.6 2812.08  5750.8 2816.43
#Mann= 4 ,-1 , 0
  3832.2     .07       0  4987.3     .05       0    5026     .07       0
  5506.4     .09       0
#XS Ineff= 2 , 0
       0    4911    2770 5089.08       0  2767.5
Permanent Ineff=
       T       F
Bank Sta=4987.3,5026
Exp/Cntr=0.5,0.3

Type RM Length L Ch R = 3 ,53984   ,,,
BEGIN DESCRIPTION:
XS 159 TOR
Structure ID: XS 159
Approximate Survey Structure
END DESCRIPTION:
Bridge Culvert--1,0,-1,-1, 0
Deck Dist Width WeirC Skew NumUp NumDn MinLoCord MaxHiCord MaxSubmerge Is_Ogee
63,24,3,0, 60, 60, , , , 0, 1,1,,
  3594.1  3729.3  3775.7    3825  3858.3  3900.1  3909.4  3918.8  3934.9  3947.4
  3993.8  4078.9    4113  4132.3  4146.8  4161.8  4196.7  4217.4  4237.1  4262.4
  4396.8  4426.4  4572.1  4604.6  4636.3  4714.3  4777.1  4800.2  4807.7    4816
    4974    4974    5026    5026  5151.2  5254.5    5302  5304.2  5316.4  5332.4
  5349.7  5357.2  5360.4  5368.2  5377.8  5406.2  5428.9  5459.2  5464.4  5483.8
    5490    5526  5543.1  5569.9  5576.5  5587.8  5590.8    5602  5624.2  5777.8
 2833.43  2820.5 2816.94 2812.32 2808.35 2805.14 2804.91  2802.6 2800.09 2799.17
 2797.32 2797.25 2795.82 2793.76 2791.44 2788.91 2781.73  2778.7 2776.27 2774.51
 2772.26 2771.34 2770.38 2769.75 2767.92 2767.34 2765.34 2765.54 2766.27 2765.79
 2766.76 2766.76 2766.84 2766.84 2768.22 2770.93 2770.75 2769.91 2767.87 2767.64
 2764.01 2761.91 2761.85  2760.5 2763.11 2768.41 2770.64 2772.43 2773.67 2785.36
 2790.52 2813.48 2827.12 2842.74 2845.37 2851.48  2851.3 2857.54 2864.74 2863.73
    2737    2737    2737    2737    2737    2737    2737    2737    2737    2737
    2737    2737    2737    2737    2737    2737    2737    2737    2737    2737
    2737    2737    2737    2737    2737    2737    2737    2737    2737    2737
    2737 2764.76 2764.84    2737    2737    2737    2737    2737    2737    2737
    2737    2737    2737    2737    2737    2737    2737    2737    2737    2737
    2737    2737    2737    2737    2737    2737    2737    2737    2737    2737
  3594.1  3729.3  3775.7    3825  3858.3  3900.1  3909.4  3918.8  3934.9  3947.4
  3993.8  4078.9    4113  4132.3  4146.8  4161.8  4196.7  4217.4  4237.1  4262.4
  4396.8  4426.4  4572.1  4604.6  4636.3  4714.3  4777.1  4800.2  4807.7    4816
    4974    4974    5026    5026  5151.2  5254.5    5302  5304.2  5316.4  5332.4
  5349.7  5357.2  5360.4  5368.2  5377.8  5406.2  5428.9  5459.2  5464.4  5483.8
    5490    5526  5543.1  5569.9  5576.5  5587.8  5590.8    5602  5624.2  5777.8
 2833.43  2820.5 2816.94 2812.32 2808.35 2805.14 2804.91  2802.6 2800.09 2799.17
 2797.32 2797.25 2795.82 2793.76 2791.44 2788.91 2781.73  2778.7 2776.27 2774.51
 2772.26 2771.34 2770.38 2769.75 2767.92 2767.34 2765.34 2765.54 2766.27 2765.79
 2766.76 2766.76 2766.84 2766.84 2768.22 2770.93 2770.75 2769.91 2767.87 2767.64
 2764.01 2761.91 2761.85  2760.5 2763.11 2768.41 2770.64 2772.43 2773.67 2785.36
 2790.52 2813.48 2827.12 2842.74 2845.37 2851.48  2851.3 2857.54 2864.74 2863.73
    2737    2737    2737    2737    2737    2737    2737    2737    2737    2737
    2737    2737    2737    2737    2737    2737    2737    2737    2737    2737
    2737    2737    2737    2737    2737    2737    2737    2737    2737    2737
    2737 2764.76 2764.84    2737    2737    2737    2737    2737    2737    2737
    2737    2737    2737    2737    2737    2737    2737    2737    2737    2737
    2737    2737    2737    2737    2737    2737    2737    2737    2737    2737
BR Coef= 1 , 1 , 0 ,1.25, 0 ,,,0.8,0,2,0,
WSPro=,,,, 1 ,,,, 0 ,,,, 0 ,,,,-1 ,-1 ,-1 , 0 , 0 , 0 , 0 , 0
BC Design=,, 0 ,, 0 ,,,,,,
BC HTab HWMax=2821.73

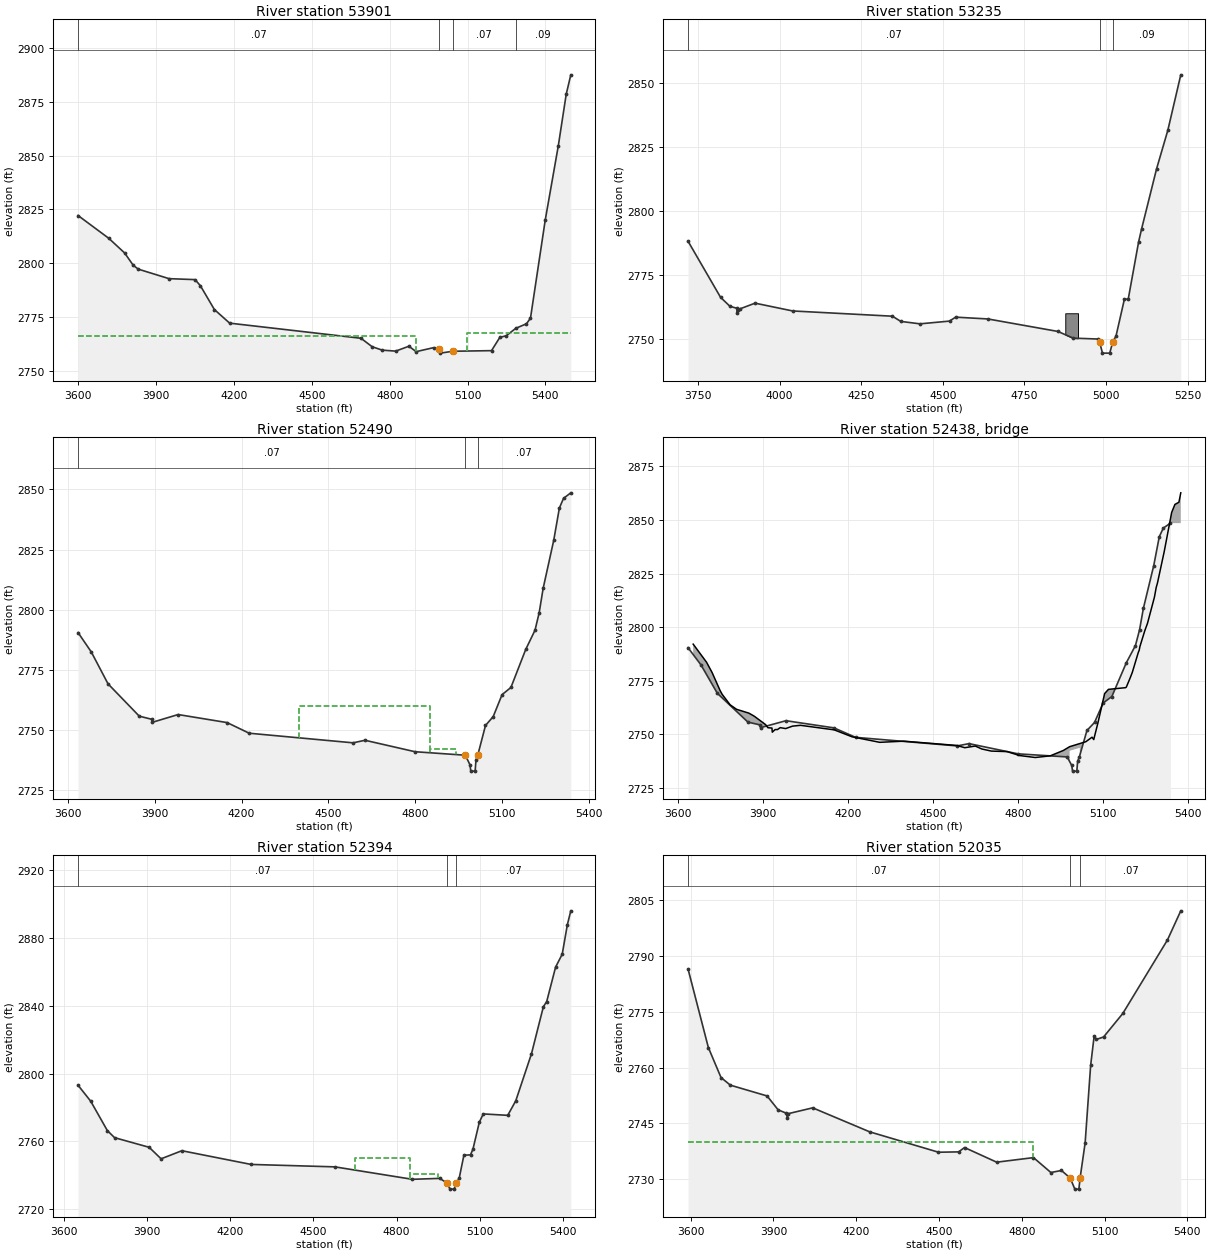
Type RM Length L Ch R = 1 ,53901   ,666,666,666
BEGIN DESCRIPTION:
XS 158
END DESCRIPTION:
XS GIS Cut Line= 6
      1057650.97       872658.72      1057096.79       872710.35
      1056536.05       872914.31      1056471.11       873229.24
      1056404.55       873331.52      1056104.23       873365.61
#Sta/Elev= 30
  3598.8 2822.21  3717.2 2811.65  3778.3 2804.85  3811.5 2799.14  3830.8 2797.36
  3949.4 2792.95  4049.9  2792.5  4070.5 2789.63  4124.2 2778.64  4183.1 2772.33
  4689.3 2765.32  4732.2 2761.41  4771.2 2759.82  4822.9 2759.37    4874 2761.64
  4901.6 2759.12  4968.7 2760.97  4988.8 2760.31  4995.3 2758.44  5043.2 2759.31
  5192.3 2759.59  5224.5 2765.77  5248.7 2766.46  5285.6 2769.92    5327 2772.05
  5342.5 2774.66  5399.5 2820.21  5449.8 2854.57  5480.2 2878.41  5497.9  2887.4
#Mann= 4 ,-1 , 0
  3598.8     .07       0  4988.8     .05       0  5043.2     .07       0
  5285.6     .09       0
#XS Ineff= 2 , 0
       0    4903 2766.44    5097       0 2767.62
Permanent Ineff=
       F       F
Bank Sta=4988.8,5043.2
Exp/Cntr=0.5,0.3

Type RM Length L Ch R = 1 ,53235   ,745,745,745
BEGIN DESCRIPTION:
XS 157
END DESCRIPTION:
XS GIS Cut Line= 5
        1057114.       871935.87      1056883.38       872163.05
      1056429.01       872459.07      1056115.78       872624.29
       1055888.6       872803.28
#Sta/Elev= 30
  3719.4 2788.12  3819.1 2766.22  3847.7 2762.73  3869.2 2761.93  3870.6 2759.97
  3871.4 2761.08  3878.3 2761.71  3924.8 2763.94  4039.8  2760.9  4345.5 2758.85
  4371.2 2756.82  4429.9 2755.87  4520.4 2756.94  4539.1 2758.48  4637.7 2757.78
  4852.5  2752.9  4899.2 2750.29  4974.1 2749.95  4980.4 2748.59    4989 2744.44
  5011.2 2744.44  5020.3 2748.75  5030.4  2751.1  5056.4 2765.64  5067.7 2765.39
  5099.7 2787.89  5108.9 2792.98  5154.6 2816.33  5189.1 2831.39  5228.8 2853.05
#Mann= 3 ,-1 , 0
  3719.4     .07       0  4980.4     .05       0  5020.3     .09       0
#Block Obstruct= 1 ,-1
    4875    4914    2760
Bank Sta=4980.4,5020.3
Exp/Cntr=0.5,0.3

Type RM Length L Ch R = 1 ,52490   ,96,96,96
BEGIN DESCRIPTION:
XS 156
END DESCRIPTION:
XS GIS Cut Line= 6
      1057076.13       871873.91      1056742.25       871894.56
      1055867.95       871942.75      1055682.07       872028.81
      1055565.04       872104.53      1055482.43       872228.45
#Sta/Elev= 30
  3634.9 2790.48  3680.5 2782.46  3738.5 2769.18  3846.4 2755.76  3889.8 2754.44
  3890.9 2753.17  3980.8 2756.42  4150.1 2753.08  4226.5 2748.66  4585.5 2744.67
  4626.8 2745.73  4799.9 2740.97  4973.5 2739.52  4989.5 2735.58  4992.5 2732.91
  5007.5 2732.91  5010.4 2737.54  5016.4 2739.48  5043.3 2751.88    5070 2755.59
  5100.6 2764.69  5131.2 2767.68  5182.3 2783.46  5214.5 2791.47  5228.9 2798.75
  5242.6 2808.87  5279.1 2828.78  5298.7 2842.24    5313 2846.25  5338.2 2848.55
#Mann= 3 ,-1 , 0
  3634.9     .07       0  4973.5     .05       0  5016.4     .07       0
#XS Ineff= 3 ,-1
    4400    4850    2760    4850    4940    2742    5060    5100    2749
Permanent Ineff=
       F       F       F
Bank Sta=4973.5,5016.4
Exp/Cntr=0.5,0.3

Type RM Length L Ch R = 3 ,52438   ,,,
BEGIN DESCRIPTION:
XS 155
Structure ID: XS 155
Approximate Survey Structure
END DESCRIPTION:
Bridge Culvert--1,0,-1,-1, 0
Deck Dist Width WeirC Skew NumUp NumDn MinLoCord MaxHiCord MaxSubmerge Is_Ogee
42,20,3,0, 60, 60, , , , 0, 1,1,,
  3653.1  3700.4  3719.8  3748.3  3755.8  3783.6  3806.4  3849.8  3868.6    3909
  3916.9  3931.2  3932.4  3942.4  3950.6  3960.5  3979.6    4004    4032  4151.2
  4214.3  4311.8  4396.6  4584.4  4611.8    4649  4672.2  4705.9  4761.3  4805.2
  4860.6  4913.8    4960    4982    4982    5018    5018  5039.3  5061.3  5067.2
  5081.8  5105.7  5119.1  5179.9  5182.3  5194.4  5203.5  5224.6  5227.7  5230.2
  5247.5  5257.1  5281.5  5287.8  5292.1  5316.2  5342.3  5353.8  5367.9  5374.5
 2792.12 2783.66 2778.91 2770.44 2768.65 2763.83 2761.72 2759.95 2758.53 2754.57
 2753.15    2753 2751.08 2752.29 2752.29 2753.18 2752.75 2753.89 2754.27 2752.15
  2748.9 2746.34 2746.88 2744.87 2743.83  2744.6 2743.23 2742.25 2742.02 2740.19
 2739.26 2740.04 2742.55  2744.3  2744.3 2745.76 2745.76 2746.63 2748.72 2747.62
  2755.3 2769.07 2771.03 2771.83 2772.11 2775.91    2779 2788.29 2789.27 2790.99
 2798.39 2801.88 2814.03 2818.59 2820.56 2835.38 2853.52 2857.26 2858.28 2862.67
    2708    2708    2708    2708    2708    2708    2708    2708    2708    2708
    2708    2708    2708    2708    2708    2708    2708    2708    2708    2708
    2708    2708    2708    2708    2708    2708    2708    2708    2708    2708
    2708    2708    2708    2708  2742.4 2743.77    2708    2708    2708    2708
    2708    2708    2708    2708    2708    2708    2708    2708    2708    2708
    2708    2708    2708    2708    2708    2708    2708    2708    2708    2708
  3653.1  3700.4  3719.8  3748.3  3755.8  3783.6  3806.4  3849.8  3868.6    3909
  3916.9  3931.2  3932.4  3942.4  3950.6  3960.5  3979.6    4004    4032  4151.2
  4214.3  4311.8  4396.6  4584.4  4611.8    4649  4672.2  4705.9  4761.3  4805.2
  4860.6  4913.8    4960    4982    4982    5018    5018  5039.3  5061.3  5067.2
  5081.8  5105.7  5119.1  5179.9  5182.3  5194.4  5203.5  5224.6  5227.7  5230.2
  5247.5  5257.1  5281.5  5287.8  5292.1  5316.2  5342.3  5353.8  5367.9  5374.5
 2792.12 2783.66 2778.91 2770.44 2768.65 2763.83 2761.72 2759.95 2758.53 2754.57
 2753.15    2753 2751.08 2752.29 2752.29 2753.18 2752.75 2753.89 2754.27 2752.15
  2748.9 2746.34 2746.88 2744.87 2743.83  2744.6 2743.23 2742.25 2742.02 2740.19
 2739.26 2740.04 2742.55  2744.3  2744.3 2745.76 2745.76 2746.63 2748.72 2747.62
  2755.3 2769.07 2771.03 2771.83 2772.11 2775.91    2779 2788.29 2789.27 2790.99
 2798.39 2801.88 2814.03 2818.59 2820.56 2835.38 2853.52 2857.26 2858.28 2862.67
    2708    2708    2708    2708    2708    2708    2708    2708    2708    2708
    2708    2708    2708    2708    2708    2708    2708    2708    2708    2708
    2708    2708    2708    2708    2708    2708    2708    2708    2708    2708
    2708    2708    2708    2708  2742.4 2743.77    2708    2708    2708    2708
    2708    2708    2708    2708    2708    2708    2708    2708    2708    2708
    2708    2708    2708    2708    2708    2708    2708    2708    2708    2708
Abutment Skew #Up #Dn= , 2 , 2
    4982    4985
  2737.5 2732.88
    4982    4985
  2742.4 2735.18
Abutment Skew #Up #Dn= , 2 , 2
    5015    5018
 2736.08  2737.5
    5015    5018
 2735.63 2743.77
BR Coef= 1 , 1 , 0 ,1.25, 0 ,,,0.8,0,2,0,
WSPro=,,,, 1 ,,,, 0 ,,,, 0 ,,,,-1 ,-1 ,-1 , 0 , 0 , 0 , 0 , 0
BC Design=,, 0 ,, 0 ,,,,,,
BC HTab HWMax=2848.55

Type RM Length L Ch R = 1 ,52394   ,359,359,359
BEGIN DESCRIPTION:
XS 154
END DESCRIPTION:
XS GIS Cut Line= 6
      1057041.71       871780.97      1056539.16       871822.28
      1055829.36       871859.94      1055640.55       871945.36
      1055485.87        872052.9      1055392.93       872190.59
#Sta/Elev= 30
  3651.4 2793.17  3697.1 2783.73  3757.1 2766.38  3783.1 2762.22  3907.8 2756.53
  3950.8 2749.73  4025.7 2754.51  4275.4 2746.41  4577.4 2744.98  4856.8 2737.63
  4955.9 2738.17  4982.1 2735.38  4992.5 2731.83  5007.5 2731.83 5013.87 2735.21
  5025.8 2738.31  5042.7 2751.87  5066.5 2752.06  5075.5 2755.52  5098.3 2771.35
  5112.6 2776.24  5200.8  2775.4  5229.8 2784.01  5286.2 2811.66  5329.3 2839.55
  5341.3 2842.61  5373.4 2862.96  5397.2 2870.55  5415.9 2888.08  5428.2 2896.16
#Mann= 3 , 0 , 0
  3651.4     .07       0  4982.1     .05       0 5013.87     .07       0
#XS Ineff= 3 ,-1
    4650    4850    2750    4850    4949    2741    5052    5100    2748
Permanent Ineff=
       F       F       F
Bank Sta=4982.1,5013.87
Exp/Cntr=0.5,0.3

Type RM Length L Ch R = 1 ,52035   ,370,370,370
BEGIN DESCRIPTION:
XS 153
END DESCRIPTION:
XS GIS Cut Line= 5
      1057021.06       871688.04      1056473.76       871667.38
      1055843.85       871553.79      1055565.04       871591.66
      1055251.81        871636.4
#Sta/Elev= 30
  3590.5 2786.57  3664.2  2765.4  3710.1 2757.33    3744 2755.28    3877 2752.38
  3917.2 2748.63  3945.7 2747.77  3950.7 2746.52  3953.9 2747.62  4042.3 2749.18
  4248.9 2742.72  4498.1 2737.24  4570.9 2737.33  4592.5  2738.5  4708.9 2734.56
  4842.3 2735.79  4905.4 2731.78  4943.6 2732.33  4975.5 2730.28  4992.1 2727.31
  5006.8 2727.31  5011.1 2730.25  5029.5 2739.78  5049.4 2760.59    5062 2768.44
  5069.7 2767.57  5096.3 2768.25    5166 2774.58  5327.8 2794.36    5376 2802.19
#Mann= 3 ,-1 , 0
  3590.5     .07       0  4975.5     .05       0  5011.1     .07       0
#XS Ineff= 2 , 0
       0  4840.1    2740               0
Permanent Ineff=
       F       F
Bank Sta=4975.5,5011.1
Exp/Cntr=0.5,0.3

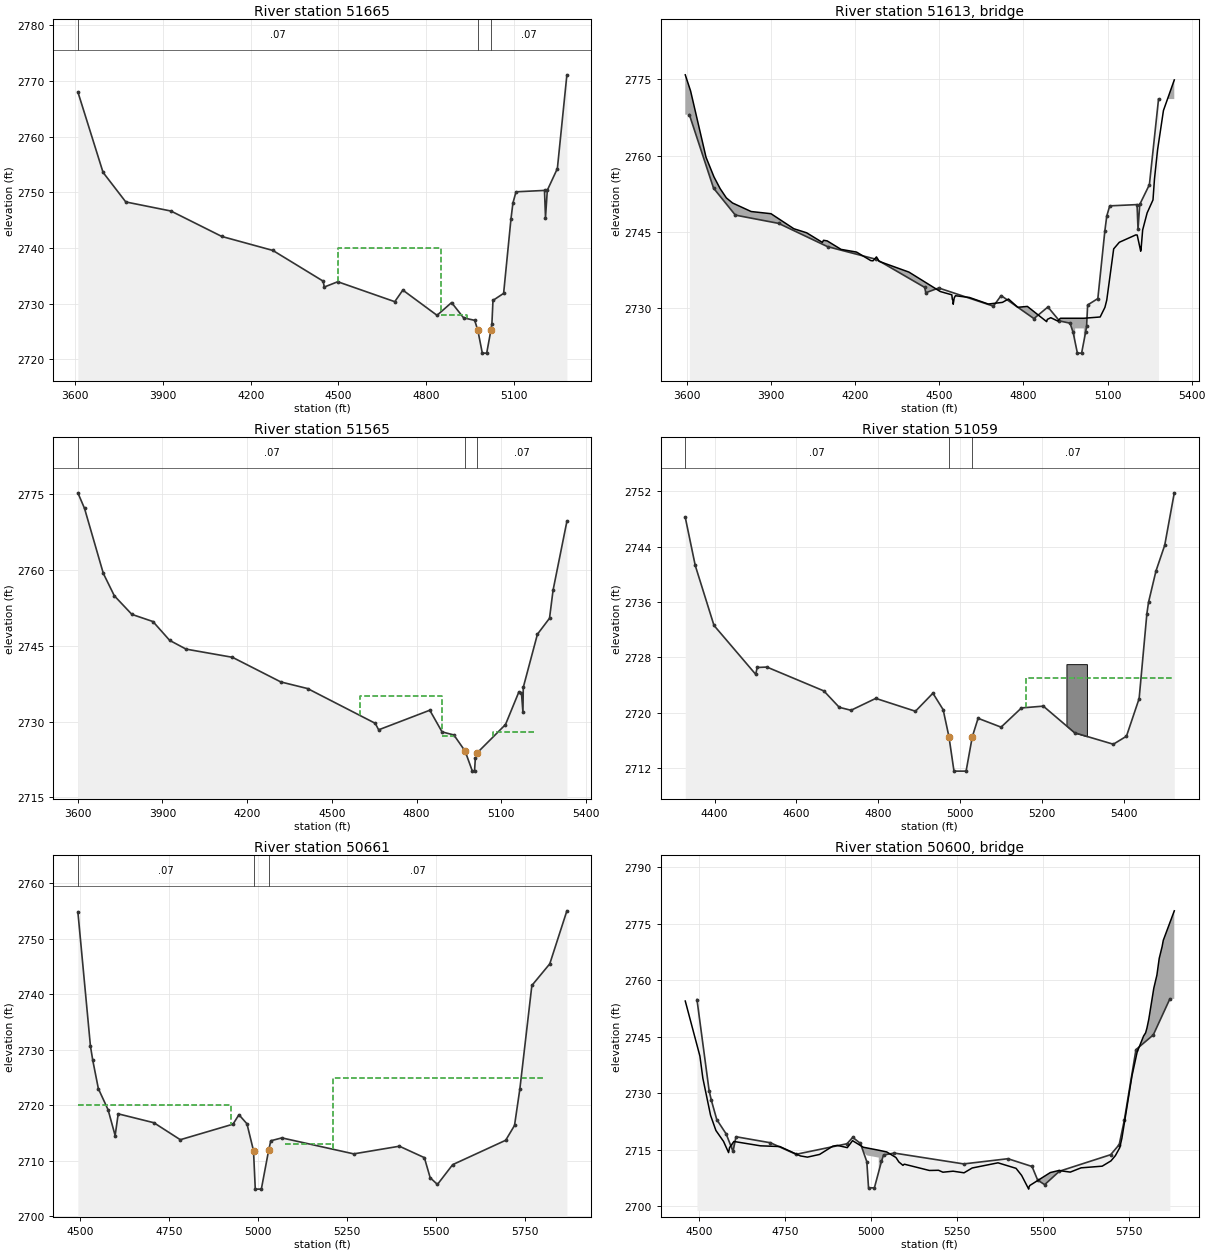
Type RM Length L Ch R = 1 ,51665   ,100,100,100
BEGIN DESCRIPTION:
XS 152
END DESCRIPTION:
XS GIS Cut Line= 6
      1056993.52       871412.67      1056738.81       871230.23
      1056577.03       871161.39      1055795.27       871271.27
      1055621.83       871188.45      1055420.47       871168.27
#Sta/Elev= 30
  3608.5 2768.05  3694.7  2753.6  3772.5 2748.29    3927 2746.66  4101.2 2742.09
  4275.8 2739.58  4447.8 2734.07  4451.7 2733.01  4497.8 2733.96  4692.9 2730.38
  4720.5 2732.46  4837.5 2727.93  4887.3 2730.22  4928.6 2727.47  4966.3 2727.03
  4977.2 2725.22  4992.5 2721.14  5007.5 2721.14 5021.74 2725.22  5025.3  2726.4
    5029 2730.61  5065.4 2731.87  5090.5 2745.21  5097.2 2748.09  5107.8 2750.11
  5205.3 2750.36  5208.7 2745.49  5214.9 2750.39  5249.3 2754.28  5281.9 2771.12
#Mann= 3 , 0 , 0
  3608.5     .07       0  4977.2     .05       0 5021.74     .07       0
#XS Ineff= 3 ,-1
    4500    4850    2740    4850  4938.5    2728  5061.5    5100 2728.25
Permanent Ineff=
       F       F       F
Bank Sta=4977.2,5021.74
Exp/Cntr=0.5,0.3

Type RM Length L Ch R = 3 ,51613   ,,,
BEGIN DESCRIPTION:
XS 151 TOR
Structure ID: XS 151
Approximate Survey Structure
END DESCRIPTION:
Bridge Culvert--1,0,-1,-1, 0
Deck Dist Width WeirC Skew NumUp NumDn MinLoCord MaxHiCord MaxSubmerge Is_Ogee
46,12,3,0, 60, 60, , , , 0, 1,1,,
  3593.9  3612.9  3667.9  3696.2  3718.2  3740.4  3762.4  3828.7  3899.6  3981.2
  4026.6  4082.7  4087.1  4100.1  4149.5  4204.8  4255.7  4263.5  4275.8  4285.1
  4391.7  4503.3  4544.6  4546.4  4548.8  4549.6  4553.1  4557.5  4607.4  4674.5
    4725  4746.8  4779.8  4814.1  4882.9  4885.1  4897.6  4922.5    4932  4984.5
  4984.5  5015.5  5015.5  5073.7  5090.7  5097.2  5121.9  5142.1  5200.8  5205.8
  5218.3    5219  5219.6  5225.3  5241.2  5262.1  5267.4  5278.3  5299.4  5338.1
 2775.89 2772.71 2759.68 2755.82 2753.51 2751.68 2750.68    2749 2748.57 2745.61
 2744.82 2742.93 2743.34 2743.22 2741.55 2741.02 2739.34  2739.3 2740.07  2739.2
 2737.08 2733.26 2732.61 2731.74 2731.43 2730.76    2732 2732.43 2732.09  2730.8
 2731.12 2731.79 2730.16 2730.33 2727.33 2727.77 2728.11 2727.45    2728    2728
    2728    2728    2728 2728.25 2730.15 2731.57 2741.65 2742.95  2744.4 2744.37
 2741.19    2742 2741.61 2745.38 2748.72 2751.28 2755.39 2761.07 2768.87 2774.89
    2700    2700    2700    2700    2700    2700    2700    2700    2700    2700
    2700    2700    2700    2700    2700    2700    2700    2700    2700    2700
    2700    2700    2700    2700    2700    2700    2700    2700    2700    2700
    2700    2700    2700    2700    2700    2700    2700    2700    2700    2700
    2726    2726    2700    2700    2700    2700    2700    2700    2700    2700
    2700    2700    2700    2700    2700    2700    2700    2700    2700    2700
  3593.9  3612.9  3667.9  3696.2  3718.2  3740.4  3762.4  3828.7  3899.6  3981.2
  4026.6  4082.7  4087.1  4100.1  4149.5  4204.8  4255.7  4263.5  4275.8  4285.1
  4391.7  4503.3  4544.6  4546.4  4548.8  4549.6  4553.1  4557.5  4607.4  4674.5
    4725  4746.8  4779.8  4814.1  4882.9  4885.1  4897.6  4922.5    4932  4984.5
  4984.5  5015.5  5015.5  5073.7  5090.7  5097.2  5121.9  5142.1  5200.8  5205.8
  5218.3    5219  5219.6  5225.3  5241.2  5262.1  5267.4  5278.3  5299.4  5338.1
 2775.89 2772.71 2759.68 2755.82 2753.51 2751.68 2750.68    2749 2748.57 2745.61
 2744.82 2742.93 2743.34 2743.22 2741.55 2741.02 2739.34  2739.3 2740.07  2739.2
 2737.08 2733.26 2732.61 2731.74 2731.43 2730.76    2732 2732.43 2732.09  2730.8
 2731.12 2731.79 2730.16 2730.33 2727.33 2727.77 2728.11 2727.45    2728    2728
    2728    2728    2728 2728.25 2730.15 2731.57 2741.65 2742.95  2744.4 2744.37
 2741.19    2742 2741.61 2745.38 2748.72 2751.28 2755.39 2761.07 2768.87 2774.89
    2700    2700    2700    2700    2700    2700    2700    2700    2700    2700
    2700    2700    2700    2700    2700    2700    2700    2700    2700    2700
    2700    2700    2700    2700    2700    2700    2700    2700    2700    2700
    2700    2700    2700    2700    2700    2700    2700    2700    2700    2700
    2726    2726    2700    2700    2700    2700    2700    2700    2700    2700
    2700    2700    2700    2700    2700    2700    2700    2700    2700    2700
BR Coef= 1 , 1 , 0 ,1.25, 0 ,,,0.8,0,2,0,
WSPro=,,,, 1 ,,,, 0 ,,,, 0 ,,,,-1 ,-1 ,-1 , 0 , 0 , 0 , 0 , 0
BC Design=,, 0 ,, 0 ,,,,,,
BC HTab HWMax=2771.12

Type RM Length L Ch R = 1 ,51565   ,506,506,506
BEGIN DESCRIPTION:
XS 150
END DESCRIPTION:
XS GIS Cut Line= 6
       1057048.6       871316.29      1056817.97       871130.41
        1056608.       871065.01      1055816.51        871171.9
      1055676.13       871102.32      1055417.03       871095.99
#Sta/Elev= 30
  3600.5 2775.32  3624.1 2772.23  3690.6 2759.37  3729.6 2754.93  3791.7 2751.25
  3866.4 2749.83  3925.6  2746.1  3983.6 2744.37  4147.8 2742.75  4319.1 2737.87
  4413.9 2736.56  4653.3 2729.68  4665.4 2728.39  4846.5 2732.27  4889.9 2727.98
  4931.8 2727.37  4971.6 2724.17  4997.2 2720.21  5004.9 2720.21  5007.7 2722.72
 5015.04 2723.87  5114.5 2729.43  5161.2  2735.8  5171.1 2735.65  5176.3 2731.85
  5177.5  2736.8  5227.6 2747.32  5270.4 2750.48    5283 2756.05  5331.9 2769.67
#Mann= 3 , 0 , 0
  3600.5     .07       0  4971.6     .05       0 5015.04     .07       0
#XS Ineff= 3 ,-1
    4600    4890    2735    4890  4938.5 2727.15 5071.22 5213.71    2728
Permanent Ineff=
       F       F       F
Bank Sta=4971.6,5015.04
Exp/Cntr=0.5,0.3

Type RM Length L Ch R = 1 ,51059   ,398,398,398
BEGIN DESCRIPTION:
XS 149
END DESCRIPTION:
XS GIS Cut Line= 6
      1056401.48       870466.08      1056057.26       870559.02
       1055823.2       870648.51      1055671.75       870731.12
      1055417.03       870837.83      1055327.53       870944.54
#Sta/Elev= 30
  4328.5 2748.23  4352.9 2741.27  4398.7  2732.6  4500.6 2725.53  4504.3 2726.52
    4528 2726.58  4667.2 2723.13  4704.8 2720.76  4733.5 2720.33  4794.1 2722.05
    4891 2720.19  4933.7  2722.8  4958.7 2720.42  4972.9 2716.51  4985.2 2711.53
  5014.8 2711.53  5029.9 2716.49  5044.1 2719.17  5100.3 2717.89  5150.1 2720.67
  5203.5 2720.93  5279.9 2717.08  5374.6 2715.42  5406.7 2716.58  5437.7 2722.03
  5456.6  2734.3  5460.7 2735.97  5478.8 2740.47  5500.2  2744.2  5523.6 2751.78
#Mann= 3 ,-1 , 0
  4328.5     .07       0  4972.9     .05       0  5029.9     .07       0
#XS Ineff= 2 , 0
       0                    5160       0    2725
Permanent Ineff=
       F       F
#Block Obstruct= 1 ,-1
    5260    5310    2727
Bank Sta=4972.9,5029.9
Exp/Cntr=0.5,0.3

Type RM Length L Ch R = 1 ,50661   ,112,112,112
BEGIN DESCRIPTION:
XS 148
END DESCRIPTION:
XS GIS Cut Line= 5
       1056084.8       870159.73      1055713.05       870245.78
      1055527.18       870376.58      1055337.86       870266.44
      1054914.48       870610.65
#Sta/Elev= 30
  4494.5 2754.86  4529.8 2730.67  4536.3 2728.12  4552.1 2722.99  4579.3 2719.21
  4599.2 2714.55  4607.8 2718.46    4708 2716.86  4782.2  2713.8  4930.2  2716.6
  4946.9  2718.3  4969.4 2716.67  4987.8 2711.83  4992.8  2704.9  5009.8  2704.9
  5030.4 2711.91  5036.4 2713.61  5067.4 2714.13  5269.3 2711.25  5397.6 2712.63
  5467.7 2710.57    5484 2706.96  5504.4 2705.74  5547.2 2709.31  5696.1  2713.7
  5720.9 2716.37  5735.8 2722.89  5769.6 2741.58  5819.9 2745.48    5868 2755.03
#Mann= 3 ,-1 , 0
  4494.5     .07       0  4987.8     .05       0  5030.4     .07       0
#XS Ineff= 3 ,-1
    4450  4923.5    2720    5076    5210    2713    5210    5800    2725
Permanent Ineff=
       F       F       F
Bank Sta=4987.8,5030.4
Exp/Cntr=0.5,0.3

Type RM Length L Ch R = 3 ,50600   ,,,
BEGIN DESCRIPTION:
XS 147 TOR
Structure ID: XS 147
Approximate Survey Structure
END DESCRIPTION:
Bridge Culvert--1,0,-1,-1, 0
Deck Dist Width WeirC Skew NumUp NumDn MinLoCord MaxHiCord MaxSubmerge Is_Ogee
54,14,3,0, 60, 60, , , , 0, 1,1,,
  4460.5    4503  4511.6    4534  4549.5  4571.6  4586.3  4589.1  4601.7  4678.9
  4735.2  4794.9  4815.3  4850.7  4888.9  4901.8  4931.1  4946.3  4977.5  4977.5
  5022.5  5022.5  5045.6  5072.4  5080.9  5092.8  5096.6  5169.5  5196.1  5208.8
  5238.4  5270.2  5293.9  5368.9  5421.2  5437.4    5458  5458.6  5461.3  5520.8
  5545.1  5578.8  5610.2  5671.5  5696.9  5709.7  5722.3  5728.7  5757.9  5772.9
  5791.7  5797.5  5801.4  5806.7  5821.4  5830.4  5837.1  5845.5  5848.9  5880.9
 2754.47 2739.87 2733.97 2724.13 2720.12 2717.23 2714.25 2715.58 2717.21 2716.05
 2715.86 2713.37 2713.05 2713.77 2715.96 2716.17 2715.57 2717.42 2715.68 2715.68
 2714.88 2714.88 2714.43 2712.95 2711.77 2710.87 2711.18 2709.51 2709.56 2709.05
 2709.32 2708.89 2710.17 2711.54 2710.08 2708.21 2704.56 2705.04 2705.53 2708.96
 2709.49 2709.08 2710.21 2710.65 2712.05 2713.44 2715.53 2718.05 2734.58  2740.9
 2745.19 2746.02 2747.29 2749.58 2757.89 2761.37 2765.79 2768.91 2770.58 2778.41
  2681.5  2681.5  2681.5  2681.5  2681.5  2681.5  2681.5  2681.5  2681.5  2681.5
  2681.5  2681.5  2681.5  2681.5  2681.5  2681.5  2681.5  2681.5  2681.5 2713.68
 2712.92  2681.5  2681.5  2681.5  2681.5  2681.5  2681.5  2681.5  2681.5  2681.5
  2681.5  2681.5  2681.5  2681.5  2681.5  2681.5  2681.5  2681.5  2681.5  2681.5
  2681.5  2681.5  2681.5  2681.5  2681.5  2681.5  2681.5  2681.5  2681.5  2681.5
  2681.5  2681.5  2681.5  2681.5  2681.5  2681.5  2681.5  2681.5  2681.5  2681.5
  4460.5    4503  4511.6    4534  4549.5  4571.6  4586.3  4589.1  4601.7  4678.9
  4735.2  4794.9  4815.3  4850.7  4888.9  4901.8  4931.1  4946.3  4977.5  4977.5
  5022.5  5022.5  5045.6  5072.4  5080.9  5092.8  5096.6  5169.5  5196.1  5208.8
  5238.4  5270.2  5293.9  5368.9  5421.2  5437.4    5458  5458.6  5461.3  5520.8
  5545.1  5578.8  5610.2  5671.5  5696.9  5709.7  5722.3  5728.7  5757.9  5772.9
  5791.7  5797.5  5801.4  5806.7  5821.4  5830.4  5837.1  5845.5  5848.9  5880.9
 2754.47 2739.87 2733.97 2724.13 2720.12 2717.23 2714.25 2715.58 2717.21 2716.05
 2715.86 2713.37 2713.05 2713.77 2715.96 2716.17 2715.57 2717.42 2715.68 2715.68
 2714.88 2714.88 2714.43 2712.95 2711.77 2710.87 2711.18 2709.51 2709.56 2709.05
 2709.32 2708.89 2710.17 2711.54 2710.08 2708.21 2704.56 2705.04 2705.53 2708.96
 2709.49 2709.08 2710.21 2710.65 2712.05 2713.44 2715.53 2718.05 2734.58  2740.9
 2745.19 2746.02 2747.29 2749.58 2757.89 2761.37 2765.79 2768.91 2770.58 2778.41
  2681.5  2681.5  2681.5  2681.5  2681.5  2681.5  2681.5  2681.5  2681.5  2681.5
  2681.5  2681.5  2681.5  2681.5  2681.5  2681.5  2681.5  2681.5  2681.5 2713.68
 2712.92  2681.5  2681.5  2681.5  2681.5  2681.5  2681.5  2681.5  2681.5  2681.5
  2681.5  2681.5  2681.5  2681.5  2681.5  2681.5  2681.5  2681.5  2681.5  2681.5
  2681.5  2681.5  2681.5  2681.5  2681.5  2681.5  2681.5  2681.5  2681.5  2681.5
  2681.5  2681.5  2681.5  2681.5  2681.5  2681.5  2681.5  2681.5  2681.5  2681.5
Abutment Skew #Up #Dn= , 2 , 2
  4977.5  4977.6
 2709.46 2713.66
  4977.5    4980
    2710 2710.08
Abutment Skew #Up #Dn= , 2 , 2
    5020  5022.5
 2705.86 2712.93
    5020  5022.5
 2709.52    2710
BR Coef= 1 , 1 , 0 ,1.25, 0 ,,,0.8,0,2,0,
WSPro=,,,, 1 ,,,, 0 ,,,, 0 ,,,,-1 ,-1 ,-1 , 0 , 0 , 0 , 0 , 0
BC Design=,, 0 ,, 0 ,,,,,,
BC HTab HWMax=2755.03