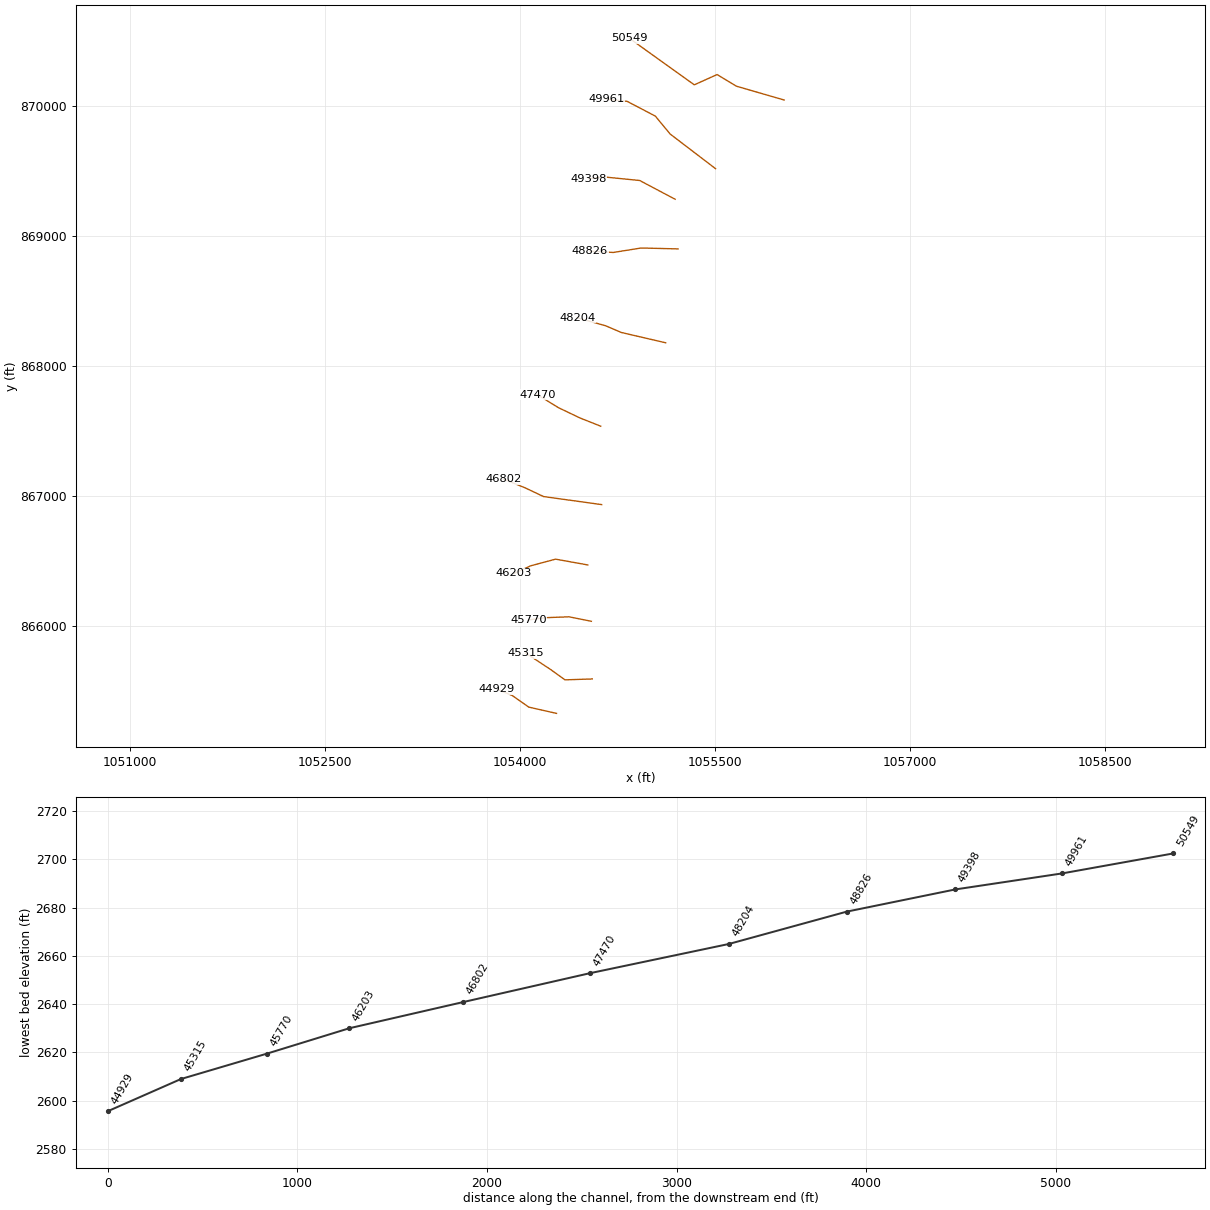
HEC-RAS study lds_big_rock_crk.prj: Big Rock Creek Limited Detail Study

--- lds_big_rock_crk.g01 (geometry) --- (continued)

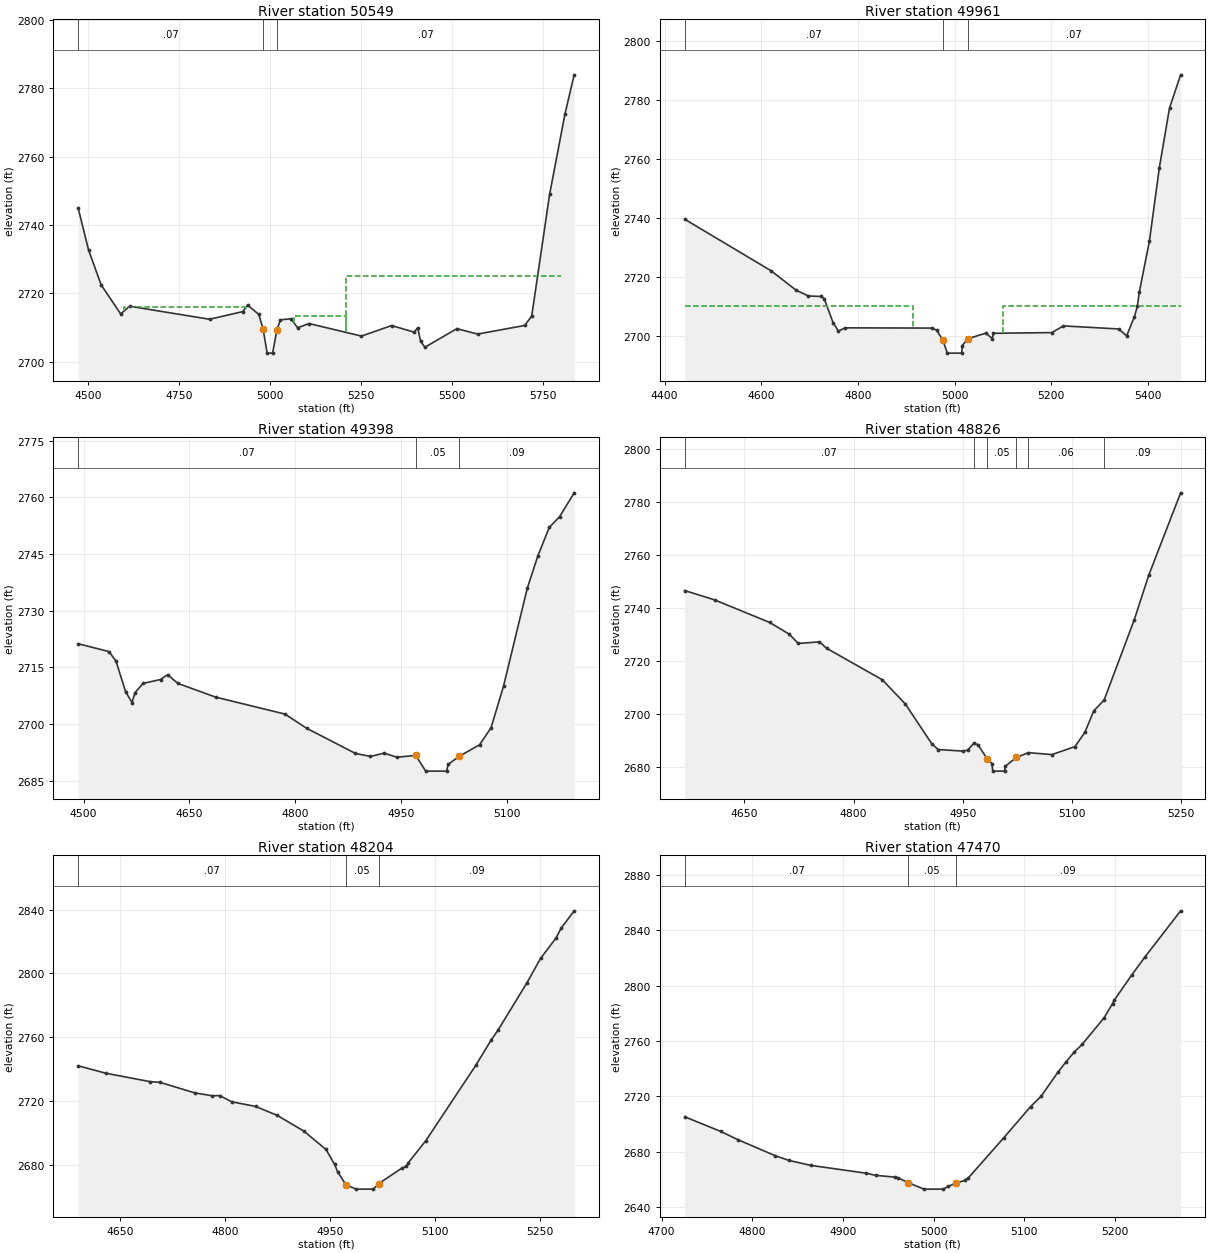
Type RM Length L Ch R = 1 ,50549   ,588,588,588
BEGIN DESCRIPTION:
XS 146
END DESCRIPTION:
XS GIS Cut Line= 5
      1056033.17       870049.58      1055664.86       870156.29
      1055516.85       870245.78       1055341.3       870166.61
      1054842.19        870524.6
#Sta/Elev= 30
  4473.2 2744.91  4501.6  2732.7  4536.3 2722.47  4589.9 2713.98  4614.3 2716.23
  4834.4 2712.41  4925.7 2714.67  4938.7 2716.54  4969.6 2713.84  4981.4 2709.56
  4992.5  2702.5  5007.5  2702.5  5019.5 2709.37  5028.9 2712.23  5058.1 2712.57
  5076.3  2709.9  5107.5 2711.16  5251.8 2707.49  5334.6 2710.57  5396.2 2708.66
  5406.2 2709.87  5414.5 2705.96  5426.1 2704.23  5514.2 2709.66    5571 2708.08
  5700.1 2710.59  5719.7 2713.31    5769 2749.01  5811.2 2772.53  5836.4 2783.96
#Mann= 3 ,-1 , 0
  4473.2     .07       0  4981.4     .05       0  5019.5     .07       0
#XS Ineff= 3 ,-1
    4600  4933.5    2716  5066.5    5210 2713.25    5210    5800    2725
Permanent Ineff=
       F       F       F
Bank Sta=4981.4,5019.5
Exp/Cntr=0.5,0.3

Type RM Length L Ch R = 1 ,49961   ,563,563,563
BEGIN DESCRIPTION:
XS 145
END DESCRIPTION:
XS GIS Cut Line= 5
      1055505.21       869520.83      1055155.43       869787.98
      1055041.84       869925.67      1054824.98       870039.26
       1054663.2       870056.47
#Sta/Elev= 30
  4441.6 2739.53  4620.2 2722.09  4671.9 2715.53  4697.7 2713.53    4724 2713.38
  4730.4  2712.6  4748.8 2704.46  4759.5  2701.7  4773.9 2702.75  4952.6 2702.67
  4963.2 2701.96  4975.7 2698.55  4985.2 2694.19  5014.8 2694.19  5016.1 2696.76
  5027.1 2699.02  5064.8 2700.97  5078.1 2699.12  5080.5 2700.91  5201.2 2701.14
  5225.3 2703.41  5339.3 2702.37  5356.2 2700.06    5372 2706.44  5378.2 2709.98
  5382.4 2714.91  5403.3 2732.19  5423.8    2757  5444.8 2777.13  5467.8 2788.41
#Mann= 3 ,-1 , 0
  4441.6     .07       0  4975.7     .05       0  5027.1     .07       0
#XS Ineff= 2 , 0
       0    4915    2710    5100       0    2710
Permanent Ineff=
       F       F
Bank Sta=4975.7,5027.1
Exp/Cntr=0.3,0.1

Type RM Length L Ch R = 1 ,49398   ,572,572,572
BEGIN DESCRIPTION:
XS 144
END DESCRIPTION:
XS GIS Cut Line= 4
      1055194.03       869285.57      1054921.36         869430.
      1054645.99       869457.54      1054528.96       869443.77
#Sta/Elev= 30
  4492.5 2721.25  4536.1 2719.18  4546.1 2716.66  4559.7 2708.56  4568.8 2705.68
    4573 2708.31  4584.4 2710.76  4609.2 2711.79  4619.3 2713.07  4633.8 2710.76
  4687.3 2707.13  4785.6 2702.65  4816.4 2698.89  4885.5 2692.24  4906.8 2691.43
  4926.2 2692.31  4944.6 2691.23  4971.1 2691.71  4985.2 2687.55  5014.8 2687.55
  5017.1 2689.35  5033.1 2691.51  5061.6 2694.53  5077.8    2699  5095.6 2710.06
  5129.2  2735.9  5144.2 2744.47  5160.4 2752.02  5175.2  2754.9  5195.7 2761.18
#Mann= 3 ,-1 , 0
  4492.5     .07       0  4971.1     .05       0  5033.1     .09       0
Bank Sta=4971.1,5033.1
Exp/Cntr=0.3,0.1

Type RM Length L Ch R = 1 ,48826   ,622,622,622
BEGIN DESCRIPTION:
XS 143
END DESCRIPTION:
XS GIS Cut Line= 4
      1055217.39       868903.35      1054931.69       868910.24
      1054718.28       868875.82      1054539.29       868886.14
#Sta/Elev= 30
    4568 2746.57  4609.4    2743  4684.6 2734.53  4711.5  2730.1    4724 2726.58
  4753.1 2727.17    4763 2724.74  4839.6 2712.84  4871.1  2703.7  4907.7 2688.58
  4916.3 2686.51  4950.8  2685.9  4956.8 2686.33  4965.2 2688.87  4970.6 2688.39
  4983.3  2683.1    4990 2681.22  4991.2 2678.35  5007.5 2678.35    5008  2680.1
  5023.4  2683.5  5040.1 2685.32  5072.5  2684.6  5104.2 2687.63  5117.8 2693.08
    5130 2701.17  5144.1 2705.16  5185.5  2735.5  5205.4 2752.33  5249.2 2783.47
#Mann= 6 ,-1 , 0
    4568     .07       0  4965.2     .09       0  4983.3     .05       0
  5023.4     .09       0  5040.1     .06       0  5144.1     .09       0
Bank Sta=4983.3,5023.4
Exp/Cntr=0.3,0.1

Type RM Length L Ch R = 1 ,48204   ,734,734,734
BEGIN DESCRIPTION:
XS 142
END DESCRIPTION:
XS GIS Cut Line= 4
      1055121.01       868180.51      1054780.23       868259.68
      1054659.76       868311.31      1054439.46       868373.27
#Sta/Elev= 30
  4589.6 2742.15  4629.1  2737.5  4692.8 2732.21    4706 2731.86  4756.6 2725.17
  4781.6 2723.37  4791.9 2723.53  4809.5  2719.6  4843.5 2716.71  4874.6 2711.07
  4912.5 2701.26  4944.1  2689.8  4956.4 2680.49  4960.9  2675.8  4972.7  2667.6
  4987.4 2664.93    5012 2664.93  5019.5 2668.34  5052.9 2678.13  5059.1 2679.12
  5062.1 2681.52  5087.2 2695.37  5158.5 2742.42  5180.5 2758.27  5190.2 2764.34
  5231.8 2794.16  5251.3 2809.44  5273.2 2822.08  5280.7 2828.34  5299.3 2839.19
#Mann= 3 , 0 , 0
  4589.6     .07       0  4972.7     .05       0  5019.5     .09       0
Bank Sta=4972.7,5019.5
Exp/Cntr=0.3,0.1

Type RM Length L Ch R = 1 ,47470   ,668,668,668
BEGIN DESCRIPTION:
XS 141
END DESCRIPTION:
XS GIS Cut Line= 4
      1054621.36       867538.09      1054460.12       867602.23
      1054294.89        867681.4      1054133.11       867781.22
#Sta/Elev= 30
  4725.4 2705.13    4765 2694.56    4784 2688.56  4825.4 2676.92  4840.5 2673.53
  4864.2    2670  4924.9 2664.37  4935.9 2662.78  4956.9 2661.49  4960.4 2661.04
  4971.9 2657.46  4989.3 2652.79  5010.8 2652.79    5016 2654.78  5024.2 2656.99
    5034 2659.04  5037.9 2660.66  5077.3 2689.93  5106.9 2712.51  5118.3 2719.81
  5136.9 2737.26  5145.7 2744.62  5154.6 2751.62  5163.7 2757.46  5187.9 2776.68
  5197.2 2786.92  5199.2 2789.51  5218.3 2807.54  5233.3 2820.95  5272.3 2854.04
#Mann= 3 , 0 , 0
  4725.4     .07       0  4971.9     .05       0  5024.2     .09       0
Bank Sta=4971.9,5024.2
Exp/Cntr=0.3,0.1

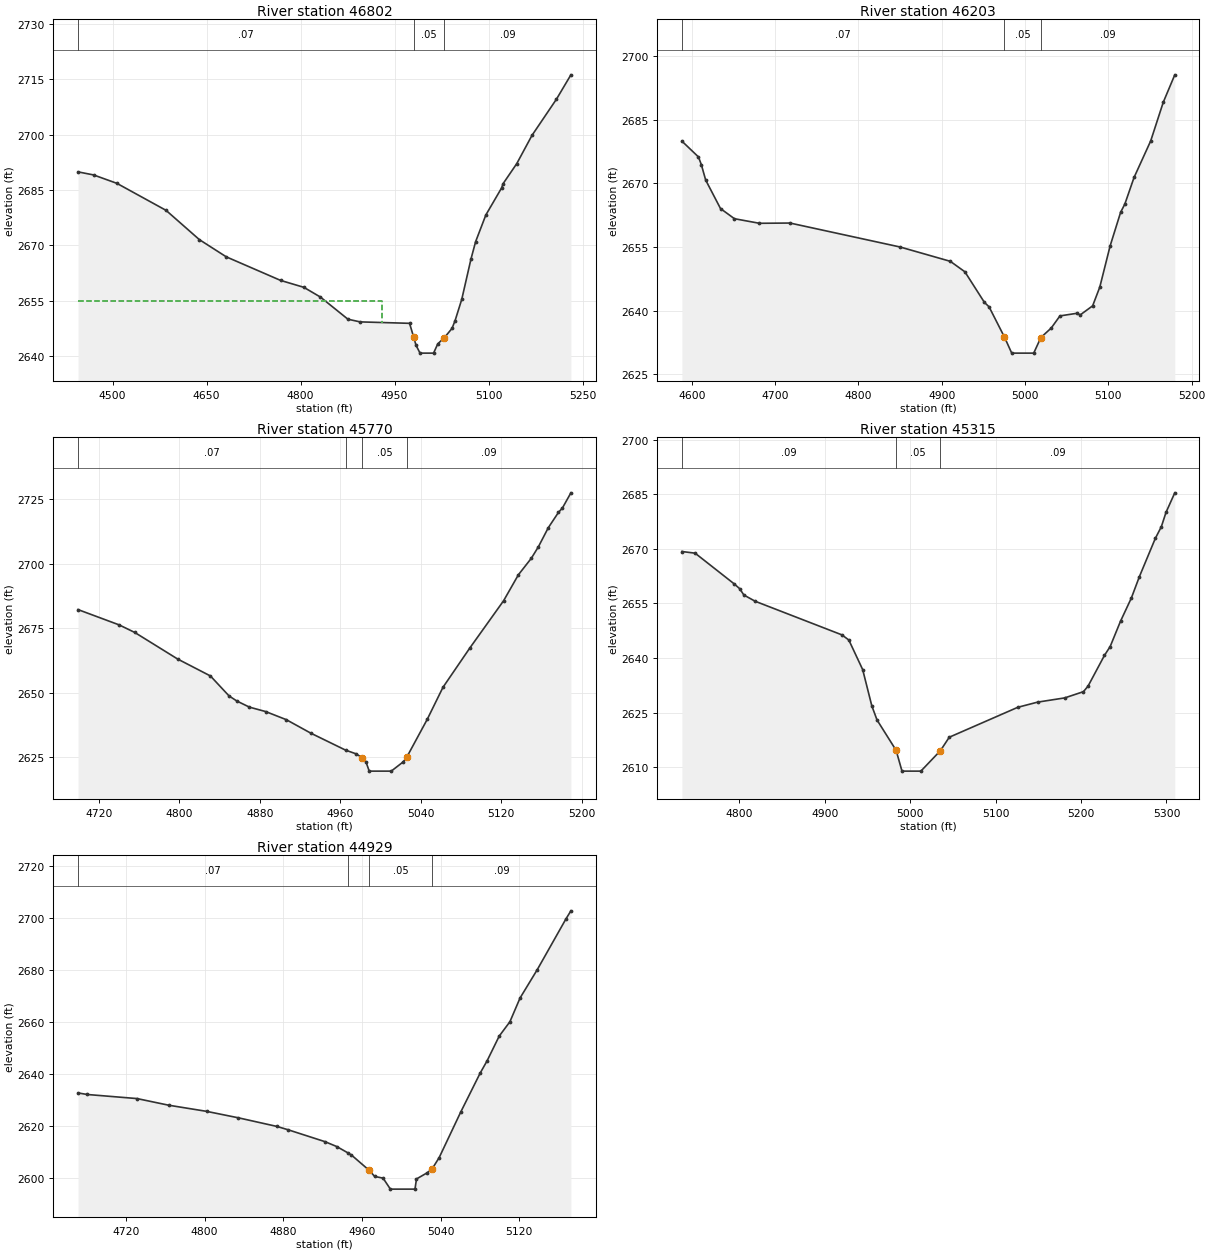
Type RM Length L Ch R = 1 ,46802   ,599,599,599
BEGIN DESCRIPTION:
XS 140
END DESCRIPTION:
XS GIS Cut Line= 4
      1054628.78       866934.46       1054181.3       866996.42
      1054043.62       867061.82      1053874.96       867130.66
#Sta/Elev= 30
    4445  2689.9  4469.8 2689.07  4506.9  2686.8  4585.4 2679.48  4638.5 2671.56
  4681.5 2666.89    4768 2660.52  4805.2 2658.64  4831.7    2656  4875.6    2650
    4895 2649.28  4973.9 2648.89 4980.49 2645.12 4984.26 2642.93  4990.6 2640.82
  5012.2 2640.82  5018.9 2643.33  5029.6 2645.05  5041.6 2647.51  5046.5 2649.61
  5057.2 2655.41  5071.9 2666.32  5079.3 2671.01  5095.6 2678.23  5120.7 2685.54
  5123.2 2686.73  5144.9 2692.13  5169.2 2699.78  5208.3  2709.6  5231.3 2716.18
#Mann= 3 , 0 , 0
    4445     .07       0 4980.49     .05       0  5029.6     .09       0
#XS Ineff= 2 , 0
       0  4930.1    2655               0
Permanent Ineff=
       F       F
Bank Sta=4980.49,5029.6
Exp/Cntr=0.3,0.1

Type RM Length L Ch R = 1 ,46203   ,433,433,433
BEGIN DESCRIPTION:
XS 139
END DESCRIPTION:
XS GIS Cut Line= 4
      1054522.08       866469.77      1054274.24       866514.52
      1054081.48       866462.89      1053954.12       866404.37
#Sta/Elev= 30
  4588.2 2679.93    4608 2676.22  4611.5 2674.39  4616.7 2670.76  4634.5 2664.05
  4651.2 2661.66  4681.2 2660.58  4717.9 2660.64  4850.1 2654.99  4910.3 2651.62
  4927.8 2649.15  4951.2 2641.95  4956.8  2640.9  4975.3 2633.76    4984 2629.99
  5010.4 2629.99    5019 2633.67  5031.4  2635.9  5041.9 2638.76  5062.7 2639.39
  5066.1 2638.98  5081.1 2641.13  5089.7 2645.55  5102.1 2655.25  5114.7 2663.17
  5119.8 2665.13  5130.8 2671.37  5150.8 2679.99  5165.9 2689.11  5179.7 2695.56
#Mann= 3 , 0 , 0
  4588.2     .07       0  4975.3     .05       0    5019     .09       0
Bank Sta=4975.3,5019
Exp/Cntr=0.3,0.1

Type RM Length L Ch R = 1 ,45770   ,455,455,455
BEGIN DESCRIPTION:
XS 138
END DESCRIPTION:
XS GIS Cut Line= 4
      1054549.61       866036.06      1054377.51       866070.48
      1054191.63        866063.6      1054064.27       866046.39
#Sta/Elev= 30
  4699.3 2682.16  4740.2 2676.22  4755.7 2673.29  4798.3 2662.99  4830.9 2656.42
  4849.4 2648.68  4857.2 2646.69  4869.7 2644.32  4885.8 2642.61  4906.3 2639.47
  4930.8 2634.21  4965.3 2627.64  4975.4 2626.25  4981.9 2624.72  4985.5 2623.12
  4988.8  2619.5  5010.7  2619.5  5022.7 2623.13  5026.3 2625.05  5046.5 2639.62
  5062.1 2652.01  5088.6 2667.15  5122.4 2685.61  5137.1 2695.67    5150  2702.1
    5157 2706.54  5166.8 2713.91  5176.9 2719.85  5180.9  2721.6  5189.3 2727.46
#Mann= 4 ,-1 , 0
  4699.3     .07       0  4965.3     .09       0  4981.9     .05       0
  5026.3     .09       0
Bank Sta=4981.9,5026.3
Exp/Cntr=0.3,0.1

Type RM Length L Ch R = 1 ,45315   ,386,386,386
BEGIN DESCRIPTION:
XS 137
END DESCRIPTION:
XS GIS Cut Line= 4
       1054556.5       865592.03      1054346.53       865585.14
      1054236.38       865664.31      1054043.62       865791.67
#Sta/Elev= 30
    4733 2669.24  4748.4 2668.79  4793.9  2660.4  4800.5 2659.05  4805.5 2657.29
  4818.8 2655.57  4920.3 2646.34  4928.3 2644.93  4944.5 2636.81  4955.2 2626.84
  4961.3 2622.97  4983.6 2614.65  4990.5 2608.93  5012.6 2608.93  5035.5 2614.56
  5045.8 2618.24    5126 2626.46  5149.2 2627.88  5180.9 2629.04  5202.8 2630.75
  5208.2 2632.27  5227.4 2640.71  5234.1 2643.15  5246.2  2650.1  5258.9 2656.48
  5268.3 2662.35  5286.9 2672.83    5294 2676.07  5299.4 2679.97  5309.7 2685.36
#Mann= 3 ,-1 , 0
    4733     .09       0  4983.6     .05       0  5035.5     .09       0
Bank Sta=4983.6,5035.5
Exp/Cntr=0.3,0.1

Type RM Length L Ch R = 1 ,44929   ,493,493,493
BEGIN DESCRIPTION:
XS 136
END DESCRIPTION:
XS GIS Cut Line= 4
      1054281.13       865326.98      1054067.71       865375.17
      1053940.36       865464.67      1053823.32       865512.86
#Sta/Elev= 30
  4671.4 2632.57  4680.8 2631.97  4731.4  2630.4  4763.5 2627.85    4802 2625.49
  4834.4    2623  4873.5 2619.69  4884.7 2618.43  4922.4 2613.83  4934.3 2611.96
  4945.3 2609.61  4949.3 2608.69  4967.5 2602.75  4972.9 2600.45  4981.5 2599.79
  4988.9 2595.57  5013.9 2595.57 5015.43 2599.48 5026.31 2601.86  5031.2 2603.28
  5038.5 2607.71  5060.2 2625.06  5080.1 2640.16  5087.2 2644.92  5099.5 2654.42
  5110.4 2659.96  5120.7 2669.08  5138.3 2680.05  5167.3 2699.47  5172.4 2702.62
#Mann= 4 ,-1 , 0
  4671.4     .07       0  4945.3     .09       0  4967.5     .05       0
  5031.2     .09       0
Bank Sta=4967.5,5031.2
Exp/Cntr=0.3,0.1