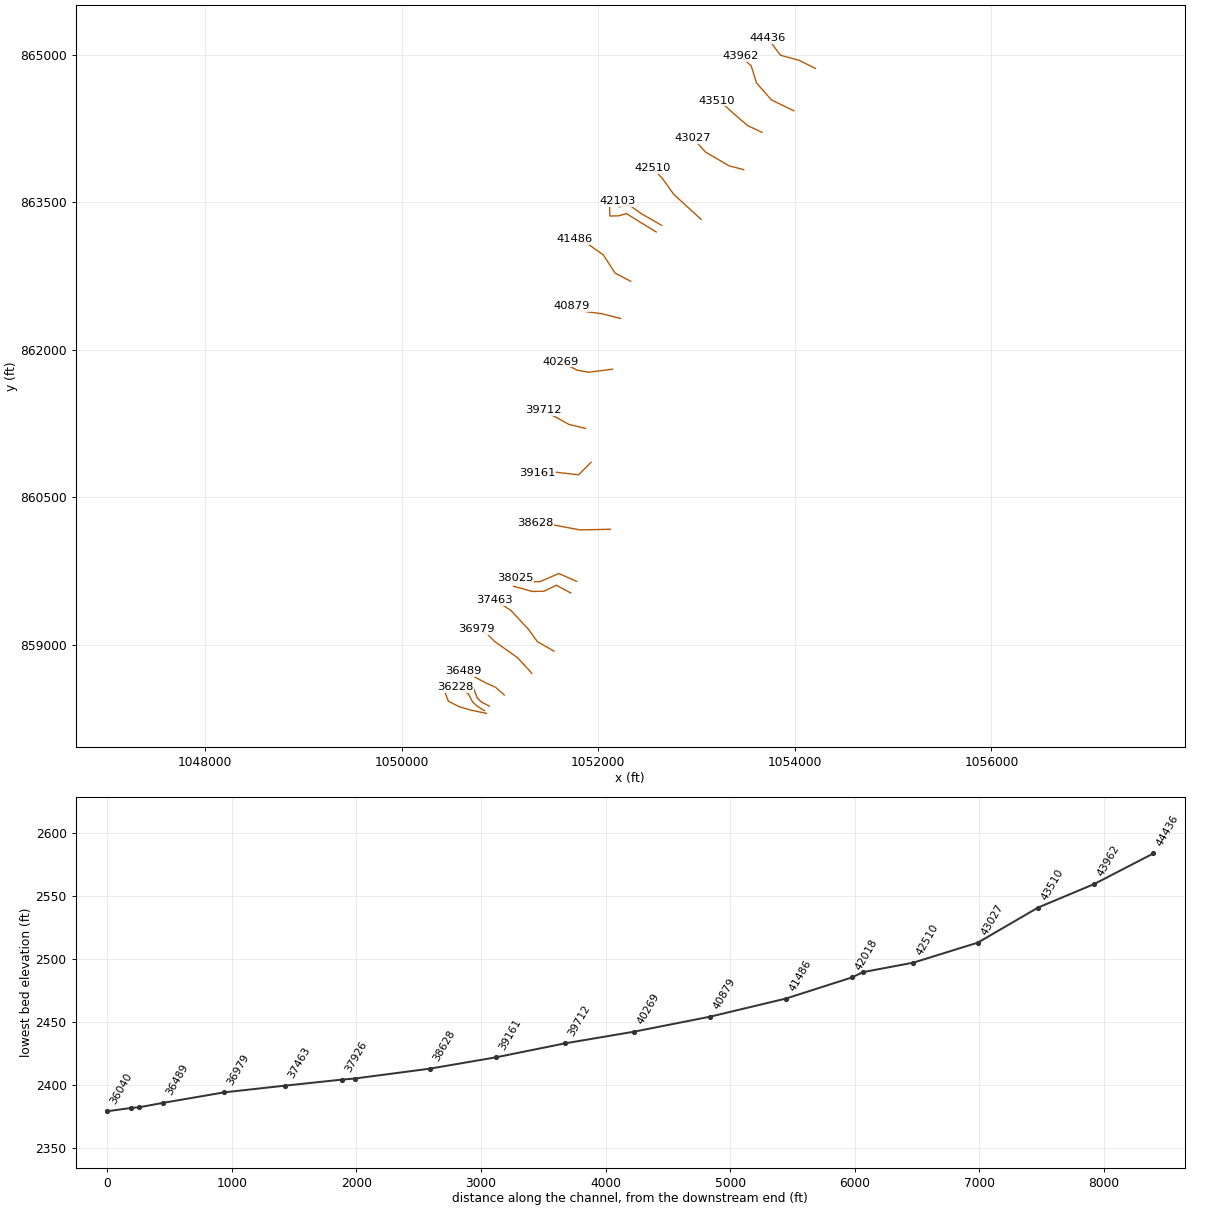
HEC-RAS study lds_big_rock_crk.prj: Big Rock Creek Limited Detail Study

--- lds_big_rock_crk.g01 (geometry) --- (continued)

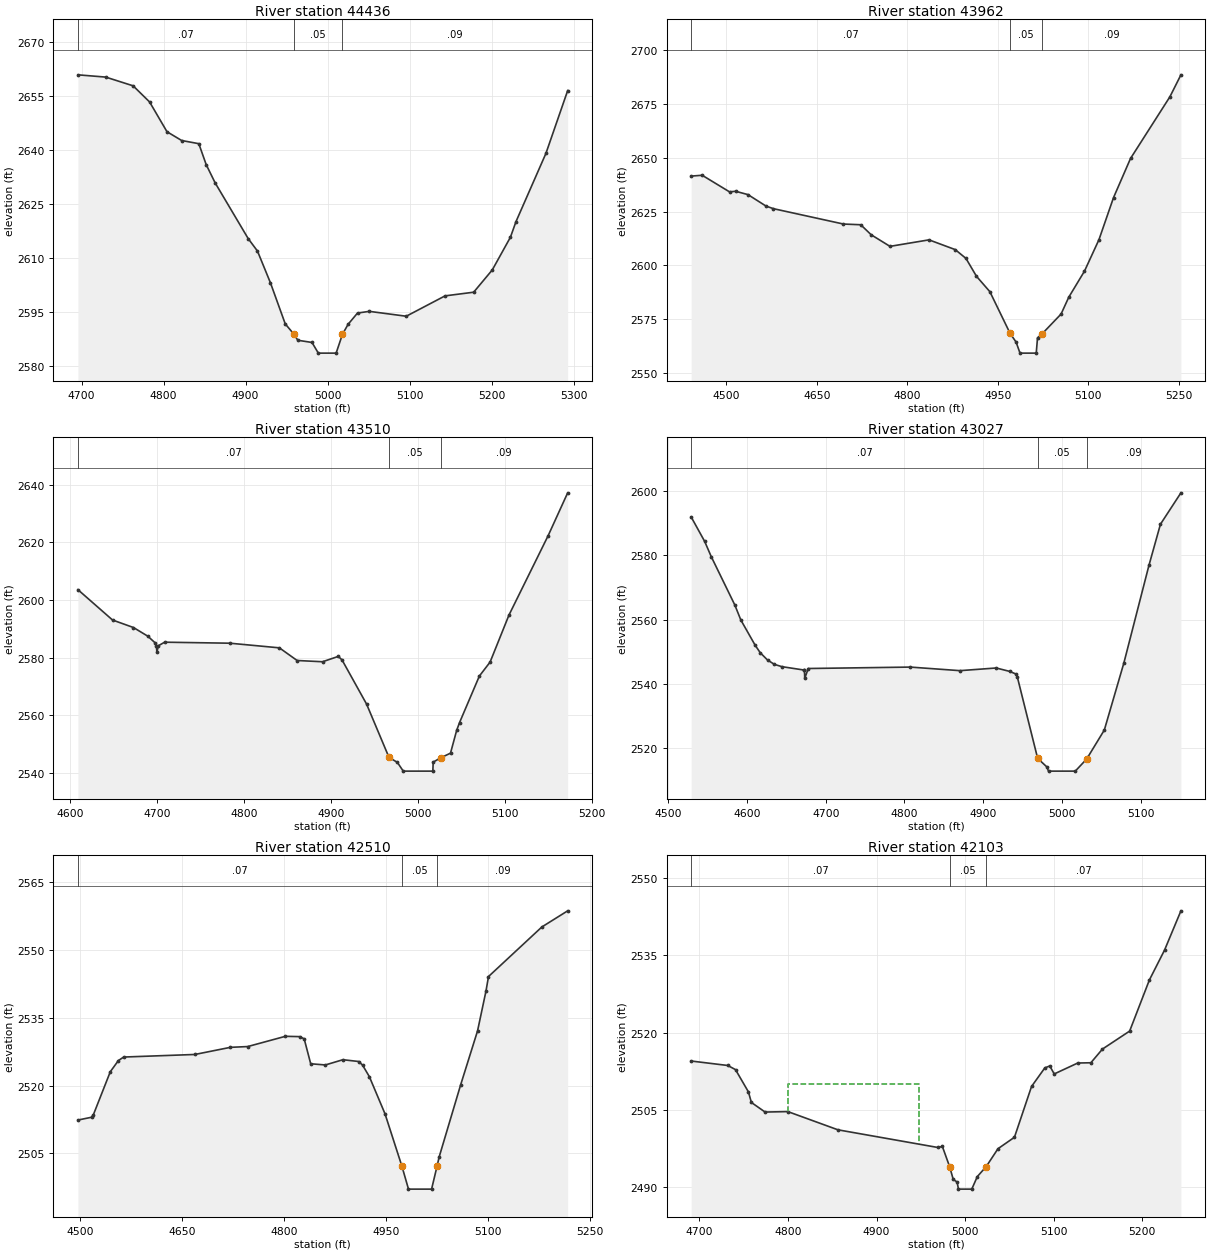
Type RM Length L Ch R = 1 ,44436   ,474,474,474
BEGIN DESCRIPTION:
XS 135
END DESCRIPTION:
XS GIS Cut Line= 4
      1054208.84        864862.3      1054043.62       864944.91
       1053854.3       864996.54       1053723.5       865168.65
#Sta/Elev= 30
  4695.6 2660.76  4729.5 2660.13  4762.9 2657.71    4783 2653.23  4804.2 2644.97
  4822.1 2642.53    4843 2641.65    4852 2635.84  4862.9 2630.78  4903.2 2615.31
  4914.5 2611.85  4930.3 2603.05  4948.4 2591.62  4959.1 2588.74  4963.7 2587.09
    4981 2586.48  4988.7 2583.52  5010.4 2583.52 5018.13 2588.74    5025 2591.52
  5036.5 2594.65  5050.9 2595.11  5095.9 2593.76  5143.2 2599.41  5178.1 2600.43
  5200.8 2606.62  5222.9 2615.69  5229.7 2620.03  5266.2 2638.97  5292.7 2656.39
#Mann= 3 , 0 , 0
  4695.6     .07       0  4959.1     .05       0 5018.13     .09       0
Bank Sta=4959.1,5018.13
Exp/Cntr=0.3,0.1

Type RM Length L Ch R = 1 ,43962   ,452,452,452
BEGIN DESCRIPTION:
XS 134
END DESCRIPTION:
XS GIS Cut Line= 5
      1053988.55       864432.03      1053761.37       864542.18
      1053609.91       864714.28      1053554.84       864889.83
      1053444.69       864986.21
#Sta/Elev= 30
  4441.4 2641.49  4459.7 2641.88    4505 2634.18  4515.2 2634.44  4535.6  2632.9
  4565.5 2627.58  4577.7 2626.38  4693.9 2619.24  4722.6 2618.91  4739.9 2614.26
  4771.1 2608.88  4835.8  2611.9  4879.3 2607.37  4897.1 2603.28  4914.5 2594.99
  4936.7 2587.85 4970.18 2568.53  4980.2 2564.45  4986.7 2559.33  5013.6 2559.33
  5015.7 2566.41 5023.68 2568.38  5054.8 2577.48  5067.5 2585.27  5093.6 2597.39
  5117.6 2611.99  5141.7 2631.48  5169.9 2649.66  5235.2 2678.29  5253.5 2688.49
#Mann= 3 , 0 , 0
  4441.4     .07       0 4970.18     .05       0 5023.68     .09       0
Bank Sta=4970.18,5023.68
Exp/Cntr=0.3,0.1

Type RM Length L Ch R = 1 ,43510   ,483,483,483
BEGIN DESCRIPTION:
XS 133
END DESCRIPTION:
XS GIS Cut Line= 5
      1053664.99       864211.73      1053520.42       864280.58
      1053382.73       864397.61      1053293.24       864480.22
      1053207.18       864531.85
#Sta/Elev= 30
    4609 2603.55  4648.8 2593.03  4672.9 2590.42  4689.3 2587.43  4697.6 2585.16
  4699.2 2584.19  4699.8 2581.91  4701.5 2584.11  4708.7 2585.34  4783.6 2584.99
  4840.6 2583.38    4861 2578.99  4890.2 2578.56  4908.3 2580.41  4912.6  2579.2
  4940.8  2563.9  4966.6  2545.4  4976.2 2543.68    4983 2540.64    5017 2540.64
  5017.4 2543.76  5025.9 2545.23  5037.3 2546.87  5044.4 2554.79  5047.7 2557.47
  5070.5 2573.61  5082.8 2578.44  5104.5 2594.74  5149.5 2622.24    5172 2637.12
#Mann= 3 , 0 , 0
    4609     .07       0  4966.6     .05       0  5025.9     .09       0
Bank Sta=4966.6,5025.9
Exp/Cntr=0.3,0.1

Type RM Length L Ch R = 1 ,43027   ,517,517,517
BEGIN DESCRIPTION:
XS 132
END DESCRIPTION:
XS GIS Cut Line= 4
      1053479.11        863833.1       1053331.1       863870.96
      1053090.15       864012.09      1052962.79       864153.22
#Sta/Elev= 30
  4529.1  2591.9  4546.3 2584.28  4554.6 2579.57  4584.6 2564.52  4592.2 2559.88
  4610.3 2552.07  4616.8 2549.72  4626.1 2547.44  4634.9 2546.08  4644.4 2545.37
  4672.8 2544.31    4673 2544.18  4673.4 2541.77  4677.9  2544.8  4807.5 2545.24
  4870.5 2544.13  4916.6 2544.96  4933.7  2543.9  4941.4 2543.11  4943.4 2542.17
  4969.2 2516.89  4980.8 2514.24    4983 2512.91    5017 2512.91  5031.5 2516.68
  5053.9 2525.68  5078.7 2546.49  5110.6 2576.87  5125.2 2589.64  5151.2 2599.39
#Mann= 3 , 0 , 0
  4529.1     .07       0  4969.2     .05       0  5031.5     .09       0
Bank Sta=4969.2,5031.5
Exp/Cntr=0.3,0.1

Type RM Length L Ch R = 1 ,42510   ,407,407,407
BEGIN DESCRIPTION:
XS 131
END DESCRIPTION:
XS GIS Cut Line= 4
       1053045.4       863327.11      1052766.59       863581.82
      1052646.12       863750.49      1052549.74       863846.87
#Sta/Elev= 30
  4496.2 2512.37  4516.5    2513  4519.1 2513.59  4543.9 2523.07  4555.8 2525.54
  4563.6 2526.32  4668.4 2526.89  4720.8 2528.47  4746.2 2528.64  4801.7 2530.91
  4822.9 2530.84  4829.4 2530.35    4839 2524.83  4860.6 2524.57  4886.4 2525.73
  4909.9 2525.33  4915.4 2524.52  4925.3    2522  4948.4 2513.76  4973.3 2502.15
    4983 2497.08    5017 2497.08 5025.04 2502.15  5028.1 2504.18  5059.8 2520.17
  5084.7 2532.12  5097.1 2540.93  5100.8 2544.14  5179.4 2555.12  5217.4 2558.69
#Mann= 3 , 0 , 0
  4496.2     .07       0  4973.3     .05       0 5025.04     .09       0
Bank Sta=4973.3,5025.04
Exp/Cntr=0.5,0.3

Type RM Length L Ch R = 1 ,42103   ,85,85,85
BEGIN DESCRIPTION:
XS 130
END DESCRIPTION:
XS GIS Cut Line= 5
      1052643.93       863266.52      1052434.95       863386.17
      1052318.67       863470.44      1052209.12       863453.58
       1052200.7       863510.88
#Sta/Elev= 30
  4690.6 2514.45    4732 2513.58  4740.7 2512.77  4755.3 2508.43  4758.6 2506.38
  4774.1 2504.51  4799.8  2504.6  4856.4 2501.05  4969.2 2497.61  4974.3 2497.81
  4982.5 2493.87  4986.6 2491.38  4990.9 2490.89  4992.5  2489.5  5007.5  2489.5
  5013.8 2491.95  5023.8 2493.89  5037.1 2497.37  5055.7  2499.6    5075 2509.49
    5090 2513.11  5095.6 2513.49  5100.6 2511.93  5127.2 2514.06    5142 2514.11
  5155.1 2516.78  5185.8 2520.28  5208.1 2530.24  5225.2 2536.05  5243.7  2543.7
#Mann= 3 ,-1 , 0
  4690.6     .07       0  4982.5     .05       0  5023.8     .07       0
#XS Ineff= 2 ,-1
    4800  4947.5    2510  5052.5    5100    2499
Permanent Ineff=
       F       F
Bank Sta=4982.5,5023.8
Exp/Cntr=0.5,0.3

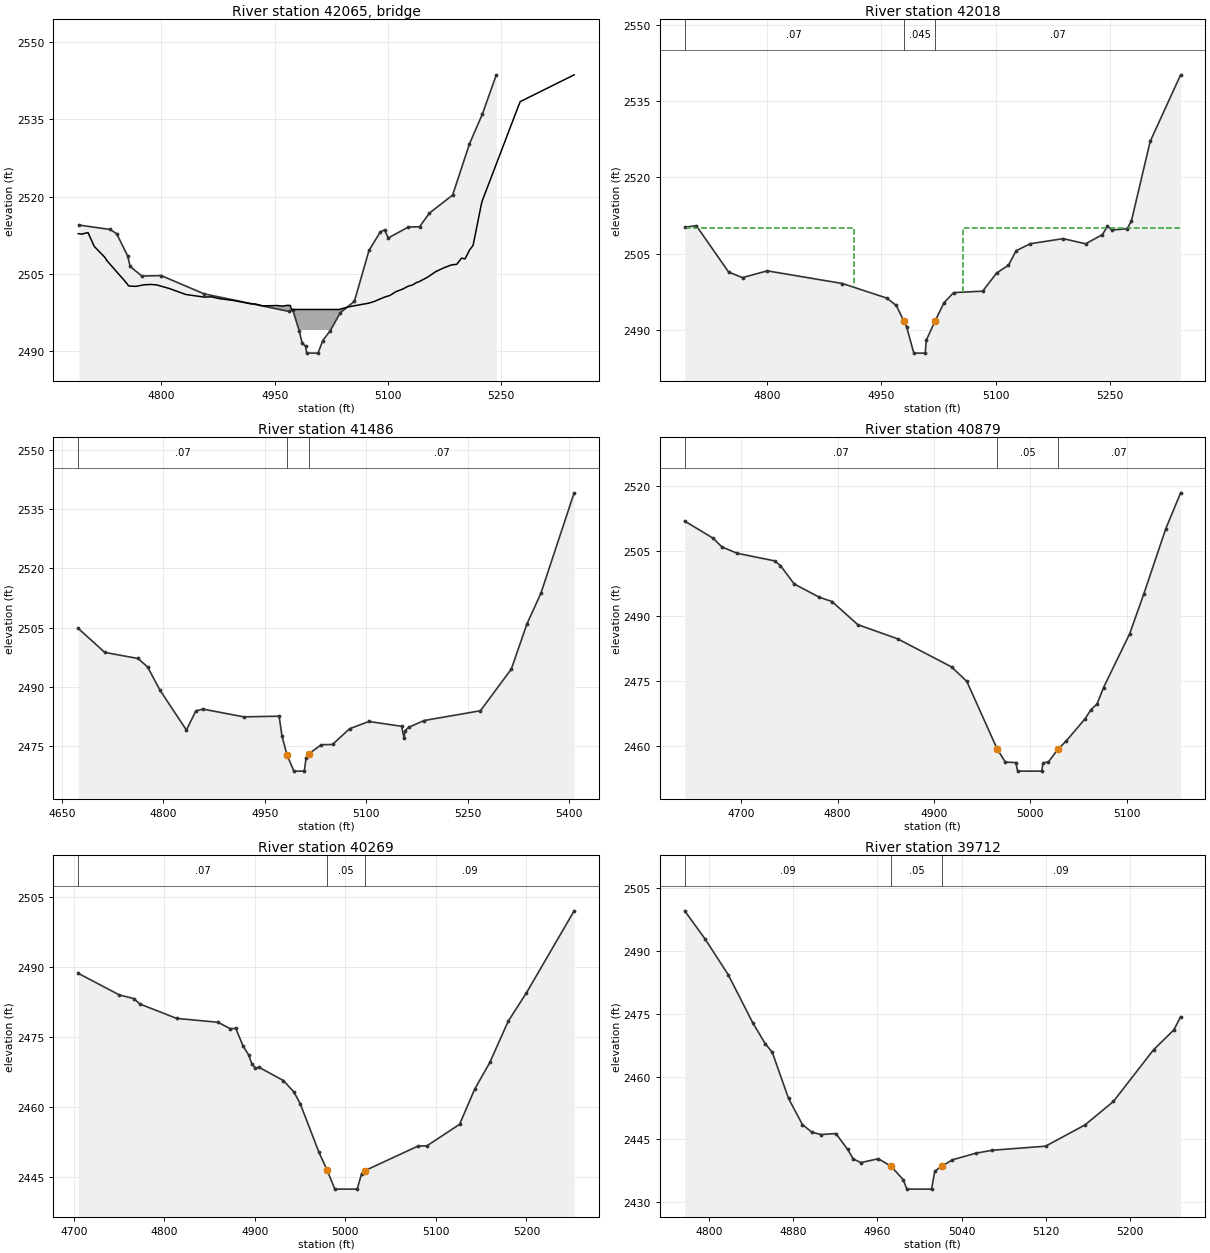
Type RM Length L Ch R = 3 ,42065   ,,,
BEGIN DESCRIPTION:
XS 129 TOR
Structure ID: XS 129
Approximate Survey Structure
END DESCRIPTION:
Bridge Culvert--1,0,-1,-1, 0
Deck Dist Width WeirC Skew NumUp NumDn MinLoCord MaxHiCord MaxSubmerge Is_Ogee
30,16,3,0, 60, 60, , , , 0, 1,1,,
  4689.8  4695.7  4696.3  4702.8    4711  4724.1    4726  4727.8  4754.3  4756.1
  4757.9  4766.4  4776.3  4785.3  4793.2  4810.4  4832.3  4856.8  4865.8  4877.7
  4895.1  4919.5    4924  4934.4  4953.7  4960.3  4967.2  4970.7  4972.5  4977.5
  4977.5  5022.5  5022.5  5035.5  5047.5  5074.3  5081.3  5096.1  5102.7    5111
  5119.4  5126.4  5133.2  5137.9  5140.7    5152  5163.6  5174.3    5184  5191.4
  5197.6  5202.2  5208.5  5212.9  5223.3  5224.8  5273.6  5274.4  5275.2  5346.8
 2512.77 2512.67 2512.76 2512.97 2510.29  2508.3 2507.96 2507.52 2503.07 2502.65
 2502.56  2502.5 2502.79 2502.88  2502.8 2502.09 2500.92 2500.41 2500.47 2500.09
 2499.76 2499.08 2499.09  2498.7 2498.77 2498.65 2498.81 2498.76    2498    2498
    2498    2498    2498    2498  2498.5 2499.22 2499.52 2500.44 2500.73  2501.5
 2501.95  2502.5 2502.81 2503.25 2503.36 2504.24 2505.38 2506.12 2506.67 2506.81
    2508 2507.85 2509.64 2510.47 2518.09 2519.06 2537.86  2538.1 2538.47  2543.7
  2469.5  2469.5  2469.5  2469.5  2469.5  2469.5  2469.5  2469.5  2469.5  2469.5
  2469.5  2469.5  2469.5  2469.5  2469.5  2469.5  2469.5  2469.5  2469.5  2469.5
  2469.5  2469.5  2469.5  2469.5  2469.5  2469.5  2469.5  2469.5  2469.5  2469.5
    2494    2494  2469.5  2469.5  2469.5  2469.5  2469.5  2469.5  2469.5  2469.5
  2469.5  2469.5  2469.5  2469.5  2469.5  2469.5  2469.5  2469.5  2469.5  2469.5
  2469.5  2469.5  2469.5  2469.5  2469.5  2469.5  2469.5  2469.5  2469.5  2469.5
  4689.8  4695.7  4696.3  4702.8    4711  4724.1    4726  4727.8  4754.3  4756.1
  4757.9  4766.4  4776.3  4785.3  4793.2  4810.4  4832.3  4856.8  4865.8  4877.7
  4895.1  4919.5    4924  4934.4  4953.7  4960.3  4967.2  4970.7  4972.5  4977.5
  4977.5  5022.5  5022.5  5035.5  5047.5  5074.3  5081.3  5096.1  5102.7    5111
  5119.4  5126.4  5133.2  5137.9  5140.7    5152  5163.6  5174.3    5184  5191.4
  5197.6  5202.2  5208.5  5212.9  5223.3  5224.8  5273.6  5274.4  5275.2  5346.8
 2512.77 2512.67 2512.76 2512.97 2510.29  2508.3 2507.96 2507.52 2503.07 2502.65
 2502.56  2502.5 2502.79 2502.88  2502.8 2502.09 2500.92 2500.41 2500.47 2500.09
 2499.76 2499.08 2499.09  2498.7 2498.77 2498.65 2498.81 2498.76    2498    2498
    2498    2498    2498    2498  2498.5 2499.22 2499.52 2500.44 2500.73  2501.5
 2501.95  2502.5 2502.81 2503.25 2503.36 2504.24 2505.38 2506.12 2506.67 2506.81
    2508 2507.85 2509.64 2510.47 2518.09 2519.06 2537.86  2538.1 2538.47  2543.7
  2469.5  2469.5  2469.5  2469.5  2469.5  2469.5  2469.5  2469.5  2469.5  2469.5
  2469.5  2469.5  2469.5  2469.5  2469.5  2469.5  2469.5  2469.5  2469.5  2469.5
  2469.5  2469.5  2469.5  2469.5  2469.5  2469.5  2469.5  2469.5  2469.5  2469.5
    2494    2494  2469.5  2469.5  2469.5  2469.5  2469.5  2469.5  2469.5  2469.5
  2469.5  2469.5  2469.5  2469.5  2469.5  2469.5  2469.5  2469.5  2469.5  2469.5
  2469.5  2469.5  2469.5  2469.5  2469.5  2469.5  2469.5  2469.5  2469.5  2469.5
Abutment Skew #Up #Dn= , 2 , 2
  4977.5    4985
    2494 2492.29
  4977.5    4985
    2494 2490.85
Abutment Skew #Up #Dn= , 2 , 2
    5015  5022.5
 2492.13    2494
    5015  5022.5
 2489.64    2494
BR Coef= 1 , 1 , 0 ,1.25, 0 ,,,0.8,0,2,0,
WSPro=,,,, 1 ,,,, 0 ,,,, 0 ,,,,-1 ,-1 ,-1 , 0 , 0 , 0 , 0 , 0
BC Design=,, 0 ,, 0 ,,,,,,
BC HTab HWMax=2543.7

Type RM Length L Ch R = 1 ,42018   ,532,532,532
BEGIN DESCRIPTION:
XS 128
END DESCRIPTION:
XS GIS Cut Line= 6
      1052588.31       863199.11      1052362.49        863337.3
      1052286.65       863386.17      1052205.75       863362.58
      1052118.12       863360.89      1052113.06        863485.6
#Sta/Elev= 30
  4691.4 2510.16  4706.7 2510.48  4749.2 2501.34  4767.4 2500.26  4799.9 2501.59
  4898.7  2499.1    4957 2496.23  4969.4 2494.78  4979.5  2491.7  4983.1 2490.55
  4992.5  2485.4  5007.5  2485.4  5008.9 2487.96  5020.7 2491.79  5032.1 2495.31
  5044.8 2497.31    5083 2497.59  5101.4 2501.18  5116.9 2502.69  5126.9 2505.54
  5145.4 2506.92  5188.7 2507.93  5218.3 2506.91  5240.4 2508.73    5247 2510.37
  5252.7 2509.63  5272.9 2509.87  5278.5 2511.44  5303.1 2527.06  5343.1 2540.16
#Mann= 3 ,-1 , 0
  4691.4     .07       0  4979.5    .045       0  5020.7     .07       0
#XS Ineff= 2 , 0
       0    4914    2510  5056.5       0    2510
Permanent Ineff=
       F       F
Bank Sta=4979.5,5020.7
Exp/Cntr=0.5,0.3

Type RM Length L Ch R = 1 ,41486   ,607,607,607
BEGIN DESCRIPTION:
XS 127
END DESCRIPTION:
XS GIS Cut Line= 5
      1052329.44        862697.2       1052171.1       862779.81
      1052050.63       862965.68      1051885.41       863082.72
      1051761.63       863123.49
#Sta/Elev= 30
  4674.3 2504.81  4713.6 2498.71  4762.8 2497.17  4776.9 2495.01  4794.8 2489.23
  4834.2 2479.02  4848.2 2483.88  4858.5 2484.34  4919.1 2482.37  4971.2 2482.54
  4975.4 2477.54  4982.9 2472.67  4993.1 2468.61  5008.4 2468.61  5011.1 2472.05
  5015.6 2473.05  5033.4  2475.3  5050.1 2475.37  5075.3 2479.36  5103.9  2481.2
  5152.1 2479.98    5156 2476.89  5156.9 2478.78  5162.5  2479.7  5185.4 2481.44
  5268.7 2483.92  5314.4 2494.51  5337.3 2505.88    5358 2513.69  5407.2 2539.18
#Mann= 3 ,-1 , 0
  4674.3     .07       0  4982.9     .05       0  5015.6     .07       0
Bank Sta=4982.9,5015.6
Exp/Cntr=0.3,0.1

Type RM Length L Ch R = 1 ,40879   ,610,610,610
BEGIN DESCRIPTION:
XS 126
END DESCRIPTION:
XS GIS Cut Line= 5
      1052226.18       862318.56      1052036.86       862366.75
      1051906.06       862383.96      1051816.56       862397.73
      1051730.51       862442.48
#Sta/Elev= 30
  4641.3 2511.94  4670.8 2507.99    4680 2505.97  4695.9 2504.51  4734.6 2502.77
  4740.7 2501.69    4755 2497.44    4781 2494.39  4794.2  2493.4    4821 2488.07
  4862.3 2484.81  4918.3 2478.33  4934.2 2474.98  4965.9 2459.31  4974.2 2456.39
  4985.1 2456.28  4986.9 2454.31  5011.9 2454.31  5013.3 2456.18  5018.9 2456.44
  5028.7 2459.35  5037.2 2461.22  5056.9 2466.37  5062.9 2468.44  5069.4  2469.8
  5076.1 2473.58  5103.2 2485.96  5117.8 2495.09  5140.7 2510.18  5156.1 2518.45
#Mann= 3 ,-1 , 0
  4641.3     .07       0  4965.9     .05       0  5028.7     .07       0
Bank Sta=4965.9,5028.7
Exp/Cntr=0.3,0.1

Type RM Length L Ch R = 1 ,40269   ,557,557,557
BEGIN DESCRIPTION:
XS 125
END DESCRIPTION:
XS GIS Cut Line= 4
      1052143.56       861802.24      1051902.62       861771.26
      1051785.58       861791.92      1051620.36       861877.97
#Sta/Elev= 30
  4704.7 2488.71  4750.2 2484.07    4766  2483.3    4773 2482.12  4813.5 2479.04
  4859.1 2478.21  4872.7 2476.84  4878.9 2476.89  4886.8 2473.14  4892.9 2471.27
  4896.5 2469.33  4900.5 2468.39  4904.8 2468.53  4931.5 2465.71  4943.1 2463.25
    4950 2460.78  4970.8 2450.31  4979.9 2446.45  4988.3 2442.43    5013 2442.43
  5017.9 2445.74  5021.9 2446.42  5080.4 2451.68  5090.1 2451.72  5126.2 2456.33
  5142.8 2463.84  5159.6 2469.59  5179.9 2478.43  5200.1 2484.53  5252.8 2502.11
#Mann= 3 ,-1 , 0
  4704.7     .07       0  4979.9     .05       0  5021.9     .09       0
Bank Sta=4979.9,5021.9
Exp/Cntr=0.3,0.1

Type RM Length L Ch R = 1 ,39712   ,551,551,551
BEGIN DESCRIPTION:
XS 124
END DESCRIPTION:
XS GIS Cut Line= 4
      1051868.19       861199.87      1051699.53       861241.18
       1051582.5       861306.58      1051437.93        861382.3
#Sta/Elev= 30
    4777 2499.63  4796.3 2492.93  4818.3 2484.39  4841.7 2472.85  4853.4 2467.93
  4860.2 2465.81  4875.6 2454.82  4888.8 2448.56  4897.8 2446.73  4906.7 2446.18
  4920.6 2446.42  4931.7 2442.64  4937.1 2440.35  4944.3 2439.48  4960.9  2440.4
  4972.9 2438.61  4984.4 2435.43    4988 2433.14  5011.4 2433.14  5014.5 2437.43
  5021.1 2438.59  5031.1 2440.13  5053.7 2441.74  5069.2 2442.43  5119.7  2443.4
  5157.1 2448.48  5184.1 2454.09  5222.2 2466.44  5241.5 2471.18  5247.9 2474.34
#Mann= 3 ,-1 , 0
    4777     .09       0  4972.9     .05       0  5021.1     .09       0
Bank Sta=4972.9,5021.1
Exp/Cntr=0.3,0.1

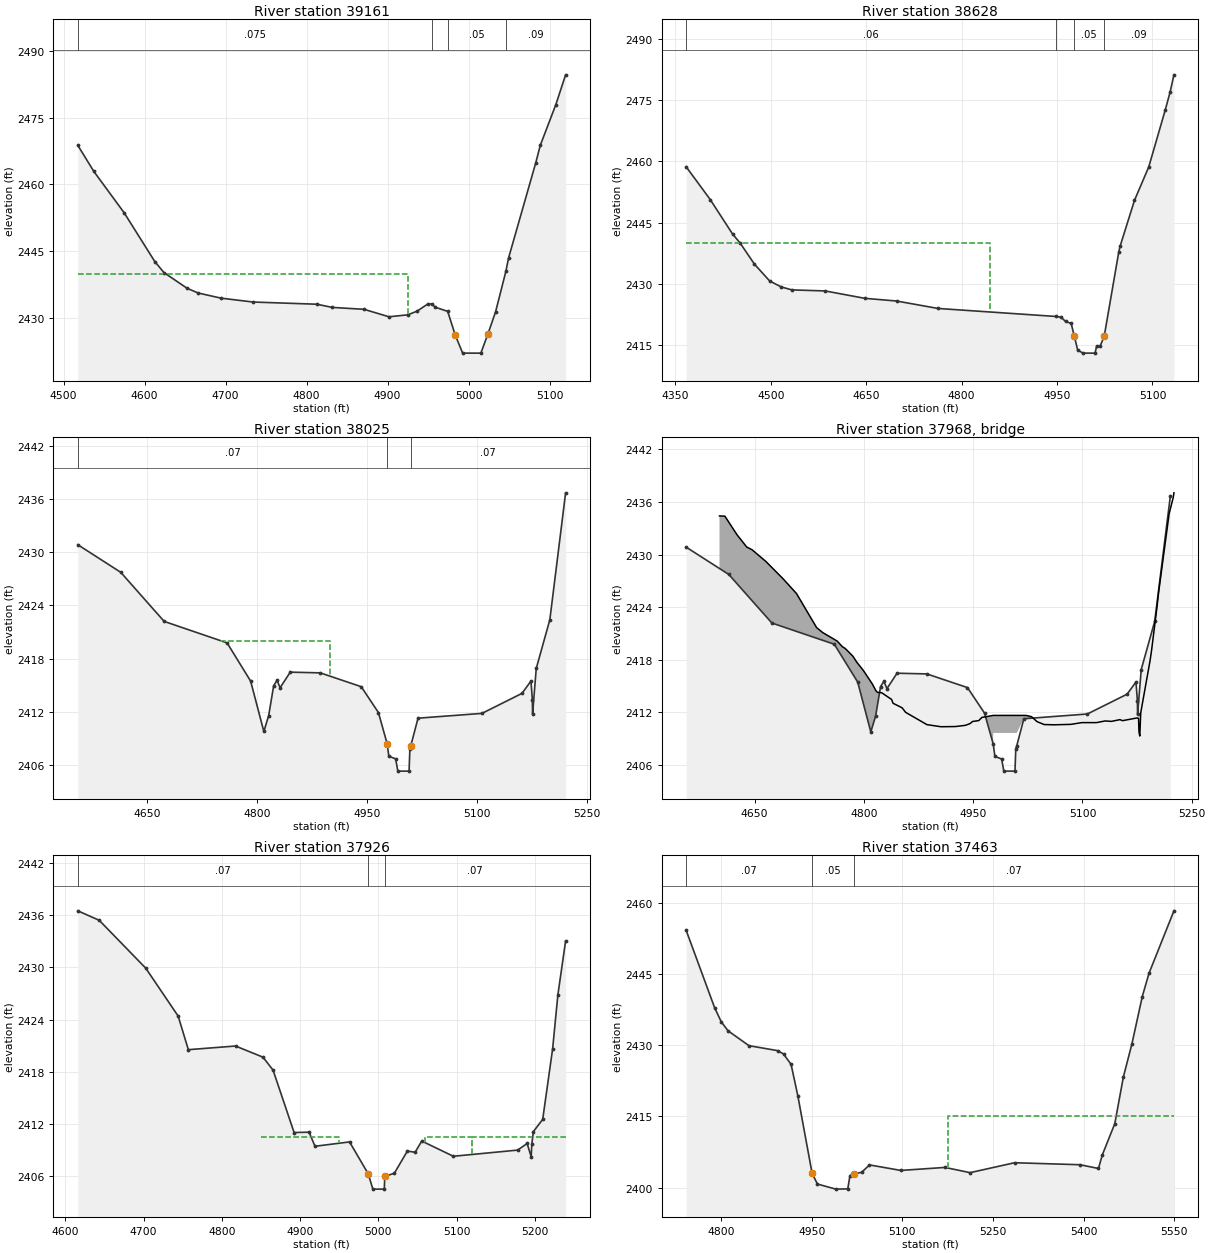
Type RM Length L Ch R = 1 ,39161   ,533,533,533
BEGIN DESCRIPTION:
XS 123
END DESCRIPTION:
XS GIS Cut Line= 4
      1051926.71       860855.66      1051799.35        860728.3
      1051551.52       860755.84      1051379.41       860742.07
#Sta/Elev= 30
  4517.6 2468.79  4537.4 2462.93  4574.8 2453.65  4612.6 2442.71  4623.9 2440.23
  4652.4 2436.71  4666.1 2435.64  4694.4 2434.48  4734.1 2433.61  4812.6 2433.12
  4831.8  2432.4  4870.8 2431.98  4901.7  2430.3    4925 2430.74  4936.4 2431.57
 4949.94 2433.21 4954.65 2433.15    4959 2432.43  4974.1 2431.52  4983.5 2426.19
  4992.6 2422.14  5015.1 2422.14 5023.89 2426.49 5033.32 2431.44    5046 2440.53
  5049.3 2443.51  5082.9  2464.9  5088.5 2468.82  5107.6 2477.91  5119.7 2484.62
#Mann= 4 ,-1 , 0
  4517.6    .075       0 4954.65     .09       0  4974.1     .05       0
    5046     .09       0
#XS Ineff= 2 , 0
       0  4925.1    2440               0
Permanent Ineff=
       F       F
Bank Sta=4983.5,5023.89
Exp/Cntr=0.3,0.1

Type RM Length L Ch R = 1 ,38628   ,603,603,603
BEGIN DESCRIPTION:
XS 122
END DESCRIPTION:
XS GIS Cut Line= 4
      1052122.91       860174.12      1051813.12       860167.23
       1051558.4       860215.42       1051362.2       860239.52
#Sta/Elev= 30
    4367  2458.7  4404.9 2450.67  4439.9 2442.27    4452 2440.02  4474.3  2434.9
  4498.3 2430.77  4516.4 2429.32  4533.2 2428.59  4585.7 2428.33  4647.7 2426.53
  4697.8 2425.87    4763 2424.05  4948.7 2422.09  4956.4 2421.91  4963.4 2420.87
  4972.2 2420.41  4977.3 2417.23  4982.4 2413.93  4990.6 2413.13  5009.8 2413.13
  5012.2 2414.81  5017.8 2414.86  5024.2 2417.26  5047.1 2437.87  5049.1 2439.23
  5071.8 2450.49  5094.2 2458.65  5120.2 2472.61  5127.7 2476.91  5133.8 2481.17
#Mann= 4 ,-1 , 0
    4367     .06       0  4948.7     .09       0  4977.3     .05       0
  5024.2     .09       0
#XS Ineff= 2 , 0
       0  4845.1    2440               0
Permanent Ineff=
       F       F
Bank Sta=4977.3,5024.2
Exp/Cntr=0.5,0.3

Type RM Length L Ch R = 1 ,38025   ,99,99,99
BEGIN DESCRIPTION:
XS 121
END DESCRIPTION:
XS GIS Cut Line= 5
       1051778.7       859644.03      1051598.39       859723.63
      1051407.18       859641.28      1051315.06       859639.89
      1051153.16       859681.76
#Sta/Elev= 30
    4556 2430.84  4614.5 2427.73  4673.7 2422.19  4759.4 2419.77  4791.5 2415.46
  4809.5 2409.78  4816.1 2411.58  4822.9 2414.94  4827.4 2415.54  4831.7 2414.72
  4845.5 2416.47  4886.4 2416.39  4942.2 2414.83  4965.6 2411.92  4977.6 2408.38
  4979.8 2406.99  4989.1 2406.69  4992.1 2405.31  5007.4 2405.31  5008.5 2407.81
  5009.8 2408.19  5019.6 2411.28  5106.7 2411.82  5161.3 2414.08  5173.5 2415.47
  5175.4 2413.32  5175.7 2411.78  5180.7 2416.89  5199.2 2422.38  5220.7 2436.69
#Mann= 3 ,-1 , 0
    4556     .07       0  4977.6     .05       0  5009.8     .07       0
#XS Ineff= 3 ,-1
    4750    4900    2420    4900    4925    2410  5074.5    5200    2410
Permanent Ineff=
       F       F       F
Bank Sta=4977.6,5009.8
Exp/Cntr=0.5,0.3

Type RM Length L Ch R = 3 ,37968   ,,,
BEGIN DESCRIPTION:
XS 120 TOR
Structure ID: XS 120
Approximate Survey Structure
END DESCRIPTION:
Bridge Culvert--1,0,-1,-1, 0
Deck Dist Width WeirC Skew NumUp NumDn MinLoCord MaxHiCord MaxSubmerge Is_Ogee
52,10,3,0, 60, 60, , , , 0, 1,1,,
  4601.8  4609.2  4625.7  4639.2  4646.4  4665.3  4689.1  4707.5  4735.1  4743.5
  4763.4  4770.6  4774.4  4784.9  4790.2  4799.2  4811.4  4816.6  4818.7  4824.5
    4838  4840.1  4852.4  4857.3  4886.5  4905.8  4925.5  4939.4  4945.7  4949.2
  4957.7    4962  4977.5  4977.5  5022.5  5022.5    5030  5037.7  5047.4  5061.1
  5084.1  5099.2  5119.3  5131.2  5139.8  5151.5    5155  5174.8    5177  5177.6
  5178.7    5180  5180.4  5192.8  5194.8  5202.3  5204.7    5219  5224.7  5225.6
  2434.4 2434.37 2432.27 2430.85 2430.55 2429.22 2427.23 2425.55 2421.67  2421.1
 2420.13 2419.48 2419.29 2418.41 2417.73 2416.79 2415.27 2414.46 2414.29 2414.24
 2413.48 2413.04 2412.53 2412.01 2410.61 2410.37 2410.39 2410.53 2410.73 2410.97
 2411.07 2411.43 2411.66 2411.66 2411.66 2411.66 2411.52 2410.95 2410.62 2410.59
 2410.64 2410.84 2410.84 2411.03 2410.98 2411.18 2411.06 2411.37 2411.33  2409.8
 2409.31  2411.9 2412.14 2417.89 2419.01 2424.01 2425.77 2434.65 2436.52 2437.03
  2382.5  2382.5  2382.5  2382.5  2382.5  2382.5  2382.5  2382.5  2382.5  2382.5
  2382.5  2382.5  2382.5  2382.5  2382.5  2382.5  2382.5  2382.5  2382.5  2382.5
  2382.5  2382.5  2382.5  2382.5  2382.5  2382.5  2382.5  2382.5  2382.5  2382.5
  2382.5  2382.5  2382.5 2409.66 2409.66  2382.5  2382.5  2382.5  2382.5  2382.5
  2382.5  2382.5  2382.5  2382.5  2382.5  2382.5  2382.5  2382.5  2382.5  2382.5
  2382.5  2382.5  2382.5  2382.5  2382.5  2382.5  2382.5  2382.5  2382.5  2382.5
  4601.8  4609.2  4625.7  4639.2  4646.4  4665.3  4689.1  4707.5  4735.1  4743.5
  4763.4  4770.6  4774.4  4784.9  4790.2  4799.2  4811.4  4816.6  4818.7  4824.5
    4838  4840.1  4852.4  4857.3  4886.5  4905.8  4925.5  4939.4  4945.7  4949.2
  4957.7    4962  4977.5  4977.5  5022.5  5022.5    5030  5037.7  5047.4  5061.1
  5084.1  5099.2  5119.3  5131.2  5139.8  5151.5    5155  5174.8    5177  5177.6
  5178.7    5180  5180.4  5192.8  5194.8  5202.3  5204.7    5219  5224.7  5225.6
  2434.4 2434.37 2432.27 2430.85 2430.55 2429.22 2427.23 2425.55 2421.67  2421.1
 2420.13 2419.48 2419.29 2418.41 2417.73 2416.79 2415.27 2414.46 2414.29 2414.24
 2413.48 2413.04 2412.53 2412.01 2410.61 2410.37 2410.39 2410.53 2410.73 2410.97
 2411.07 2411.43 2411.66 2411.66 2411.66 2411.66 2411.52 2410.95 2410.62 2410.59
 2410.64 2410.84 2410.84 2411.03 2410.98 2411.18 2411.06 2411.37 2411.33  2409.8
 2409.31  2411.9 2412.14 2417.89 2419.01 2424.01 2425.77 2434.65 2436.52 2437.03
  2382.5  2382.5  2382.5  2382.5  2382.5  2382.5  2382.5  2382.5  2382.5  2382.5
  2382.5  2382.5  2382.5  2382.5  2382.5  2382.5  2382.5  2382.5  2382.5  2382.5
  2382.5  2382.5  2382.5  2382.5  2382.5  2382.5  2382.5  2382.5  2382.5  2382.5
  2382.5  2382.5  2382.5 2409.66 2409.66  2382.5  2382.5  2382.5  2382.5  2382.5
  2382.5  2382.5  2382.5  2382.5  2382.5  2382.5  2382.5  2382.5  2382.5  2382.5
  2382.5  2382.5  2382.5  2382.5  2382.5  2382.5  2382.5  2382.5  2382.5  2382.5
Abutment Skew #Up #Dn= , 2 , 2
  4977.5    4985
 2409.66 2406.82
  4977.5    4985
 2409.66 2406.54
Abutment Skew #Up #Dn= , 2 , 2
    5015  5022.5
 2408.03 2409.66
  5015.3  5022.5
 2406.32 2409.66
BR Coef= 1 , 1 , 0 ,1.25, 0 ,,,0.8,0,2,0,
WSPro=,,,, 1 ,,,, 0 ,,,, 0 ,,,,-1 ,-1 ,-1 , 0 , 0 , 0 , 0 , 0
BC Design=,, 0 ,, 0 ,,,,,,
BC HTab HWMax=2436.69

Type RM Length L Ch R = 1 ,37926   ,463,463,463
BEGIN DESCRIPTION:
XS 119
END DESCRIPTION:
XS GIS Cut Line= 5
      1051719.82       859525.44      1051573.27         859605.
      1051447.65       859543.58      1051331.81       859540.79
       1051137.8       859593.83
#Sta/Elev= 30
  4615.8 2436.51  4643.2 2435.42  4702.7 2429.91  4744.1  2424.4  4757.1 2420.54
  4817.4 2420.96  4852.5 2419.68  4865.4 2418.19  4892.3 2411.01  4911.5 2411.05
    4919 2409.43  4963.2 2409.93    4987 2406.27    4993  2404.5  5007.6  2404.5
  5008.2 2405.96  5020.5 2406.33  5037.1 2408.88    5047 2408.74  5055.5 2410.03
  5095.9 2408.28  5178.1 2408.99  5190.2 2409.75  5195.4 2408.22  5196.2 2409.71
  5198.2 2411.12  5210.1 2412.52  5222.8 2420.64  5229.5 2426.84  5239.4 2433.05
#Mann= 3 ,-1 , 0
  4615.8     .07       0    4987     .05       0  5008.2     .07       0
#XS Ineff= 3 ,-1
    4850    4950  2410.5    5060    5120  2410.5    5120    5250  2410.5
Permanent Ineff=
       F       F       F
Bank Sta=4987,5008.2
Exp/Cntr=0.5,0.3

Type RM Length L Ch R = 1 ,37463   ,484,484,484
BEGIN DESCRIPTION:
XS 118
END DESCRIPTION:
XS GIS Cut Line= 5
       1051548.2       858934.55      1051379.41       859031.33
      1051289.92       859155.25      1051110.93       859348.01
       1050945.7       859454.71
#Sta/Elev= 30
  4742.1 2454.21  4789.2  2437.9  4800.2 2434.92  4811.5 2433.02  4846.1 2429.89
  4893.3 2428.85  4903.3 2428.14  4915.8 2425.94    4927 2419.29  4950.6 2402.97
  4959.4 2400.74  4989.8 2399.67  5009.6 2399.72  5013.2 2402.53  5019.4 2402.86
  5032.6 2403.22  5045.5 2404.77  5097.4 2403.61  5170.4 2404.24    5212 2403.14
  5285.6 2405.23  5393.9 2404.81  5424.4 2404.02  5430.8 2406.89  5451.4 2413.45
  5465.6 2423.28  5479.9 2430.34  5496.9 2440.23    5508 2445.13  5549.3  2458.3
#Mann= 3 ,-1 , 0
  4742.1     .07       0  4950.6     .05       0  5019.4     .07       0
#XS Ineff= 2 , 0
       0                    5175       0    2415
Permanent Ineff=
       F       F
Bank Sta=4950.6,5019.4
Exp/Cntr=0.3,0.1

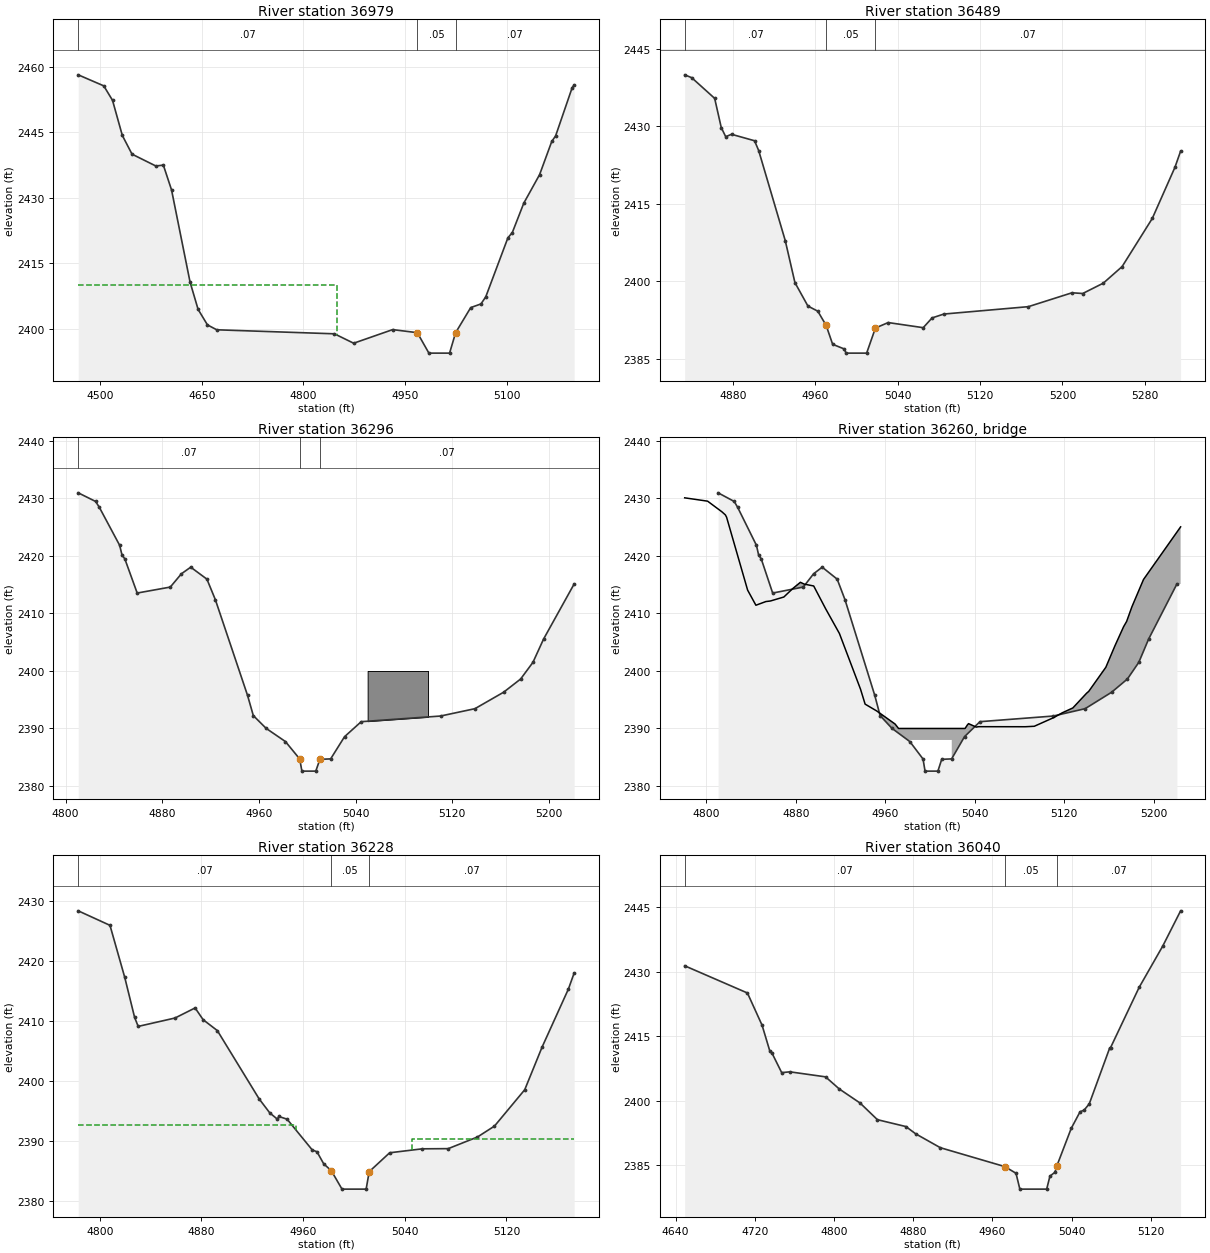
Type RM Length L Ch R = 1 ,36979   ,490,490,490
BEGIN DESCRIPTION:
XS 117
END DESCRIPTION:
XS GIS Cut Line= 5
      1051324.34       858707.77      1051179.77       858866.11
      1050942.26       859034.77      1050866.54        859110.5
      1050756.39       859155.25
#Sta/Elev= 30
  4467.7  2458.2  4505.4 2455.67  4518.3 2452.36  4532.8 2444.29  4547.1 2440.01
  4582.2  2437.3  4593.3  2437.5  4605.4 2431.81  4632.7 2410.69  4644.6 2404.41
  4658.4 2400.86  4672.1 2399.74  4845.7 2398.82  4874.1 2396.66  4931.6 2399.78
    4968 2399.08  4985.1 2394.39  5015.6 2394.39  5024.5 2399.07  5046.8 2404.83
  5061.9 2405.67    5069  2407.3  5101.7 2420.85  5108.1 2422.01  5125.1 2428.78
  5148.4 2435.31  5166.4 2442.94    5172 2444.18  5196.5 2455.27  5199.4 2455.87
#Mann= 3 ,-1 , 0
  4467.7     .07       0    4968     .05       0  5024.5     .07       0
#XS Ineff= 2 , 0
       0    4850    2410               0
Permanent Ineff=
       F       F
Bank Sta=4968,5024.5
Exp/Cntr=0.3,0.1

Type RM Length L Ch R = 1 ,36489   ,193,193,193
BEGIN DESCRIPTION:
XS 116
END DESCRIPTION:
XS GIS Cut Line= 4
      1051043.26        858487.7      1050956.71       858564.77
      1050865.41       858606.27      1050630.65       858729.58
#Sta/Elev= 30
  4833.4    2440  4840.2 2439.45  4862.5 2435.44  4868.9 2429.78  4873.2 2428.02
  4878.9 2428.48  4901.2 2427.23  4905.2 2425.34    4931 2407.89  4940.4 2399.75
    4953 2395.21  4962.6 2394.21  4970.7 2391.46    4977  2387.8  4988.2  2386.9
    4990 2386.09    5010 2386.09  5018.5 2390.95  5030.9 2392.01  5064.9 2391.02
  5073.5 2392.91  5084.9 2393.66  5166.9 2395.09  5209.3 2397.78  5219.7 2397.64
  5239.7 2399.65  5257.9 2402.85  5287.2 2412.18  5309.2 2422.09  5314.7 2425.22
#Mann= 3 ,-1 , 0
  4833.4     .07       0  4970.7     .05       0  5018.5     .07       0
Bank Sta=4970.7,5018.5
Exp/Cntr=0.5,0.3

Type RM Length L Ch R = 1 ,36296   ,68,68,68
BEGIN DESCRIPTION:
XS 115
END DESCRIPTION:
XS GIS Cut Line= 5
      1050891.73       858374.02      1050809.78       858417.28
      1050768.04       858457.49      1050735.41       858544.76
      1050585.17       858616.85
#Sta/Elev= 30
  4810.5 2430.98  4824.9 2429.48  4827.9 2428.49  4844.8 2421.85  4846.7  2420.2
  4849.1 2419.48  4859.3 2413.55  4886.7 2414.59  4895.9  2416.9  4903.6 2418.05
    4917 2415.97    4924 2412.39  4950.6 2395.77  4955.4 2392.24    4966 2390.02
    4982 2387.72  4993.8 2384.69  4995.6 2382.58  5007.1 2382.58  5010.5 2384.63
  5019.4 2384.71  5030.9 2388.57  5044.7 2391.18  5110.3 2392.16  5138.8 2393.44
  5162.5  2396.3  5176.6  2398.6  5186.8  2401.5  5195.6 2405.55  5220.9 2415.13
#Mann= 3 ,-1 , 0
  4810.5     .07       0  4993.8     .05       0  5010.5     .07       0
#XS Ineff= 2 , 0
       0  4950.5 2393.26  5049.5       0 2390.31
Permanent Ineff=
       F       F
#Block Obstruct= 1 ,-1
    5050    5100    2400
Bank Sta=4993.8,5010.5
Exp/Cntr=0.5,0.3

Type RM Length L Ch R = 3 ,36260   ,,,
BEGIN DESCRIPTION:
XS 114
Structure ID: XS 114
Approximate Survey Structure
END DESCRIPTION:
Bridge Culvert--1,0,-1,-1, 0
Deck Dist Width WeirC Skew NumUp NumDn MinLoCord MaxHiCord MaxSubmerge Is_Ogee
30,12,3,0, 44, 44, , , , 0, 1,1,,
  4780.6  4801.1  4813.9    4817  4818.1  4836.9  4844.3  4853.2  4857.3  4869.3
  4877.2  4884.1  4887.6    4896  4906.7    4919  4937.9    4942  4952.4  4968.8
  4971.9  4980.5  4980.5  5019.5  5019.5  5031.4  5033.5  5034.5  5041.4  5043.5
  5085.3  5093.3  5110.7  5118.4  5127.8  5140.1    5142  5157.3  5165.4  5173.2
  5175.9  5180.6    5191  5224.2
 2430.11 2429.53 2427.68 2427.14 2426.73 2414.06 2411.43 2412.07 2412.17 2412.86
 2414.32 2415.42  2415.1 2414.78 2410.81 2406.52 2396.82 2394.23 2393.04 2390.77
    2390    2390    2390    2390    2390    2390 2390.62 2390.84 2390.24 2390.31
  2390.3 2390.38 2391.89 2392.73 2393.57 2396.13 2396.45 2400.64 2404.36  2407.7
 2408.61 2411.15 2415.91 2425.06
    2360    2360    2360    2360    2360    2360    2360    2360    2360    2360
    2360    2360    2360    2360    2360    2360    2360    2360    2360    2360
    2360    2360    2388    2388    2360    2360    2360    2360    2360    2360
    2360    2360    2360    2360    2360    2360    2360    2360    2360    2360
    2360    2360    2360    2360
  4780.6  4801.1  4813.9    4817  4818.1  4836.9  4844.3  4853.2  4857.3  4869.3
  4877.2  4884.1  4887.6    4896  4906.7    4919  4937.9    4942  4952.4  4968.8
  4971.9  4980.5  4980.5  5019.5  5019.5  5031.4  5033.5  5034.5  5041.4  5043.5
  5085.3  5093.3  5110.7  5118.4  5127.8  5140.1    5142  5157.3  5165.4  5173.2
  5175.9  5180.6    5191  5224.2
 2430.11 2429.53 2427.68 2427.14 2426.73 2414.06 2411.43 2412.07 2412.17 2412.86
 2414.32 2415.42  2415.1 2414.78 2410.81 2406.52 2396.82 2394.23 2393.04 2390.77
    2390    2390    2390    2390    2390    2390 2390.62 2390.84 2390.24 2390.31
  2390.3 2390.38 2391.89 2392.73 2393.57 2396.13 2396.45 2400.64 2404.36  2407.7
 2408.61 2411.15 2415.91 2425.06
    2360    2360    2360    2360    2360    2360    2360    2360    2360    2360
    2360    2360    2360    2360    2360    2360    2360    2360    2360    2360
    2360    2360    2388    2388    2360    2360    2360    2360    2360    2360
    2360    2360    2360    2360    2360    2360    2360    2360    2360    2360
    2360    2360    2360    2360
Abutment Skew #Up #Dn= , 2 , 2
  4980.5    4985
    2388 2385.58
  4980.5    4985
    2388 2383.88
Abutment Skew #Up #Dn= , 2 , 2
    5015  5019.5
 2384.67    2388
    5015  5019.5
 2385.57    2388
BR Coef= 1 , 1 , 0 ,1.25, 0 ,,,0.8,0,2,0,
WSPro=,,,, 1 ,,,, 0 ,,,, 0 ,,,,-1 ,-1 ,-1 , 0 , 0 , 0 , 0 , 0
BC Design=,, 0 ,, 0 ,,,,,,
BC HTab HWMax=2430.98

Type RM Length L Ch R = 1 ,36228   ,188,188,188
BEGIN DESCRIPTION:
XS 113
END DESCRIPTION:
XS GIS Cut Line= 5
      1050841.65       858327.73      1050767.28       858374.78
      1050720.24       858418.79      1050673.19       858506.06
      1050548.74       858567.52
#Sta/Elev= 30
    4783  2428.4    4808 2425.98  4819.6 2417.32  4827.4 2410.62  4830.2 2409.13
  4859.2 2410.53    4875 2412.21  4881.3 2410.25  4892.5 2408.43  4925.4 2397.04
  4933.8  2394.7  4939.7 2393.67  4940.9 2394.11  4947.4 2393.66  4967.2 2388.53
  4970.9 2388.23  4976.2 2386.22  4982.2 2385.07  4990.6    2382  5009.6    2382
    5012 2384.91  5028.1 2388.06  5053.8 2388.72  5074.2 2388.75  5097.2 2390.69
  5110.6 2392.51  5134.4 2398.57  5148.1  2405.7  5168.8 2415.37  5173.3 2418.03
#Mann= 3 ,-1 , 0
    4783     .07       0  4982.2     .05       0    5012     .07       0
#XS Ineff= 2 , 0
       0  4954.5 2392.75  5045.5       0 2390.31
Permanent Ineff=
       F       F
Bank Sta=4982.2,5012
Exp/Cntr=0.5,0.3

Type RM Length L Ch R = 1 ,36040   ,100,100,100
BEGIN DESCRIPTION:
XS 112
END DESCRIPTION:
XS GIS Cut Line= 5
        1050861.       858300.73      1050693.71       858336.44
      1050580.92       858370.28      1050474.14       858424.86
      1050442.13       858511.42
#Sta/Elev= 30
  4649.1 2431.39  4712.5 2425.06  4727.3 2417.56  4735.2 2411.49  4737.2 2411.13
  4747.1 2406.54  4755.3 2406.73  4791.4 2405.56  4805.3 2402.74  4826.3 2399.47
  4843.8  2395.6  4872.6    2394  4882.4 2392.32  4907.4 2389.08  4972.5 2384.69
  4983.8 2383.14  4987.7 2379.45  5014.8 2379.45  5018.1 2382.48  5023.2 2383.38
    5025 2384.81  5039.6 2393.58  5048.5 2397.43  5052.6 2397.83  5057.8 2399.27
  5078.3 2412.18  5079.3 2412.34  5108.2 2426.37  5132.1    2436  5150.1 2444.17
#Mann= 3 ,-1 , 0
  4649.1     .07       0  4972.5     .05       0    5025     .07       0
Bank Sta=4972.5,5025
Exp/Cntr=0.5,0.3