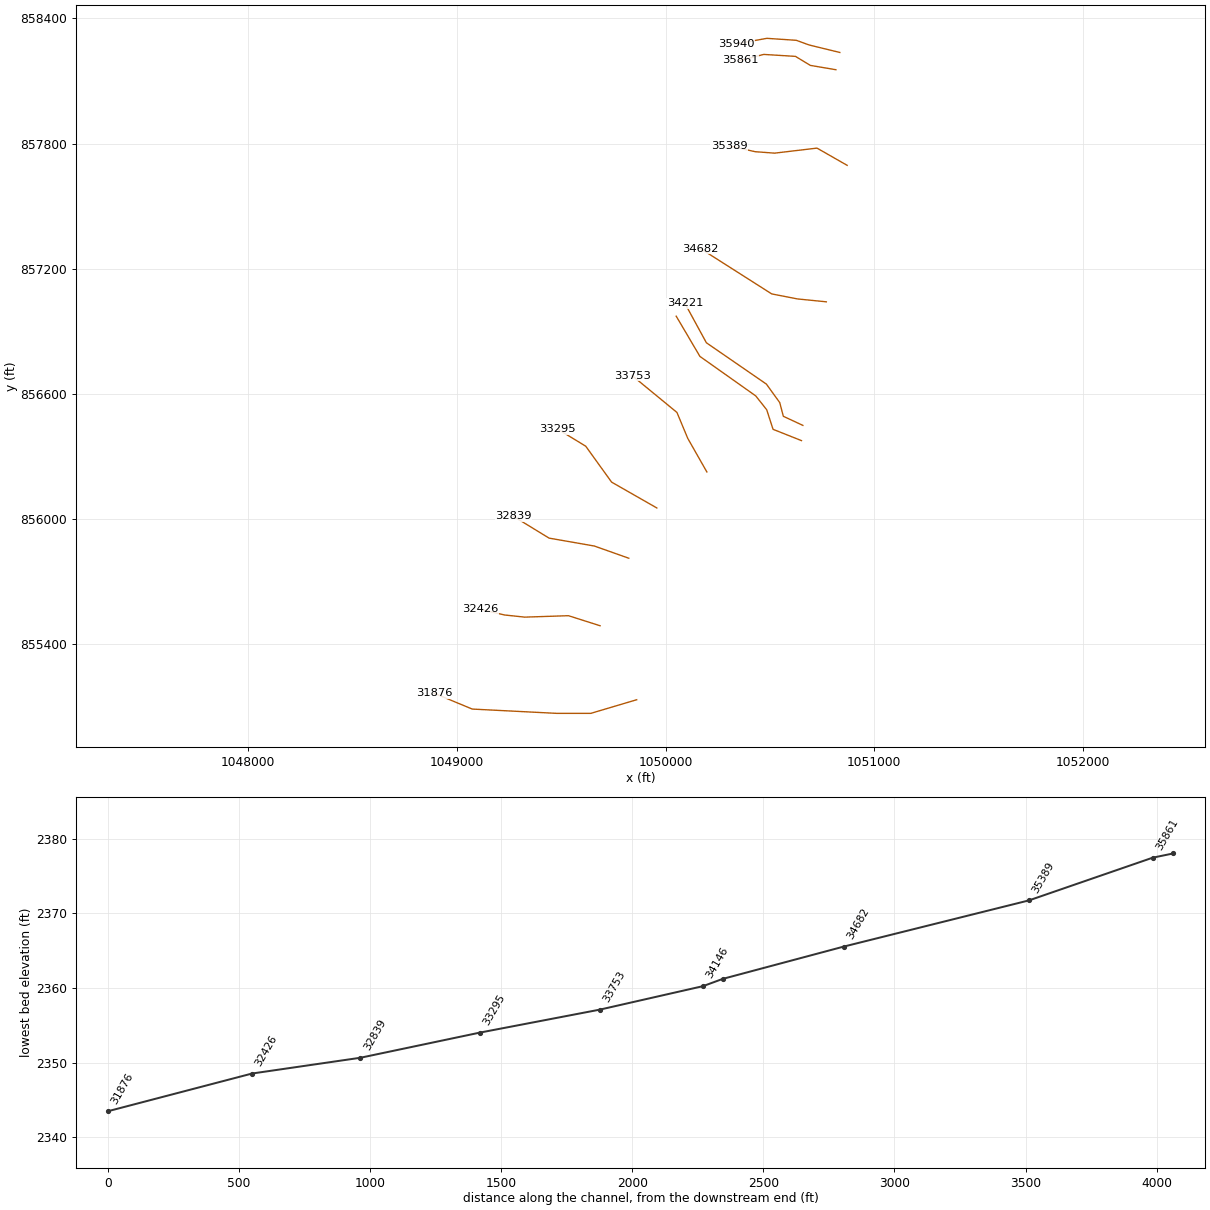
HEC-RAS study lds_big_rock_crk.prj: Big Rock Creek Limited Detail Study

--- lds_big_rock_crk.g01 (geometry) --- (continued)

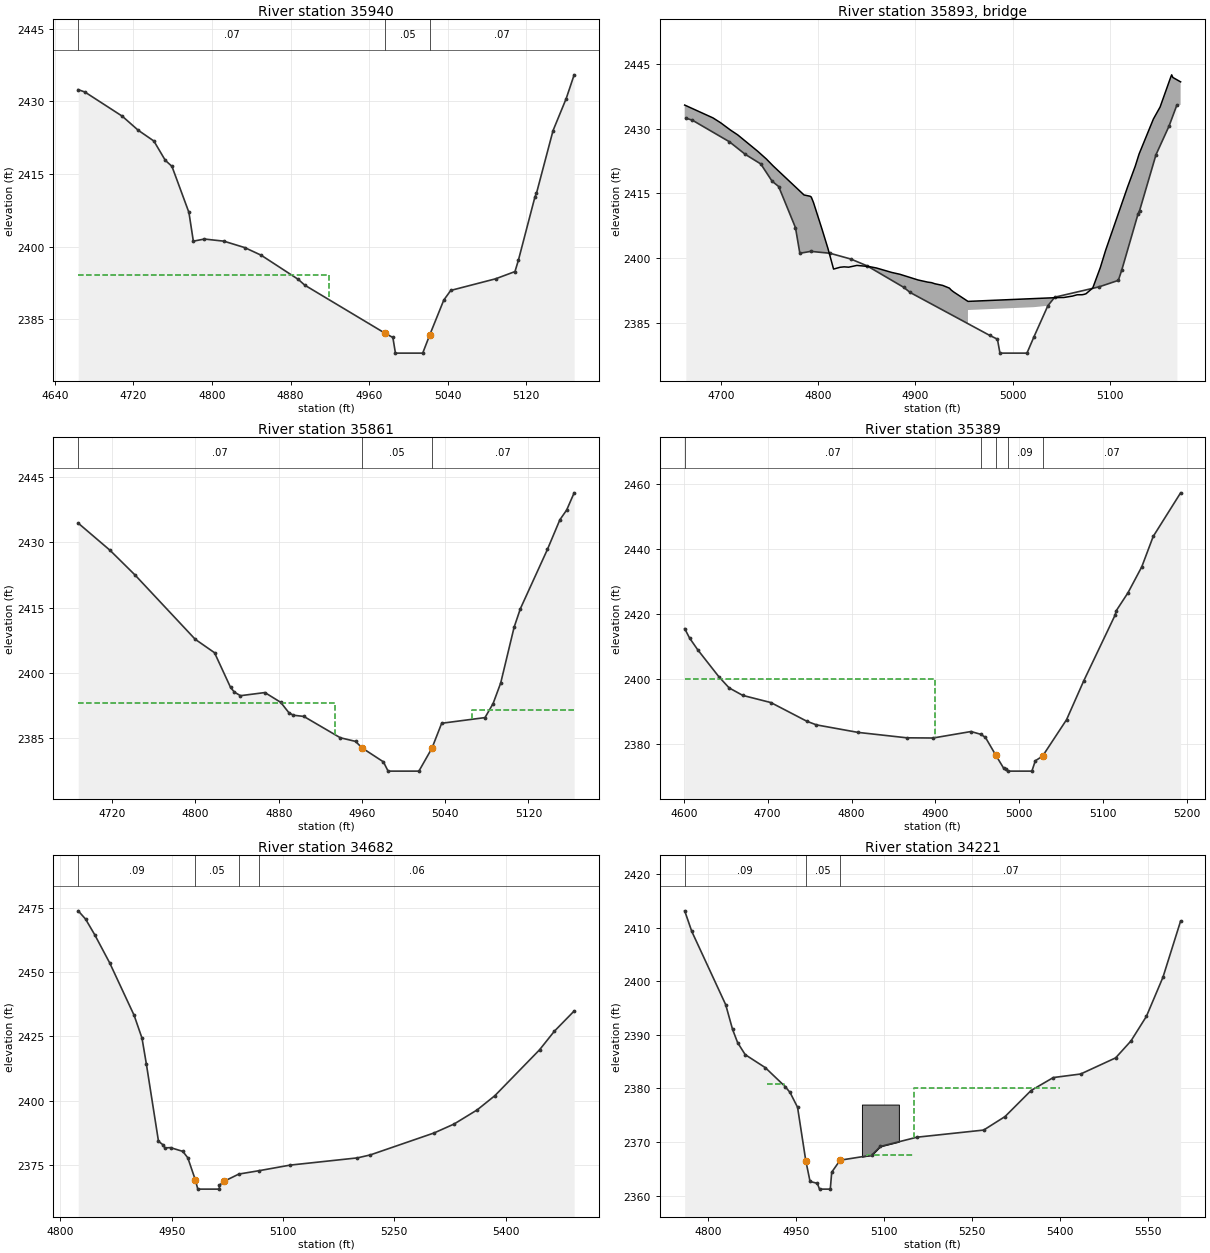
Type RM Length L Ch R = 1 ,35940   ,79,79,79
BEGIN DESCRIPTION:
XS 111
END DESCRIPTION:
XS GIS Cut Line= 5
      1050834.69       858236.81      1050688.07       858272.53
      1050626.03       858295.09      1050485.05       858304.49
      1050340.31       858278.17
#Sta/Elev= 30
  4663.7 2432.43  4670.5 2431.94  4708.5 2426.96  4724.8 2424.05  4740.8 2421.82
  4752.4 2417.84  4759.2 2416.59  4776.5 2407.07    4781 2401.14  4792.3 2401.58
  4812.1 2401.14  4833.4 2399.81  4850.1 2398.24  4887.9 2393.25  4894.5 2392.06
  4976.3 2382.13  4984.3 2381.25  4986.9 2378.02  5014.7 2378.02  5021.9  2381.8
  5036.2 2388.99  5043.3 2390.97    5089 2393.37  5108.7 2394.86  5112.2 2397.21
  5129.1 2410.32  5130.6 2411.02  5147.5 2423.98  5160.9 2430.59    5169 2435.49
#Mann= 3 ,-1 , 0
  4663.7     .07       0  4976.3     .05       0  5021.9     .07       0
#XS Ineff= 2 , 0
       0    4919 2394.15    5081       0 2392.84
Permanent Ineff=
       F       F
Bank Sta=4976.3,5021.9
Exp/Cntr=0.5,0.3

Type RM Length L Ch R = 3 ,35893   ,,,
BEGIN DESCRIPTION:
XS 110 TOR
Structure ID: XS 110
Approximate Survey Structure
END DESCRIPTION:
Bridge Culvert--1,0,-1,-1, 0
Deck Dist Width WeirC Skew NumUp NumDn MinLoCord MaxHiCord MaxSubmerge Is_Ogee
35,24,3,0, 53, 53, , , , 0, 1,1,,
  4662.5  4691.6  4699.5  4709.8  4717.1  4737.6  4746.6  4753.5  4785.3  4791.5
  4792.8  4795.1  4803.8    4810  4815.7  4822.4  4826.6  4831.2  4839.7  4852.1
  4859.7  4875.6  4883.9  4902.8  4912.6  4916.5    4920    4928  4934.9  4936.8
  4939.3    4954    4954    5046    5046  5052.5  5061.6  5066.3  5071.5  5073.3
  5075.4  5082.4  5090.2  5095.6  5118.2  5126.1  5130.1  5144.8  5151.7  5162.7
  5163.6  5164.8  5172.8
 2435.46 2432.49 2431.36 2429.64 2428.55 2424.77 2422.96 2421.37 2414.64 2414.35
 2414.15 2412.85 2406.73 2402.19 2397.48  2397.9    2398 2397.92 2398.33 2398.07
 2397.74  2396.7 2396.28 2394.95 2394.46 2394.34 2394.08  2393.7 2393.07 2392.61
 2392.18    2390    2390 2390.88 2390.88  2390.9 2391.23 2391.53 2391.54 2391.62
 2391.76 2393.11 2397.85 2401.81 2416.48  2421.3 2424.15 2432.24 2435.02 2441.97
 2442.46 2441.85 2440.83
    2356    2356    2356    2356    2356    2356    2356    2356    2356    2356
    2356    2356    2356    2356    2356    2356    2356    2356    2356    2356
    2356    2356    2356    2356    2356    2356    2356    2356    2356    2356
    2356    2356    2388  2388.9    2356    2356    2356    2356    2356    2356
    2356    2356    2356    2356    2356    2356    2356    2356    2356    2356
    2356    2356    2356
  4662.5  4691.6  4699.5  4709.8  4717.1  4737.6  4746.6  4753.5  4785.3  4791.5
  4792.8  4795.1  4803.8    4810  4815.7  4822.4  4826.6  4831.2  4839.7  4852.1
  4859.7  4875.6  4883.9  4902.8  4912.6  4916.5    4920    4928  4934.9  4936.8
  4939.3    4954    4954    5046    5046  5052.5  5061.6  5066.3  5071.5  5073.3
  5075.4  5082.4  5090.2  5095.6  5118.2  5126.1  5130.1  5144.8  5151.7  5162.7
  5163.6  5164.8  5172.8
 2435.46 2432.49 2431.36 2429.64 2428.55 2424.77 2422.96 2421.37 2414.64 2414.35
 2414.15 2412.85 2406.73 2402.19 2397.48  2397.9    2398 2397.92 2398.33 2398.07
 2397.74  2396.7 2396.28 2394.95 2394.46 2394.34 2394.08  2393.7 2393.07 2392.61
 2392.18    2390    2390 2390.88 2390.88  2390.9 2391.23 2391.53 2391.54 2391.62
 2391.76 2393.11 2397.85 2401.81 2416.48  2421.3 2424.15 2432.24 2435.02 2441.97
 2442.46 2441.85 2440.83
    2356    2356    2356    2356    2356    2356    2356    2356    2356    2356
    2356    2356    2356    2356    2356    2356    2356    2356    2356    2356
    2356    2356    2356    2356    2356    2356    2356    2356    2356    2356
    2356    2356    2388  2388.9    2356    2356    2356    2356    2356    2356
    2356    2356    2356    2356    2356    2356    2356    2356    2356    2356
    2356    2356    2356
Abutment Skew #Up #Dn= , 2 , 2
    4954    4975
    2388 2382.35
    4954    4975
    2388 2379.02
Abutment Skew #Up #Dn= , 2 , 2
    5025    5046
 2383.36    2388
    5025    5046
 2380.97    2388
BR Coef= 1 , 1 , 0 ,1.25, 0 ,,,0.8,0,2,0,
WSPro=,,,, 1 ,,,, 0 ,,,, 0 ,,,,-1 ,-1 ,-1 , 0 , 0 , 0 , 0 , 0
BC Design=,, 0 ,, 0 ,,,,,,
BC HTab HWMax=2435.49

Type RM Length L Ch R = 1 ,35861   ,472,472,472
BEGIN DESCRIPTION:
XS 109
END DESCRIPTION:
XS GIS Cut Line= 5
      1050815.89       858154.11      1050693.71       858174.78
      1050622.27       858218.02      1050470.01       858227.42
       1050357.1       858198.34
#Sta/Elev= 30
  4687.3 2434.39  4717.8 2428.17    4742 2422.46  4799.7 2407.73  4818.3 2404.64
  4833.7 2396.67  4837.4 2395.59  4843.2 2394.77  4866.7 2395.49  4881.9 2393.25
  4889.7 2390.88    4894 2390.29  4904.1 2390.01  4939.2 2385.11  4953.8 2384.28
  4960.2 2382.76  4980.6 2379.58  4985.1 2377.45  5014.7 2377.45  5027.2  2382.7
  5036.6 2388.44  5078.2 2389.74    5086 2392.96  5093.3 2397.68  5106.2 2410.49
  5112.2 2414.74  5138.2 2428.35  5150.2 2435.17  5156.7  2437.4  5163.9 2441.35
#Mann= 3 ,-1 , 0
  4687.3     .07       0  4960.2     .05       0  5027.2     .07       0
#XS Ineff= 2 , 0
       0    4934 2393.15    5066       0 2391.51
Permanent Ineff=
       F       F
Bank Sta=4960.2,5027.2
Exp/Cntr=0.5,0.3

Type RM Length L Ch R = 1 ,35389   ,707,707,707
BEGIN DESCRIPTION:
XS 108
END DESCRIPTION:
XS GIS Cut Line= 5
      1050869.98       857695.79      1050725.41        857778.4
      1050522.32        857754.3      1050429.39       857761.19
      1050305.47       857788.72
#Sta/Elev= 30
  4601.1 2415.53  4606.9 2412.66  4616.5 2409.08  4641.8 2400.76  4654.1 2397.31
  4670.4    2395  4703.9  2392.8  4746.8 2387.05  4758.1 2385.95  4807.6 2383.64
  4865.9 2381.97  4897.2 2381.91  4942.4  2383.9  4953.9 2383.06  4959.6 2382.11
  4972.1 2376.57  4981.2 2372.69  4983.8 2372.53  4986.1 2371.73    5015 2371.73
  5019.1 2374.91  5027.7 2376.33  5056.3 2387.53  5076.8 2399.47  5114.1 2419.64
  5115.7 2421.09  5129.5 2426.53    5146 2434.53  5159.6 2443.86  5192.3 2457.27
#Mann= 5 ,-1 , 0
  4601.1     .07       0  4953.9     .09       0  4972.1     .05       0
  4986.1     .09       0  5027.7     .07       0
#XS Ineff= 2 , 0
       0    4900    2400               0
Permanent Ineff=
       F       F
Bank Sta=4972.1,5027.7
Exp/Cntr=0.3,0.1

Type RM Length L Ch R = 1 ,34682   ,461,461,461
BEGIN DESCRIPTION:
XS 107
END DESCRIPTION:
XS GIS Cut Line= 4
      1050770.16       857041.78      1050632.47       857055.55
      1050508.55       857079.64      1050167.78        857296.5
#Sta/Elev= 30
    4824 2473.84  4833.9 2470.63  4846.2 2464.56  4866.4 2453.59  4899.4 2433.15
    4910 2424.27  4915.9 2414.17  4932.2 2384.18  4938.8 2382.66  4940.7 2381.59
  4948.5 2381.68    4965 2380.23  4971.7 2377.74 4981.91  2369.1  4985.2 2365.54
  5014.2 2365.54  5014.4  2367.1 5021.15 2368.66  5040.5  2371.4  5067.1 2372.68
  5109.5 2374.88  5200.4  2377.7  5217.8 2378.86  5303.8 2387.41  5330.6 2390.87
  5361.8 2396.38  5385.6  2401.9  5445.9 2419.77  5465.8 2426.98  5492.5 2434.86
#Mann= 4 ,-1 , 0
    4824     .09       0 4981.91     .05       0  5040.5     .09       0
  5067.1     .06       0
Bank Sta=4981.91,5021.15
Exp/Cntr=0.5,0.3

Type RM Length L Ch R = 1 ,34221   ,75,75,75
BEGIN DESCRIPTION:
XS 106
END DESCRIPTION:
XS GIS Cut Line= 6
      1050657.69       856449.63      1050564.09       856493.15
      1050546.85       856558.83      1050482.81        856647.5
      1050195.32       856845.58      1050092.06        857034.9
#Sta/Elev= 30
  4759.9 2413.15    4772 2409.31  4829.8 2395.64  4841.5 2391.03  4850.2 2388.54
  4863.1 2386.31  4897.3 2383.89    4931 2380.37  4939.5 2379.26  4952.3 2376.49
  4966.3 2366.54  4973.6 2362.65    4986  2362.3  4989.7 2361.22  5008.1 2361.22
  5010.5 2364.38  5024.9 2366.62  5078.7 2367.55  5093.4 2369.18  5155.8 2370.91
  5269.5 2372.24  5305.9 2374.76  5350.3 2379.62  5388.2 2382.04  5434.8  2382.7
  5494.4 2385.71  5520.5 2388.86  5546.9 2393.46  5575.1 2400.76  5605.2 2411.25
#Mann= 3 ,-1 , 0
  4759.9     .09       0  4966.3     .05       0  5024.9     .07       0
#XS Ineff= 3 ,-1
    4900  4929.5 2380.92  5070.5    5150 2367.68    5150    5400    2380
Permanent Ineff=
       F       F       F
#Block Obstruct= 1 ,-1
    5062    5125    2377
Bank Sta=4966.3,5024.9
Exp/Cntr=0.5,0.3

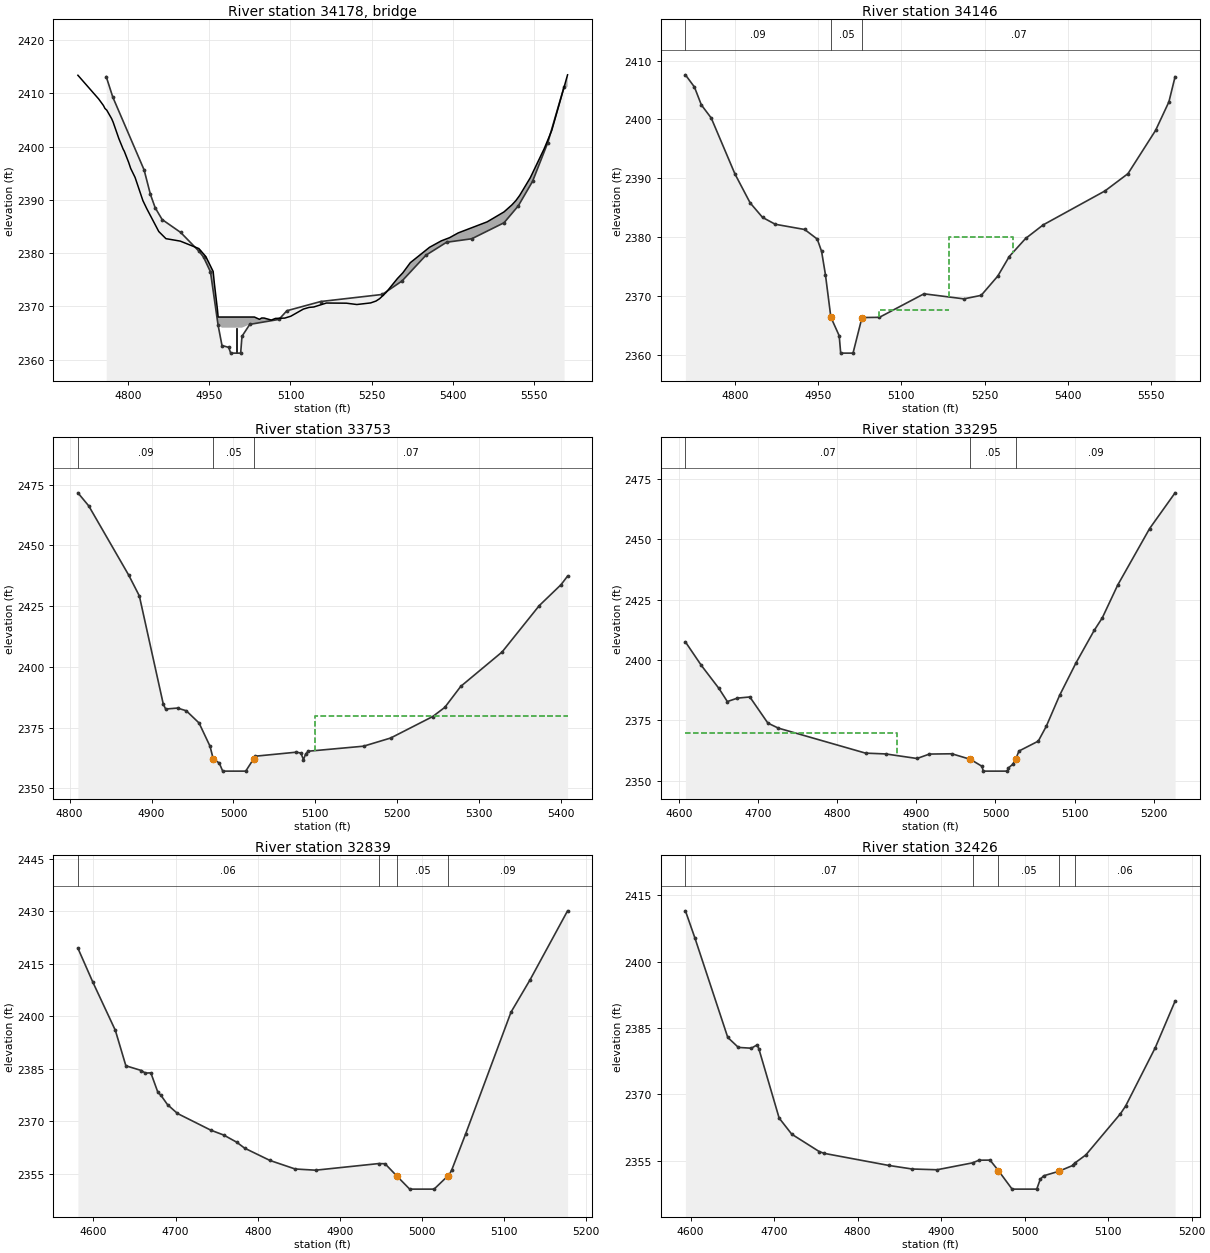
Type RM Length L Ch R = 3 ,34178   ,,,
BEGIN DESCRIPTION:
XS 105 TOR
Structure ID: XS 105
Approximate Survey Structure
END DESCRIPTION:
Bridge Culvert--1,0,-1,-1, 0
Deck Dist Width WeirC Skew NumUp NumDn MinLoCord MaxHiCord MaxSubmerge Is_Ogee
37,12,3,0, 60, 60, , , , 0, 1,1,,
  4707.6  4745.9  4754.8  4757.5  4760.9  4769.8  4772.7  4783.2  4791.3  4793.1
  4801.2  4805.1  4813.2  4827.6  4834.8  4856.9  4870.1  4896.5  4930.9  4943.9
  4957.3  4959.4  4965.3  4966.5  4966.5  5033.5  5033.5  5042.7  5046.9  5051.4
  5064.7  5072.3  5089.5  5100.6  5123.8  5134.5  5143.2  5166.4  5203.3  5222.5
    5248  5257.9  5264.7  5276.5  5297.4  5307.5  5321.3  5356.8  5378.5  5393.9
  5409.7  5463.2  5494.2  5508.6  5516.1  5523.1  5542.8  5568.5  5582.4  5611.6
 2413.41 2408.96 2407.72 2407.18 2406.85 2405.27 2404.59 2401.51 2399.49 2399.17
 2397.07  2395.9 2394.21 2389.86 2388.34 2384.06 2382.72 2382.26 2380.86 2379.34
 2376.56 2374.44 2369.34    2368    2368    2368    2368 2367.57 2367.82 2367.81
 2367.43 2367.74  2367.8 2368.15 2369.49 2369.81 2369.89 2370.63  2370.6 2370.35
 2370.65    2371 2371.45  2372.6 2375.22 2376.31 2378.21  2381.1 2382.31 2382.91
  2383.8 2385.88 2387.74 2389.04 2389.86 2390.83 2394.17 2399.63 2403.04 2413.49
    2334    2334    2334    2334    2334    2334    2334    2334    2334    2334
    2334    2334    2334    2334    2334    2334    2334    2334    2334    2334
    2334    2334    2334    2334    2366    2366    2334    2334    2334    2334
    2334    2334    2334    2334    2334    2334    2334    2334    2334    2334
    2334    2334    2334    2334    2334    2334    2334    2334    2334    2334
    2334    2334    2334    2334    2334    2334    2334    2334    2334    2334
  4707.6  4745.9  4754.8  4757.5  4760.9  4769.8  4772.7  4783.2  4791.3  4793.1
  4801.2  4805.1  4813.2  4827.6  4834.8  4856.9  4870.1  4896.5  4930.9  4943.9
  4957.3  4959.4  4965.3  4966.5  4966.5  5033.5  5033.5  5042.7  5046.9  5051.4
  5064.7  5072.3  5089.5  5100.6  5123.8  5134.5  5143.2  5166.4  5203.3  5222.5
    5248  5257.9  5264.7  5276.5  5297.4  5307.5  5321.3  5356.8  5378.5  5393.9
  5409.7  5463.2  5494.2  5508.6  5516.1  5523.1  5542.8  5568.5  5582.4  5611.6
 2413.41 2408.96 2407.72 2407.18 2406.85 2405.27 2404.59 2401.51 2399.49 2399.17
 2397.07  2395.9 2394.21 2389.86 2388.34 2384.06 2382.72 2382.26 2380.86 2379.34
 2376.56 2374.44 2369.34    2368    2368    2368    2368 2367.57 2367.82 2367.81
 2367.43 2367.74  2367.8 2368.15 2369.49 2369.81 2369.89 2370.63  2370.6 2370.35
 2370.65    2371 2371.45  2372.6 2375.22 2376.31 2378.21  2381.1 2382.31 2382.91
  2383.8 2385.88 2387.74 2389.04 2389.86 2390.83 2394.17 2399.63 2403.04 2413.49
    2334    2334    2334    2334    2334    2334    2334    2334    2334    2334
    2334    2334    2334    2334    2334    2334    2334    2334    2334    2334
    2334    2334    2334    2334    2366    2366    2334    2334    2334    2334
    2334    2334    2334    2334    2334    2334    2334    2334    2334    2334
    2334    2334    2334    2334    2334    2334    2334    2334    2334    2334
    2334    2334    2334    2334    2334    2334    2334    2334    2334    2334
Pier Skew, UpSta & Num, DnSta & Num=  ,5000, 2 ,5000, 2 , 0 , 0 , 0 ,0,0
       2       2
    2354    2366
       2       2
 2353.75    2366
Abutment Skew #Up #Dn= , 2 , 2
  4966.5    4980
    2366 2362.45
  4966.5    4980
    2366 2361.47
Abutment Skew #Up #Dn= , 2 , 2
    5020  5033.5
 2362.35    2366
    5020  5033.5
  2360.8    2366
BR Coef= 1 , 1 , 0 ,1.25, 0 ,,,0.8,0,2,0,
WSPro=,,,, 1 ,,,, 0 ,,,, 0 ,,,,-1 ,-1 ,-1 , 0 , 0 , 0 , 0 , 0
BC Design=,, 0 ,, 0 ,,,,,,
BC HTab HWMax=2413.15

Type RM Length L Ch R = 1 ,34146   ,393,393,393
BEGIN DESCRIPTION:
XS 104
END DESCRIPTION:
XS GIS Cut Line= 6
      1050651.12       856376.56      1050514.83       856430.75
      1050484.45       856524.35      1050431.91       856590.85
      1050164.34       856780.18      1050050.75       856972.94
#Sta/Elev= 30
  4711.2 2407.59  4727.4 2405.52  4739.9 2402.47  4757.7 2400.24  4800.4 2390.72
  4827.7 2385.81    4850 2383.34  4872.9 2382.17  4925.9 2381.28  4948.5 2379.65
  4956.3 2377.56  4963.2 2373.62    4973 2366.36    4988 2363.21  4990.7 2360.25
  5012.9 2360.25    5029  2366.3  5060.4 2366.34  5140.6 2370.34  5212.5 2369.48
  5243.6 2370.08  5273.4 2373.35  5294.1 2376.68  5323.5 2379.75  5355.1 2382.06
  5466.4 2387.84  5507.8 2390.78  5557.5 2398.14  5581.5    2403  5592.6 2407.27
#Mann= 3 ,-1 , 0
  4711.2     .09       0    4973     .05       0    5029     .07       0
#XS Ineff= 3 ,-1
    4900  4940.5 2379.74  5059.5    5185 2367.58    5185    5300    2380
Permanent Ineff=
       F       F       F
Bank Sta=4973,5029
Exp/Cntr=0.5,0.3

Type RM Length L Ch R = 1 ,33753   ,458,458,458
BEGIN DESCRIPTION:
XS 103
END DESCRIPTION:
XS GIS Cut Line= 4
       1050197.5       856226.59      1050105.83       856387.78
      1050054.19       856511.69      1049839.26       856688.28
#Sta/Elev= 30
  4810.1 2471.63  4823.3 2466.27  4872.2 2437.72  4885.1 2429.22  4914.3 2384.74
  4917.2 2382.66  4931.7 2383.06  4942.4 2381.95    4958 2376.92  4971.4 2367.35
  4975.2 2362.28  4982.7  2360.4  4986.9 2357.11    5015 2357.11  5024.7 2362.21
    5026 2363.23  5076.9 2364.91  5082.3 2364.54  5085.5 2361.82  5088.2 2364.21
  5091.3  2365.3  5158.8 2367.37  5191.9 2370.73  5243.3 2379.58    5258 2383.34
  5277.5 2391.99    5328 2406.15  5373.3 2425.21    5400 2433.86  5407.9 2437.37
#Mann= 3 ,-1 , 0
  4810.1     .09       0  4975.2     .05       0  5024.7     .07       0
#XS Ineff= 2 , 0
       0                    5100       0    2380
Permanent Ineff=
       F       F
Bank Sta=4975.2,5024.7
Exp/Cntr=0.3,0.1

Type RM Length L Ch R = 1 ,33295   ,456,456,456
BEGIN DESCRIPTION:
XS 102
END DESCRIPTION:
XS GIS Cut Line= 4
      1049957.81       856053.89      1049740.96       856177.81
      1049617.04       856349.91      1049482.93       856431.57
#Sta/Elev= 30
  4608.2 2407.51  4628.2 2397.83  4650.5 2388.27  4661.2 2382.82  4673.9 2384.24
  4689.6 2384.72  4712.4 2373.91  4725.6 2371.83  4835.8 2361.48  4861.4 2361.14
  4900.9 2359.26  4916.5 2361.09  4944.9 2361.21  4968.4  2358.9  4982.9 2356.04
  4984.6 2354.03  5015.1 2354.03  5016.3 2355.33    5022  2356.9  5025.8 2359.17
  5029.7 2362.34  5054.1 2366.44  5064.3 2372.63  5081.1  2385.4  5101.7 2398.77
  5124.7 2412.23    5135 2417.45  5154.5 2431.03  5194.8  2454.4    5227 2469.19
#Mann= 3 ,-1 , 0
  4608.2     .07       0  4968.4     .05       0  5025.8     .09       0
#XS Ineff= 2 , 0
       0    4875    2370               0
Permanent Ineff=
       F       F
Bank Sta=4968.4,5025.8
Exp/Cntr=0.3,0.1

Type RM Length L Ch R = 1 ,32839   ,413,413,413
BEGIN DESCRIPTION:
XS 101
END DESCRIPTION:
XS GIS Cut Line= 4
      1049823.57       855812.94      1049658.35       855871.46
      1049441.49       855909.32      1049270.28       856013.94
#Sta/Elev= 30
  4581.1 2419.48  4599.3 2409.77  4626.7    2396  4639.5 2385.89  4658.5 2384.53
  4663.2 2383.81  4669.9 2383.87  4678.5 2378.29  4682.1 2377.48  4690.2 2374.79
  4702.3 2372.27  4742.9  2367.5  4758.6 2366.11  4774.3 2364.08  4784.1 2362.36
  4814.9 2358.85  4845.6 2356.41  4870.5 2356.07  4947.3 2357.96    4955 2357.91
  4969.8  2354.3    4985 2350.66  5014.7 2350.66  5031.5 2354.44  5032.1 2354.39
  5036.1 2356.07  5053.2 2366.48  5108.3 2401.19  5131.5 2410.43  5177.2 2430.15
#Mann= 4 ,-1 , 0
  4581.1     .06       0  4947.3     .09       0  4969.8     .05       0
  5031.5     .09       0
Bank Sta=4969.8,5031.5
Exp/Cntr=0.3,0.1

Type RM Length L Ch R = 1 ,32426   ,550,550,550
BEGIN DESCRIPTION:
XS 100
END DESCRIPTION:
XS GIS Cut Line= 5
      1049685.89       855489.38      1049534.43       855537.57
      1049324.46       855530.69      1049228.08       855541.01
      1049111.05       855568.55
#Sta/Elev= 30
  4593.9 2411.47  4605.3 2405.31  4644.6 2382.85  4657.3 2380.59  4672.8 2380.41
  4679.9 2381.18    4682 2380.16  4706.1 2364.62  4721.2 2360.97  4754.2 2357.03
  4760.2 2356.63  4837.5  2353.9  4865.3  2353.1  4895.2 2352.93  4937.6 2354.49
  4945.4 2355.09  4958.6 2355.11  4968.7 2352.71    4985 2348.55  5014.5 2348.55
  5018.6 2350.74  5022.7 2351.56  5040.7 2352.57  5057.6  2353.9  5059.7 2354.39
  5073.3 2356.29  5114.7  2365.6  5120.9 2367.34  5156.4 2380.54  5180.1 2391.05
#Mann= 5 ,-1 , 0
  4593.9     .07       0  4937.6     .09       0  4968.7     .05       0
  5040.7     .09       0  5059.7     .06       0
Bank Sta=4968.7,5040.7
Exp/Cntr=0.3,0.1

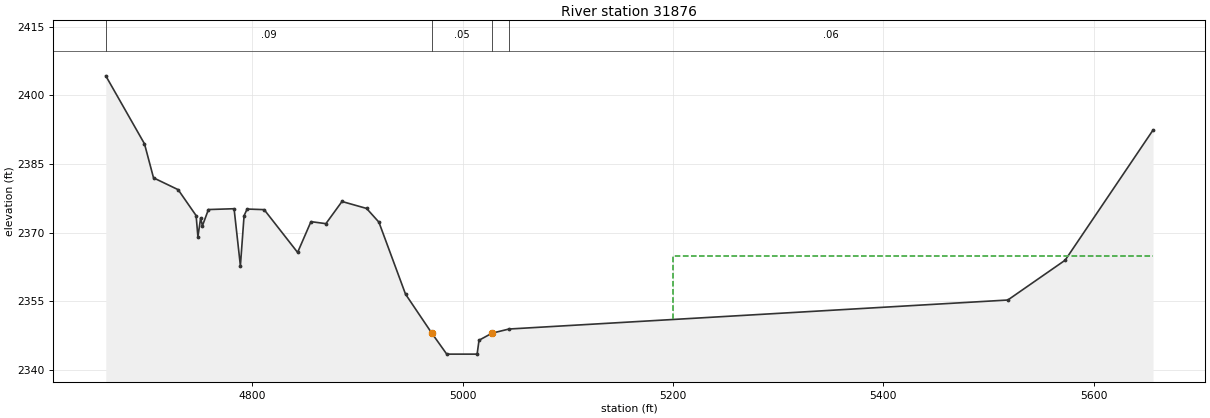
Type RM Length L Ch R = 1 ,31876   ,601,601,601
BEGIN DESCRIPTION:
XS 99
END DESCRIPTION:
XS GIS Cut Line= 5
      1049861.43       855134.84      1049641.14       855069.44
      1049479.36       855069.44      1049073.19       855090.09
      1048890.75       855165.82
#Sta/Elev= 30
  4660.6 2404.25  4697.4 2389.41    4706 2381.98  4729.4  2379.4  4746.5 2373.74
  4748.2 2369.12  4750.8 2373.21  4752.5 2371.52  4758.2 2375.06  4782.6 2375.24
  4788.6 2362.78  4792.1 2373.72    4795 2375.17  4811.2 2375.04    4843  2365.7
  4855.7 2372.42  4869.9 2371.98  4885.2 2376.82  4908.6  2375.3  4920.3 2372.31
  4945.6  2356.6  4970.5 2348.11  4984.8  2343.5  5013.7  2343.5  5015.5 2346.53
  5027.8 2348.07    5044 2348.98  5518.3 2355.31  5572.8    2364  5656.4 2392.42
#Mann= 4 ,-1 , 0
  4660.6     .09       0  4970.5     .05       0  5027.8     .09       0
    5044     .06       0
#XS Ineff= 2 , 0
       0                    5200       0    2365
Permanent Ineff=
       F       F
Bank Sta=4970.5,5027.8
Exp/Cntr=0.3,0.1