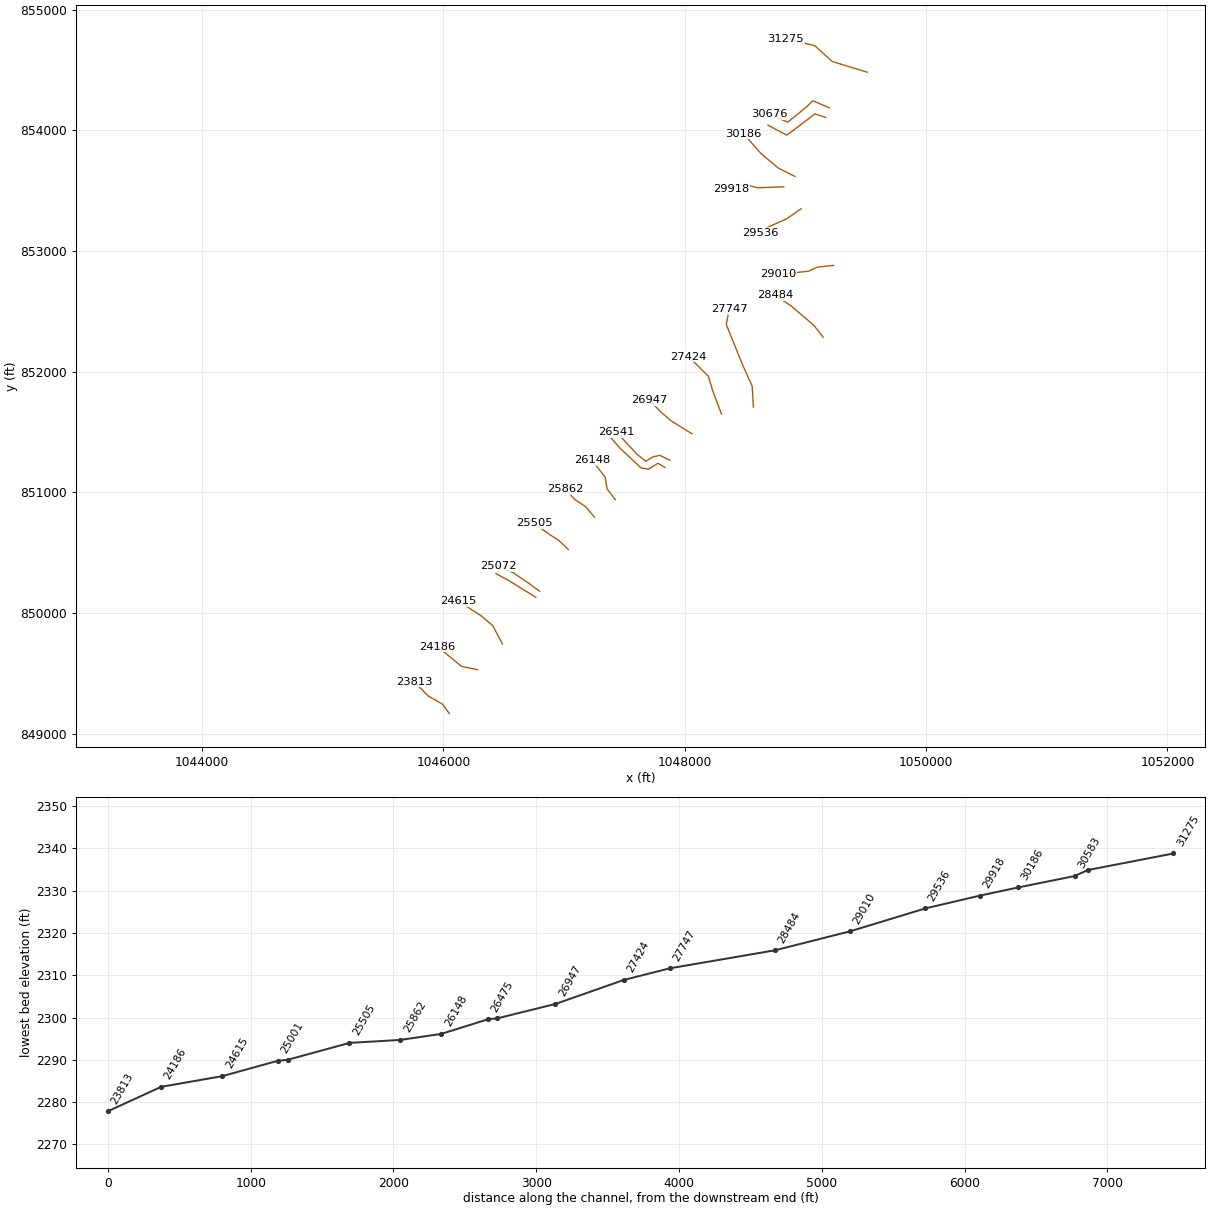
HEC-RAS study lds_big_rock_crk.prj: Big Rock Creek Limited Detail Study

--- lds_big_rock_crk.g01 (geometry) --- (continued)

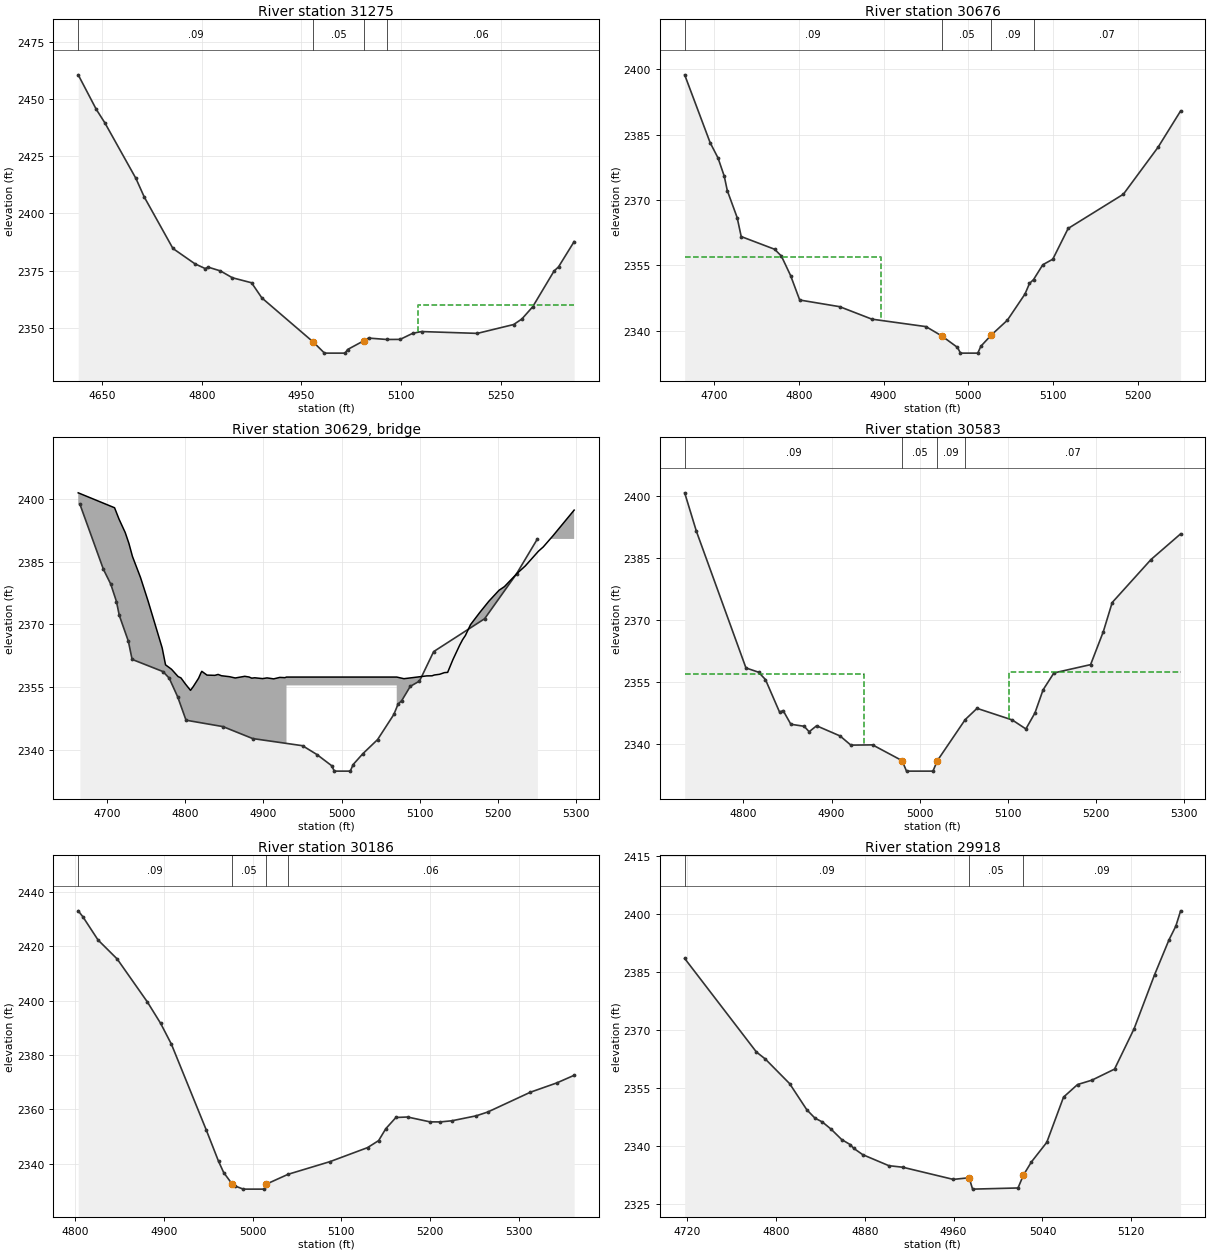
Type RM Length L Ch R = 1 ,31275   ,599,599,599
BEGIN DESCRIPTION:
XS 98
END DESCRIPTION:
XS GIS Cut Line= 4
      1049511.67       854481.34       1049221.2       854570.33
      1049076.63       854701.13      1048835.68       854759.65
#Sta/Elev= 30
    4614 2460.73  4641.2  2445.6    4654 2439.75  4700.9 2415.33  4713.4 2407.23
  4756.6 2384.66  4789.7 2377.95  4805.1 2375.87  4809.6 2376.48    4828 2374.84
  4846.1 2371.83    4875 2369.63  4890.5    2363  4968.1 2343.62  4984.8 2338.81
  5015.8 2338.81  5019.5 2340.38  5044.4 2344.29  5051.1 2345.41  5078.4 2344.79
  5098.7 2344.83  5117.7  2347.5  5130.9 2348.26  5214.9 2347.46  5269.6 2351.34
  5281.9 2353.75  5298.2 2359.08  5330.4 2374.76  5337.2 2376.61  5360.7 2387.68
#Mann= 4 ,-1 , 0
    4614     .09       0  4968.1     .05       0  5044.4     .09       0
  5078.4     .06       0
#XS Ineff= 2 , 0
       0                    5125       0    2360
Permanent Ineff=
       F       F
Bank Sta=4968.1,5044.4
Exp/Cntr=0.5,0.3

Type RM Length L Ch R = 1 ,30676   ,93,93,93
BEGIN DESCRIPTION:
XS 97
END DESCRIPTION:
XS GIS Cut Line= 5
      1049197.68       854186.51      1049061.27       854244.75
      1049007.63       854192.64      1048852.84       854066.97
      1048704.18       854132.87
#Sta/Elev= 30
  4665.3 2398.72  4695.3 2383.18  4704.7 2379.63    4712 2375.47  4715.6 2372.16
  4727.2 2365.99    4732 2361.63  4771.4 2358.72  4779.4 2357.16  4790.3 2352.67
    4801 2347.08  4848.2 2345.55  4886.2 2342.69    4950 2340.98  4968.4 2338.87
  4987.1 2336.22  4990.7  2334.9  5011.1  2334.9  5014.7 2336.47  5027.1 2339.06
    5046 2342.45  5066.8 2348.46  5072.1 2350.88  5076.9 2351.77  5087.8 2355.17
  5099.6 2356.44  5117.7 2363.49  5182.9 2371.35  5223.8 2382.12  5250.4 2390.44
#Mann= 4 ,-1 , 0
  4665.3     .09       0  4968.4     .05       0  5027.1     .09       0
  5076.9     .07       0
#XS Ineff= 2 , 0
       0  4897.5 2357.05  5102.5       0 2357.51
Permanent Ineff=
       F       F
Bank Sta=4968.4,5027.1
Exp/Cntr=0.5,0.3

Type RM Length L Ch R = 3 ,30629   ,,,
BEGIN DESCRIPTION:
XS 96 TOR
Structure ID: XS 96
Approximate Survey Structure
END DESCRIPTION:
Bridge Culvert--1,0,-1,-1, 0
Deck Dist Width WeirC Skew NumUp NumDn MinLoCord MaxHiCord MaxSubmerge Is_Ogee
32,30,3,0, 60, 60, , , , 0, 1,1,,
  4663.1  4709.6  4715.3  4723.2  4727.9  4732.5  4742.8  4752.4  4770.5  4774.8
  4782.4  4790.9  4794.5    4800  4806.7  4810.3  4817.1  4820.1  4821.2  4827.8
  4837.9    4842  4846.3  4856.6  4863.9  4876.1  4881.7    4885  4888.8  4898.9
  4904.6  4913.1  4920.9  4927.4  4929.5  4929.5  5070.5  5070.5  5079.7  5108.8
  5115.6  5118.7  5125.3  5131.5  5135.6  5142.3    5151  5154.7  5158.3  5164.9
  5176.7  5188.3  5201.3  5208.2  5224.6  5234.9  5251.8  5257.9  5270.1  5297.4
 2401.47  2397.9 2395.18 2391.98  2389.4 2386.24  2381.2 2375.62 2364.36 2360.32
 2359.27 2357.51  2357.2 2355.79 2354.23 2355.14 2357.14 2358.42 2358.77 2357.87
 2357.81 2358.03 2357.72 2357.49 2357.18 2357.58 2357.41 2357.14 2357.23 2357.03
  2357.2 2356.97 2357.32 2357.26  2357.4  2357.4  2357.4  2357.4 2357.01 2357.68
  2357.7  2357.9 2358.06 2358.46 2358.52 2361.56 2365.03 2366.34 2367.35 2369.95
 2372.85 2375.54 2378.16 2379.03 2382.23 2383.98 2387.52 2388.53 2391.15 2397.34
    2313    2313    2313    2313    2313    2313    2313    2313    2313    2313
    2313    2313    2313    2313    2313    2313    2313    2313    2313    2313
    2313    2313    2313    2313    2313    2313    2313    2313    2313    2313
    2313    2313    2313    2313    2313  2355.4  2355.4    2313    2313    2313
    2313    2313    2313    2313    2313    2313    2313    2313    2313    2313
    2313    2313    2313    2313    2313    2313    2313    2313    2313    2313
  4663.1  4709.6  4715.3  4723.2  4727.9  4732.5  4742.8  4752.4  4770.5  4774.8
  4782.4  4790.9  4794.5    4800  4806.7  4810.3  4817.1  4820.1  4821.2  4827.8
  4837.9    4842  4846.3  4856.6  4863.9  4876.1  4881.7    4885  4888.8  4898.9
  4904.6  4913.1  4920.9  4927.4  4929.5  4929.5  5070.5  5070.5  5079.7  5108.8
  5115.6  5118.7  5125.3  5131.5  5135.6  5142.3    5151  5154.7  5158.3  5164.9
  5176.7  5188.3  5201.3  5208.2  5224.6  5234.9  5251.8  5257.9  5270.1  5297.4
 2401.47  2397.9 2395.18 2391.98  2389.4 2386.24  2381.2 2375.62 2364.36 2360.32
 2359.27 2357.51  2357.2 2355.79 2354.23 2355.14 2357.14 2358.42 2358.77 2357.87
 2357.81 2358.03 2357.72 2357.49 2357.18 2357.58 2357.41 2357.14 2357.23 2357.03
  2357.2 2356.97 2357.32 2357.26  2357.4  2357.4  2357.4  2357.4 2357.01 2357.68
  2357.7  2357.9 2358.06 2358.46 2358.52 2361.56 2365.03 2366.34 2367.35 2369.95
 2372.85 2375.54 2378.16 2379.03 2382.23 2383.98 2387.52 2388.53 2391.15 2397.34
    2313    2313    2313    2313    2313    2313    2313    2313    2313    2313
    2313    2313    2313    2313    2313    2313    2313    2313    2313    2313
    2313    2313    2313    2313    2313    2313    2313    2313    2313    2313
    2313    2313    2313    2313    2313  2355.4  2355.4    2313    2313    2313
    2313    2313    2313    2313    2313    2313    2313    2313    2313    2313
    2313    2313    2313    2313    2313    2313    2313    2313    2313    2313
Abutment Skew #Up #Dn= , 2 , 2
  4929.5    4952
  2355.4 2340.89
  4929.5    4975
  2355.4 2336.54
Abutment Skew #Up #Dn= , 2 , 2
  5045.9  5070.5
 2342.68  2355.4
    5025  5070.5
 2337.33  2355.4
BR Coef= 1 , 1 , 0 ,1.25, 0 ,,,0.8,0,2,0,
WSPro=,,,, 1 ,,,, 0 ,,,, 0 ,,,,-1 ,-1 ,-1 , 0 , 0 , 0 , 0 , 0
BC Design=,, 0 ,, 0 ,,,,,,
BC HTab HWMax=2398.72

Type RM Length L Ch R = 1 ,30583   ,397,397,397
BEGIN DESCRIPTION:
XS 95
END DESCRIPTION:
XS GIS Cut Line= 5
      1049167.02       854106.82      1049078.13       854135.94
      1048917.21       854013.33      1048845.18       853959.69
      1048688.85       854042.45
#Sta/Elev= 30
  4733.4 2400.68  4746.7 2391.39  4802.9 2358.39  4817.2 2357.36    4825 2355.59
    4841 2347.73  4845.1 2348.09  4853.8 2344.79  4868.9  2344.3  4874.6 2342.98
    4883 2344.42  4909.6 2341.97  4921.9 2339.75  4946.5 2339.81    4980    2336
    4985 2333.47    5015 2333.47    5020    2336  5051.6 2345.92    5065 2348.63
  5104.9 2345.83  5120.4 2343.66  5130.7 2347.53  5139.9  2353.1  5152.2 2357.18
  5193.8 2359.19  5208.2 2367.14  5218.3 2374.19  5262.3 2384.57  5295.9 2390.77
#Mann= 4 ,-1 , 0
  4733.4     .09       0    4980     .05       0    5020     .09       0
  5051.6     .07       0
#XS Ineff= 2 , 0
       0 4937.15 2357.04  5101.5       0 2357.49
Permanent Ineff=
       F       F
Bank Sta=4980,5020
Exp/Cntr=0.5,0.3

Type RM Length L Ch R = 1 ,30186   ,268,268,268
BEGIN DESCRIPTION:
XS 94
END DESCRIPTION:
XS GIS Cut Line= 4
      1048912.61       853617.92      1048774.68       853686.89
      1048633.68        853804.9      1048488.08       853970.42
#Sta/Elev= 30
  4803.7 2432.92    4809 2430.72    4826 2422.23  4847.6 2415.24  4881.6 2399.46
  4896.6 2391.57  4908.7 2383.93    4948 2352.41  4961.7 2341.01  4967.5 2336.87
  4976.6 2332.83  4979.8 2331.98  4989.6 2330.77    5013 2330.77  5015.4 2332.58
  5040.1 2336.22  5087.4 2340.88  5129.5    2346    5142 2348.58  5150.1 2352.96
  5161.5 2357.07  5174.6 2357.24  5199.9 2355.46  5211.5 2355.44  5224.5 2355.86
  5251.8 2357.67  5264.8 2359.06  5312.9 2366.34  5342.6 2369.75  5362.2 2372.55
#Mann= 4 ,-1 , 0
  4803.7     .09       0  4976.6     .05       0  5015.4     .09       0
  5040.1     .06       0
Bank Sta=4976.6,5015.4
Exp/Cntr=0.3,0.1

Type RM Length L Ch R = 1 ,29918   ,382,382,382
BEGIN DESCRIPTION:
XS 93
END DESCRIPTION:
XS GIS Cut Line= 4
      1048820.66       853532.09      1048603.75       853523.32
      1048491.49       853553.94      1048386.03       853513.12
#Sta/Elev= 30
  4717.9 2388.53  4782.5 2364.31  4790.4 2362.53  4812.4 2356.13  4827.9 2349.35
  4835.2 2347.21  4841.9  2346.2  4849.8 2344.33  4859.3 2341.65  4867.1 2340.33
  4869.9 2339.43  4878.2 2337.75  4901.7  2334.9  4914.2  2334.5  4959.7 2331.35
    4974 2331.77  4977.1 2328.83    5018 2329.13 5022.88 2332.46  5030.1 2335.88
  5043.9 2340.94    5059 2352.65  5071.6  2355.9  5084.5 2357.03  5104.9 2359.89
  5122.5 2370.33  5140.9 2384.28  5153.9 2393.33  5160.1 2396.91  5164.4 2400.86
#Mann= 3 ,-1 , 0
  4717.9     .09       0    4974     .05       0 5022.88     .09       0
#XS Ineff= 2 , 0
       0    4900                       0
Permanent Ineff=
       T       F
Bank Sta=4974,5022.88
Exp/Cntr=0.3,0.1

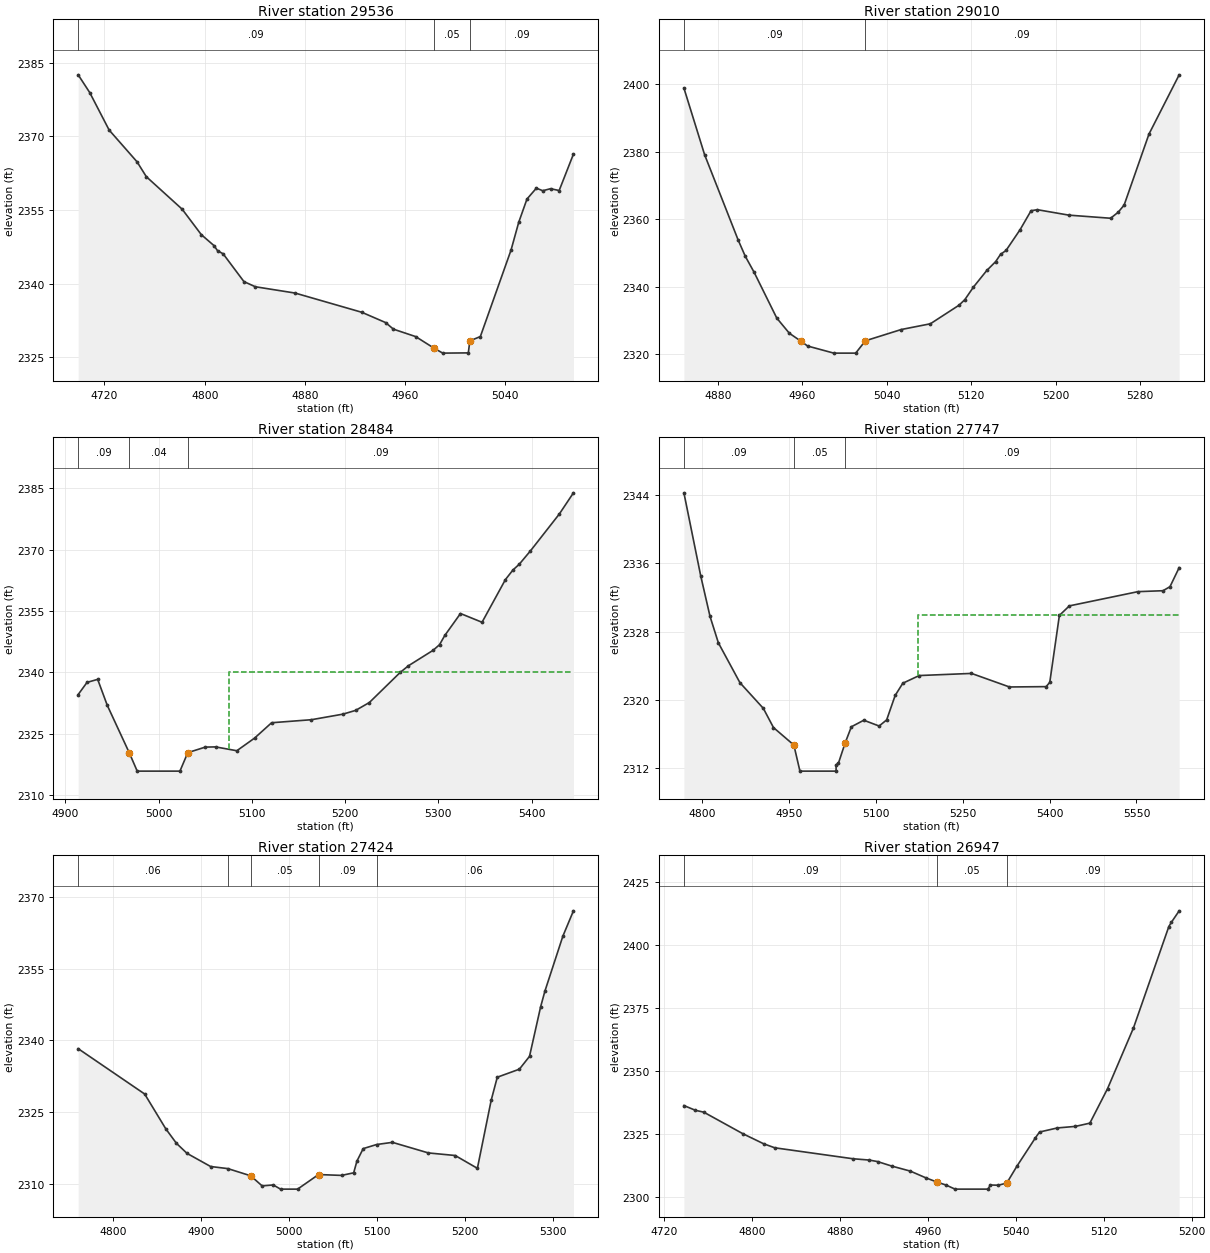
Type RM Length L Ch R = 1 ,29536   ,526,526,526
BEGIN DESCRIPTION:
XS 92
END DESCRIPTION:
XS GIS Cut Line= 4
      1048964.35       853349.83      1048841.88       853264.78
      1048678.59       853193.34      1048624.16       853152.52
#Sta/Elev= 30
    4699 2382.57  4708.2 2378.96  4723.7 2371.31    4746 2364.82  4753.4 2361.79
    4782 2355.16  4797.3 2349.96  4807.5 2347.71  4810.2  2346.7  4814.7 2346.06
  4831.3 2340.39  4840.4 2339.34  4872.2 2338.05  4925.4 2334.13  4944.4 2332.03
  4950.6 2330.69  4968.4 2329.17  4982.9 2326.83    4990  2325.8  5010.4 2325.85
  5011.6  2328.3    5020 2329.18  5044.5 2346.83  5050.6 2352.47  5057.2 2357.23
  5064.7 2359.45  5069.8 2358.93    5076 2359.34  5082.9 2358.97  5094.3  2366.4
#Mann= 3 ,-1 , 0
    4699     .09       0  4982.9     .05       0  5011.6     .09       0
Bank Sta=4982.9,5011.6
Exp/Cntr=0.3,0.1

Type RM Length L Ch R = 1 ,29010   ,526,526,526
BEGIN DESCRIPTION:
XS 91
END DESCRIPTION:
XS GIS Cut Line= 4
      1049233.09       852880.37      1049100.42       852866.76
      1049025.58       852832.74      1048773.84       852805.53
#Sta/Elev= 30
    4848 2398.79  4867.6 2379.07  4899.4 2353.81  4906.1 2349.03  4914.5 2344.28
  4935.9 2330.76  4947.8 2326.27    4959 2323.87  4965.1 2322.49  4989.9 2320.39
  5010.6 2320.39  5019.8 2324.04  5053.7 2327.37  5081.3 2329.07  5108.4 2334.56
  5113.9  2336.2  5122.1 2339.94  5134.7 2344.84  5143.1 2347.46  5147.7  2349.6
  5152.9 2350.75  5166.2 2356.89  5176.6 2362.51  5182.6 2362.81  5212.4  2361.2
  5251.9 2360.28  5259.1 2362.07  5264.7 2364.18  5288.2 2385.17  5316.8  2402.7
#Mann= 2 ,-1 , 0
    4848     .09       0  5019.8     .09       0
Bank Sta=4959,5019.8
Exp/Cntr=0.3,0.1

Type RM Length L Ch R = 1 ,28484   ,737,737,737
BEGIN DESCRIPTION:
XS 90
END DESCRIPTION:
XS GIS Cut Line= 4
      1049147.22       852284.99      1049069.81        852383.7
       1048882.7       852543.58      1048750.03       852632.03
#Sta/Elev= 30
  4913.8 2334.61  4923.3 2337.58  4934.7 2338.31    4945 2331.97 4968.69 2320.32
  4977.1  2315.9  5022.9  2315.9  5031.3 2320.41  5050.1 2321.77  5061.1 2321.82
  5083.9 2320.88    5103 2323.98  5121.2 2327.72  5163.9 2328.46  5197.7 2329.82
  5211.3 2330.74    5226 2332.66    5259    2340  5267.9 2341.64  5294.3 2345.41
  5301.2 2346.78  5306.9 2349.05  5323.7  2354.4  5346.8 2352.26  5371.9  2362.7
  5379.9 2365.02  5386.8 2366.46  5398.7  2369.7  5429.7 2378.72  5444.8 2383.88
#Mann= 3 ,-1 , 0
  4913.8     .09       0 4968.69     .04       0  5031.3     .09       0
#XS Ineff= 2 , 0
       0                  5075.7       0    2340
Permanent Ineff=
       F       F
Bank Sta=4968.69,5031.3
Exp/Cntr=0.3,0.1

Type RM Length L Ch R = 1 ,27747   ,323,323,323
BEGIN DESCRIPTION:
XS 89
END DESCRIPTION:
XS GIS Cut Line= 5
      1048568.53       851706.81      1048558.33        851880.3
      1048480.09        852053.8      1048344.01       852390.59
      1048367.82       852516.45
#Sta/Elev= 30
  4768.4 2344.28  4797.5 2334.52  4813.5 2329.79  4827.9 2326.69  4865.2 2322.01
  4905.6    2319  4923.1 2316.75  4958.3  2314.7  4968.8 2311.64  5031.2 2311.64
  5031.3 2312.39  5035.3 2312.57  5046.6 2314.89  5057.6 2316.84  5079.1 2317.61
  5105.6 2316.93  5118.6 2317.65  5133.3 2320.52  5146.5 2321.95  5174.8 2322.85
  5265.1  2323.1  5330.7 2321.51    5394 2321.55  5400.3 2322.05  5416.9  2329.9
  5434.1 2331.02  5552.6 2332.69  5595.9  2332.8  5607.9 2333.27  5623.8 2335.51
#Mann= 3 , 0 , 0
  4768.4     .09       0  4958.3     .05       0  5046.6     .09       0
#XS Ineff= 2 , 0
       0                    5173       0    2330
Permanent Ineff=
       F       F
Bank Sta=4958.3,5046.6
Exp/Cntr=0.3,0.1

Type RM Length L Ch R = 1 ,27424   ,477,477,477
BEGIN DESCRIPTION:
XS 88
END DESCRIPTION:
XS GIS Cut Line= 4
      1048304.38       851648.89      1048232.95         851836.
      1048195.52       851961.86      1048032.23       852125.15
#Sta/Elev= 30
  4760.5 2338.24    4836 2328.76    4860 2321.48  4872.1 2318.45  4884.1 2316.35
  4910.9  2313.6  4930.5 2313.16  4956.4 2311.66  4969.4 2309.55  4982.1 2309.74
  4990.3 2308.87  5009.7 2308.87  5033.5 2311.92  5059.6 2311.74  5073.4 2312.28
  5077.1 2314.74  5084.2 2317.34  5099.5  2318.2  5117.4 2318.65  5158.2 2316.44
  5188.7  2315.9  5213.9 2313.22  5229.6 2327.47  5236.5 2332.27  5261.6 2333.95
  5273.1 2336.63  5285.7 2346.97  5290.6 2350.28    5311 2361.77    5323 2367.06
#Mann= 5 ,-1 , 0
  4760.5     .06       0  4930.5     .09       0  4956.4     .05       0
  5033.5     .09       0  5099.5     .06       0
Bank Sta=4956.4,5033.5
Exp/Cntr=0.3,0.1

Type RM Length L Ch R = 1 ,26947   ,406,406,406
BEGIN DESCRIPTION:
XS 87
END DESCRIPTION:
XS GIS Cut Line= 4
      1048059.45        851485.6      1047889.36       851591.06
      1047800.91        851665.9      1047709.06       851764.56
#Sta/Elev= 30
  4737.8 2336.31  4748.3 2334.43  4755.9 2333.69  4791.5 2325.15  4810.4 2321.17
  4820.5 2319.58  4891.7 2315.24  4906.6 2314.72  4914.1 2314.12    4927 2312.34
    4944 2310.33  4958.4 2307.61  4968.2 2306.01  4976.6 2304.79  4984.6 2303.21
  5014.5 2303.21  5016.8 2304.84    5024 2304.76  5031.7 2305.62  5040.9 2312.29
  5057.7  2323.5  5061.5 2325.83  5077.8 2327.45  5094.2 2328.06  5107.3 2329.34
  5123.4    2343    5147 2367.05  5179.2 2407.23  5181.6 2408.96  5188.6 2413.44
#Mann= 3 ,-1 , 0
  4737.8     .09       0  4968.2     .05       0  5031.7     .09       0
Bank Sta=4968.2,5031.7
Exp/Cntr=0.5,0.3

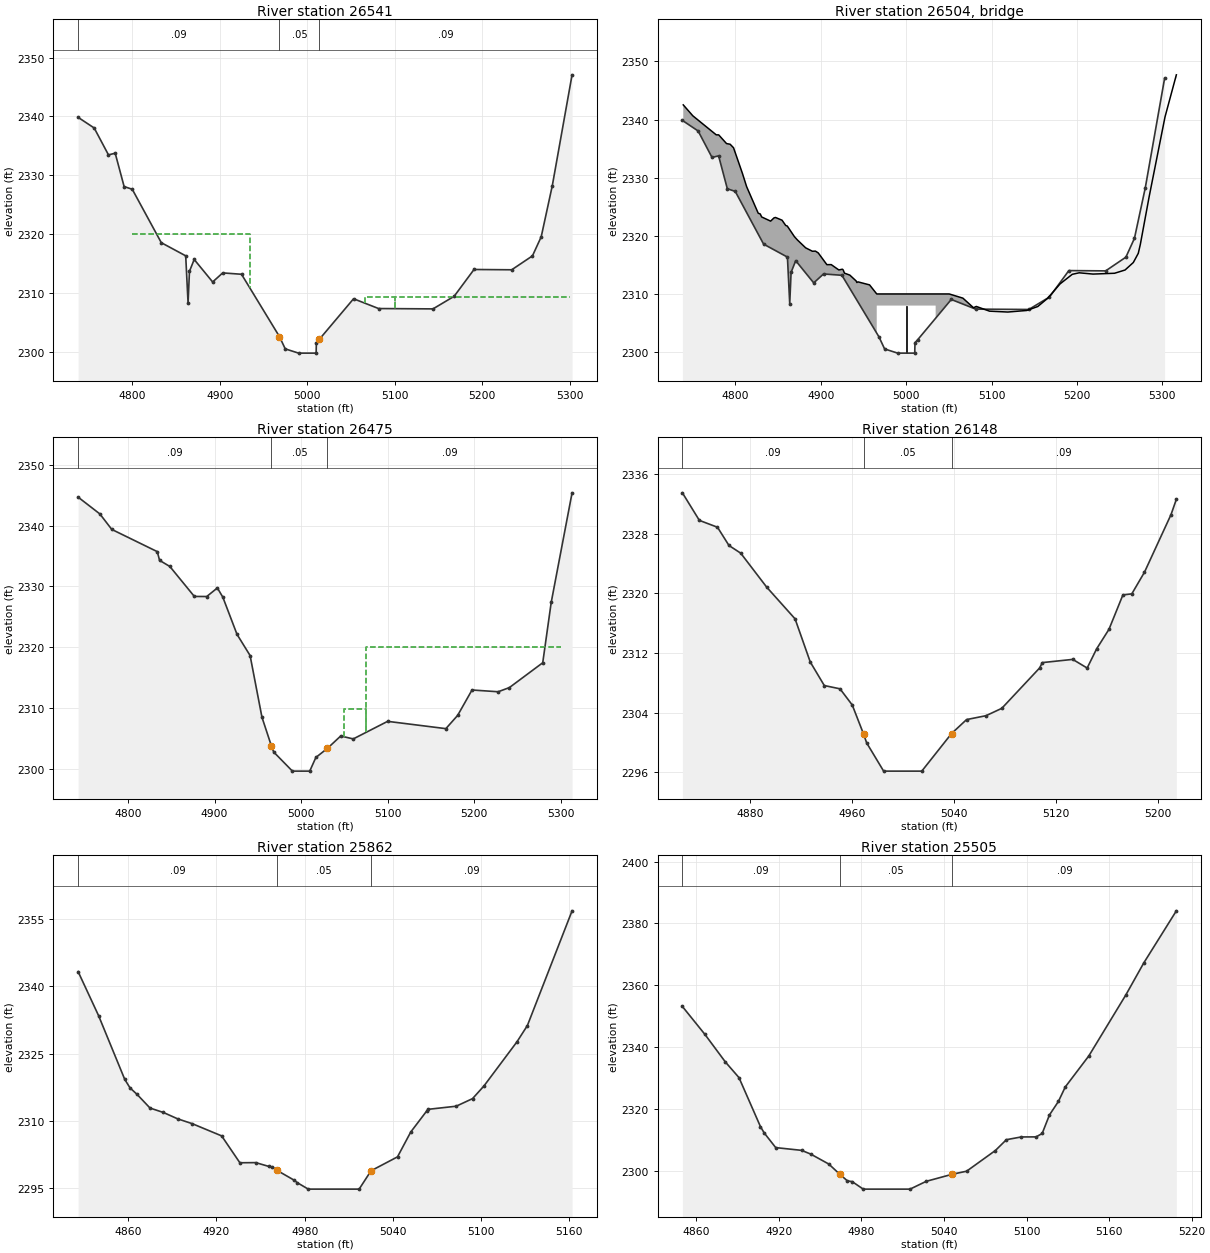
Type RM Length L Ch R = 1 ,26541   ,66,66,66
BEGIN DESCRIPTION:
XS 86
END DESCRIPTION:
XS GIS Cut Line= 6
      1047878.21       851265.94      1047792.29       851306.77
      1047732.52       851292.98      1047677.34       851257.73
      1047602.25        851317.5      1047435.19       851498.34
#Sta/Elev= 30
  4737.9 2339.85  4756.3 2338.04  4772.6 2333.48  4780.3 2333.76  4790.5  2328.1
  4799.8 2327.64    4833 2318.57  4860.9 2316.34  4863.6 2308.33  4865.2 2313.71
  4870.6 2315.72  4891.7  2311.9  4903.2 2313.44  4924.7 2313.21  4968.1 2302.62
  4974.7 2300.54    4990 2299.82    5010 2299.82  5010.3 2301.62  5013.6 2302.15
  5052.8 2309.05  5081.4 2307.39  5143.6 2307.33  5167.8 2309.47  5190.5 2314.02
  5233.6 2313.97  5257.3 2316.33  5267.3 2319.56    5280 2328.25  5302.6 2347.07
#Mann= 3 ,-1 , 0
  4737.9     .09       0  4968.1     .05       0  5013.6     .09       0
#XS Ineff= 3 ,-1
    4800  4934.5    2320  5065.5    5100  2309.3    5100    5300  2309.3
Permanent Ineff=
       F       F       F
Bank Sta=4968.1,5013.6
Exp/Cntr=0.5,0.3

Type RM Length L Ch R = 3 ,26504   ,,,
BEGIN DESCRIPTION:
XS 85 TOR
Structure ID: XS 85
Approximate Survey Structure
END DESCRIPTION:
Bridge Culvert--1,0,-1,-1, 0
Deck Dist Width WeirC Skew NumUp NumDn MinLoCord MaxHiCord MaxSubmerge Is_Ogee
31,12,3,0, 60, 60, , , , 0, 1,1,,
  4738.9  4750.1  4777.5  4780.4  4789.6  4793.8  4797.8  4808.3  4813.1  4826.7
  4829.1  4830.7  4841.2  4845.2  4846.9  4854.6  4858.9  4860.7  4869.1  4872.4
  4882.2  4890.1  4893.7    4897  4907.1  4912.2  4921.1  4925.3  4926.2  4927.7
    4934  4941.4  4942.2  4943.5  4957.1  4965.5  4965.5  5034.5  5034.5  5050.4
  5066.4  5078.8  5082.1  5097.6    5119  5141.2  5154.1  5165.7  5180.1  5194.5
  5202.6  5218.8    5244  5256.3    5266  5271.8  5274.2  5284.5  5303.1  5316.4
 2342.53 2340.65 2337.38 2337.37 2335.87 2335.76 2335.15  2330.7 2328.47 2323.89
 2323.76 2323.25 2322.53 2323.09 2323.16 2322.69 2321.78 2321.69 2319.86 2319.32
 2317.94 2317.35 2317.37 2317.06 2315.04 2315.05 2314.13 2314.26 2314.13 2313.58
 2313.24 2312.23 2311.97 2312.08 2311.56    2310    2310    2310    2310    2310
 2309.28 2307.63 2307.85 2307.04 2306.89 2307.16 2307.84 2309.26 2311.72 2313.38
 2313.64 2313.42 2313.56 2314.12 2315.41 2316.99 2318.52 2326.71 2340.45  2347.7
  2272.5  2272.5  2272.5  2272.5  2272.5  2272.5  2272.5  2272.5  2272.5  2272.5
  2272.5  2272.5  2272.5  2272.5  2272.5  2272.5  2272.5  2272.5  2272.5  2272.5
  2272.5  2272.5  2272.5  2272.5  2272.5  2272.5  2272.5  2272.5  2272.5  2272.5
  2272.5  2272.5  2272.5  2272.5  2272.5  2272.5    2308    2308  2272.5  2272.5
  2272.5  2272.5  2272.5  2272.5  2272.5  2272.5  2272.5  2272.5  2272.5  2272.5
  2272.5  2272.5  2272.5  2272.5  2272.5  2272.5  2272.5  2272.5  2272.5  2272.5
  4738.9  4750.1  4777.5  4780.4  4789.6  4793.8  4797.8  4808.3  4813.1  4826.7
  4829.1  4830.7  4841.2  4845.2  4846.9  4854.6  4858.9  4860.7  4869.1  4872.4
  4882.2  4890.1  4893.7    4897  4907.1  4912.2  4921.1  4925.3  4926.2  4927.7
    4934  4941.4  4942.2  4943.5  4957.1  4965.5  4965.5  5034.5  5034.5  5050.4
  5066.4  5078.8  5082.1  5097.6    5119  5141.2  5154.1  5165.7  5180.1  5194.5
  5202.6  5218.8    5244  5256.3    5266  5271.8  5274.2  5284.5  5303.1  5316.4
 2342.53 2340.65 2337.38 2337.37 2335.87 2335.76 2335.15  2330.7 2328.47 2323.89
 2323.76 2323.25 2322.53 2323.09 2323.16 2322.69 2321.78 2321.69 2319.86 2319.32
 2317.94 2317.35 2317.37 2317.06 2315.04 2315.05 2314.13 2314.26 2314.13 2313.58
 2313.24 2312.23 2311.97 2312.08 2311.56    2310    2310    2310    2310    2310
 2309.28 2307.63 2307.85 2307.04 2306.89 2307.16 2307.84 2309.26 2311.72 2313.38
 2313.64 2313.42 2313.56 2314.12 2315.41 2316.99 2318.52 2326.71 2340.45  2347.7
  2272.5  2272.5  2272.5  2272.5  2272.5  2272.5  2272.5  2272.5  2272.5  2272.5
  2272.5  2272.5  2272.5  2272.5  2272.5  2272.5  2272.5  2272.5  2272.5  2272.5
  2272.5  2272.5  2272.5  2272.5  2272.5  2272.5  2272.5  2272.5  2272.5  2272.5
  2272.5  2272.5  2272.5  2272.5  2272.5  2272.5    2308    2308  2272.5  2272.5
  2272.5  2272.5  2272.5  2272.5  2272.5  2272.5  2272.5  2272.5  2272.5  2272.5
  2272.5  2272.5  2272.5  2272.5  2272.5  2272.5  2272.5  2272.5  2272.5  2272.5
Pier Skew, UpSta & Num, DnSta & Num=  ,5000, 2 ,5000, 2 , 0 , 0 , 0 ,0,0
       1       1
  2292.5    2308
       1       1
 2292.25    2308
BR Coef= 1 , 1 , 0 ,1.25, 0 ,,,0.8,0,2,0,
WSPro=,,,, 1 ,,,, 0 ,,,, 0 ,,,,-1 ,-1 ,-1 , 0 , 0 , 0 , 0 , 0
BC Design=,, 0 ,, 0 ,,,,,,
BC HTab HWMax=2347.07

Type RM Length L Ch R = 1 ,26475   ,327,327,327
BEGIN DESCRIPTION:
XS 84
END DESCRIPTION:
XS GIS Cut Line= 6
       1047835.2       851207.15      1047776.96       851240.87
      1047697.27       851191.82      1047635.96       851204.09
      1047459.71       851369.61      1047390.75        851449.3
#Sta/Elev= 30
  4742.4 2344.67  4767.5 2341.91  4781.3 2339.36  4833.9  2335.7  4836.5 2334.27
  4848.4 2333.26  4876.7 2328.33    4891 2328.32  4903.3 2329.73  4909.6 2328.21
    4926 2322.09  4941.1 2318.61  4954.8 2308.46  4965.8  2303.7  4968.4 2302.73
    4990 2299.59    5010 2299.59  5017.1 2301.84  5030.4 2303.33  5045.8 2305.37
  5060.3 2304.89    5100 2307.78  5167.3 2306.58  5180.9 2308.76  5197.5 2312.94
  5227.7 2312.65  5240.6 2313.33  5279.2 2317.42    5289 2327.35  5313.1 2345.38
#Mann= 3 ,-1 , 0
  4742.4     .09       0  4965.8     .05       0  5030.4     .09       0
#XS Ineff= 3 ,-1
    4900  4942.5    2312 5050.16    5075 2309.78    5075    5300    2320
Permanent Ineff=
       F       F       F
Bank Sta=4965.8,5030.4
Exp/Cntr=0.5,0.3

Type RM Length L Ch R = 1 ,26148   ,286,286,286
BEGIN DESCRIPTION:
XS 83
END DESCRIPTION:
XS GIS Cut Line= 4
      1047424.11       850940.62      1047356.34       851028.72
      1047339.39         851127.      1047230.95       851265.94
#Sta/Elev= 30
  4827.1 2333.49  4840.4 2329.79  4854.6 2328.87  4863.6 2326.42  4872.8 2325.39
  4893.1 2320.84  4915.4 2316.57  4927.3 2310.78  4938.3 2307.62  4950.6 2307.18
  4960.2 2305.01  4969.2 2301.05  4971.5 2299.92  4984.8 2296.13  5014.7 2296.13
    5038 2301.17  5049.8 2303.05    5065 2303.57  5077.4 2304.56    5107 2309.97
  5109.2  2310.7    5133 2311.13  5144.3 2309.97  5151.7 2312.54  5161.4 2315.17
  5172.3 2319.78  5179.3 2319.93  5189.2 2322.83    5210 2330.56  5214.2 2332.62
#Mann= 3 ,-1 , 0
  4827.1     .09       0  4969.2     .05       0    5038     .09       0
Bank Sta=4969.2,5038
Exp/Cntr=0.3,0.1

Type RM Length L Ch R = 1 ,25862   ,357,357,357
BEGIN DESCRIPTION:
XS 82
END DESCRIPTION:
XS GIS Cut Line= 4
      1047251.28        850794.9      1047176.73       850883.01
      1047088.62       850940.62      1047010.68       851025.34
#Sta/Elev= 30
  4825.9 2343.29  4839.8 2333.47  4857.6 2319.23  4861.2 2317.32    4866 2315.87
  4874.8 2312.82  4883.9 2311.83  4893.6 2310.41  4903.5 2309.33  4923.5  2306.6
  4935.9  2300.6  4946.7 2300.63  4955.7 2299.77  4957.9 2299.69  4960.9 2298.95
    4973 2296.67  4974.9 2296.16  4982.4 2294.71    5017 2294.71  5025.1 2298.81
  5043.1 2301.92  5052.1 2307.47  5063.2 2312.27  5064.1 2312.54    5083 2313.23
  5094.1 2314.92  5101.8 2317.72  5124.3  2327.6  5131.4 2331.24  5161.8 2356.87
#Mann= 3 ,-1 , 0
  4825.9     .09       0  4960.9     .05       0  5025.1     .09       0
Bank Sta=4960.9,5025.1
Exp/Cntr=0.3,0.1

Type RM Length L Ch R = 1 ,25505   ,433,433,433
BEGIN DESCRIPTION:
XS 81
END DESCRIPTION:
XS GIS Cut Line= 4
       1047034.4       850527.18      1046956.46       850601.74
      1046881.91       850649.18      1046749.74       850744.07
#Sta/Elev= 30
  4849.9 2353.12  4866.3 2344.06  4881.1 2335.17    4891  2330.1  4906.6 2314.25
  4909.3 2312.21  4917.7 2307.44  4936.5 2306.55  4943.1 2305.35  4956.3 2302.11
  4964.1 2298.87  4969.8 2296.67  4973.3 2296.42  4981.3    2294  5015.3    2294
  5027.1 2296.53  5046.1 2298.83  5056.4  2299.8  5077.3  2306.5  5085.3    2310
  5096.1 2310.89  5106.9 2310.91  5111.3 2312.01  5116.6 2318.01  5123.1 2322.38
  5128.1 2327.08  5145.2 2337.12  5172.1 2356.86  5185.1  2367.2  5208.8 2384.08
#Mann= 3 ,-1 , 0
  4849.9     .09       0  4964.1     .05       0  5046.1     .09       0
Bank Sta=4964.1,5046.1
Exp/Cntr=0.5,0.3

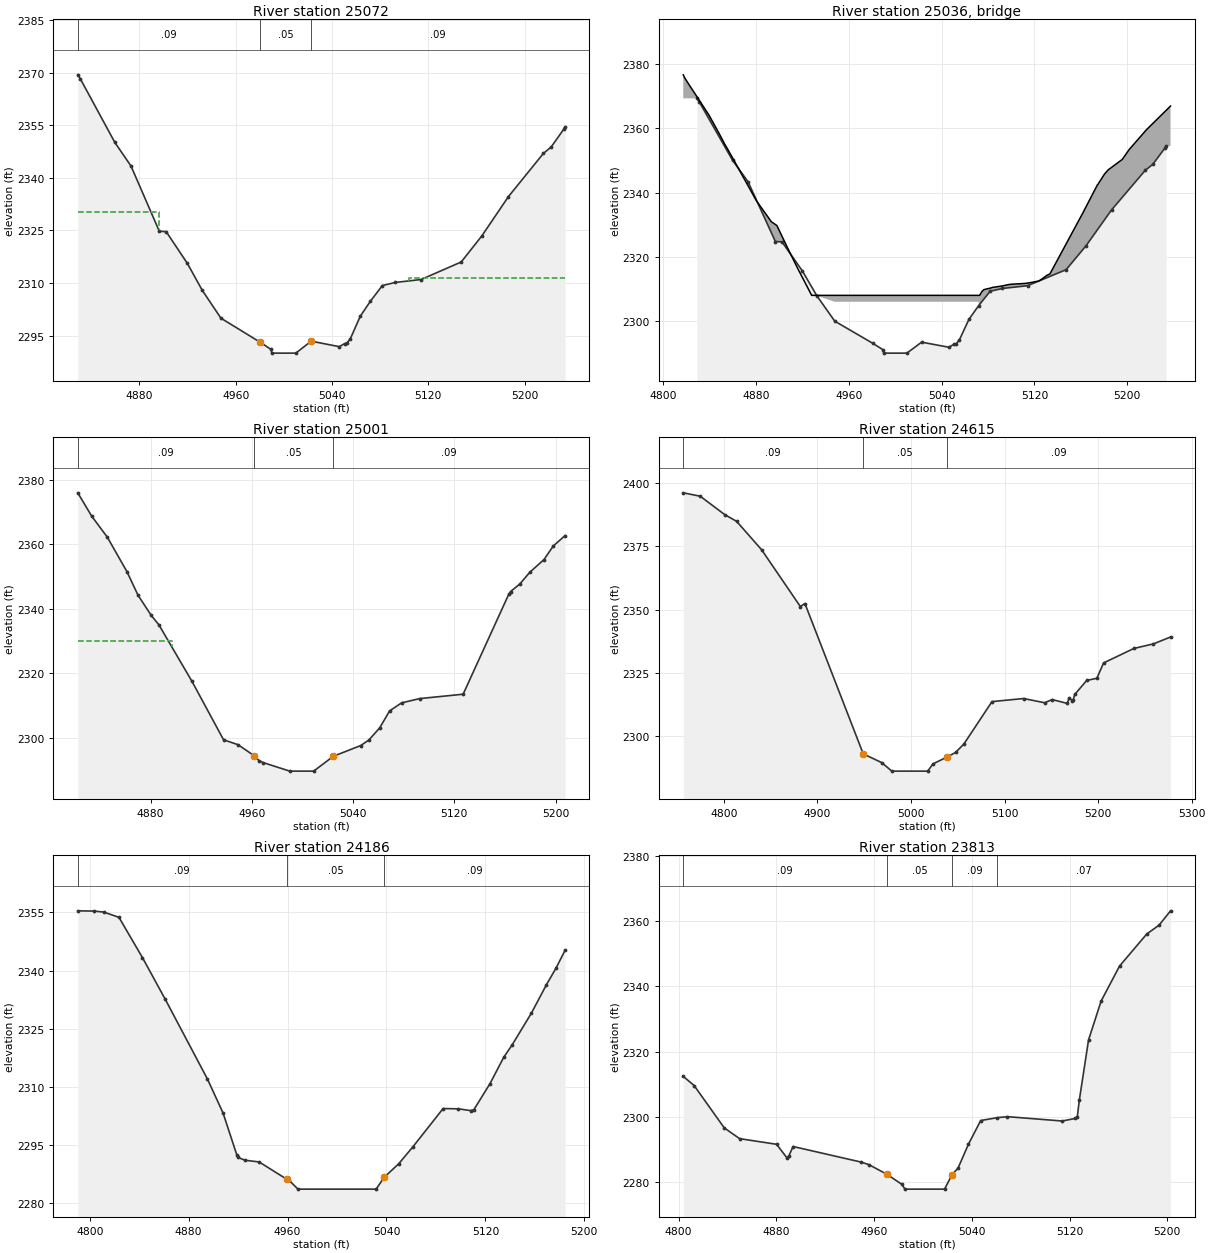
Type RM Length L Ch R = 1 ,25072   ,71,71,71
BEGIN DESCRIPTION:
XS 80
END DESCRIPTION:
XS GIS Cut Line= 4
      1046796.25       850181.08      1046692.04        850257.1
      1046578.01       850334.34      1046451.73       850389.51
#Sta/Elev= 30
  4828.9 2369.39  4830.9 2368.33  4859.7 2350.09  4873.1 2343.37  4896.6 2324.77
  4902.3 2324.66  4919.9  2315.6  4932.3  2307.9  4947.8 2299.96  4980.5 2293.08
  4989.4 2291.06    4990    2290    5010    2290  5022.7 2293.42  5046.1 2291.84
  5050.6 2292.74  5052.3 2292.82  5055.3 2294.15  5063.5 2300.53  5071.9 2304.81
  5081.8 2309.27  5092.4 2310.15    5114    2311  5147.3    2316  5164.5 2323.47
  5186.5 2334.64  5215.6 2346.99    5222  2348.8  5232.5  2353.9  5233.5 2354.55
#Mann= 3 ,-1 , 0
  4828.9     .09       0  4980.5     .05       0  5022.7     .09       0
#XS Ineff= 2 , 0
       0    4896 2330.23    5104       0 2311.55
Permanent Ineff=
       F       F
Bank Sta=4980.5,5022.7
Exp/Cntr=0.5,0.3

Type RM Length L Ch R = 3 ,25036   ,,,
BEGIN DESCRIPTION:
XS 79 TOR
Structure ID: XS 79
Approximate Survey Structure
END DESCRIPTION:
Bridge Culvert--1,0,-1,-1, 0
Deck Dist Width WeirC Skew NumUp NumDn MinLoCord MaxHiCord MaxSubmerge Is_Ogee
32,8,3,0, 48, 48, , , , 0, 1,1,,
  4817.2  4818.1  4819.8  4821.6  4839.4  4848.2  4852.9  4855.3  4880.3  4880.9
  4893.1  4897.9    4907  4916.4  4927.9    4928    4928    5072    5072  5072.7
  5072.8  5074.8  5076.5  5083.1  5083.6  5085.1  5089.1  5092.4  5097.5  5100.1
  5111.6  5115.9  5122.6  5123.9  5127.4  5130.7  5133.3  5161.4  5174.2  5174.7
  5180.4  5183.6  5194.5  5195.6  5201.7  5201.9  5216.6  5237.3
 2376.72    2376 2374.99 2373.97 2364.14 2358.38 2355.13 2353.68 2337.44 2337.15
 2330.95 2329.76 2322.89    2316    2308    2308    2308    2308    2308    2308
 2308.04 2309.26  2309.8 2310.37 2310.48 2310.54 2310.76 2310.95 2311.35 2311.47
 2311.71 2311.93 2312.39  2312.5 2313.34 2314.24 2314.67 2333.47 2342.39 2342.59
 2345.81 2347.11 2350.04 2350.31 2353.46 2353.54 2359.63 2366.99
    2270    2270    2270    2270    2270    2270    2270    2270    2270    2270
    2270    2270    2270    2270    2270    2270    2306    2306    2270    2270
    2270    2270    2270    2270    2270    2270    2270    2270    2270    2270
    2270    2270    2270    2270    2270    2270    2270    2270    2270    2270
    2270    2270    2270    2270    2270    2270    2270    2270
  4817.2  4818.1  4819.8  4821.6  4839.4  4848.2  4852.9  4855.3  4880.3  4880.9
  4893.1  4897.9    4907  4916.4  4927.9    4928    4928    5072    5072  5072.7
  5072.8  5074.8  5076.5  5083.1  5083.6  5085.1  5089.1  5092.4  5097.5  5100.1
  5111.6  5115.9  5122.6  5123.9  5127.4  5130.7  5133.3  5161.4  5174.2  5174.7
  5180.4  5183.6  5194.5  5195.6  5201.7  5201.9  5216.6  5237.3
 2376.72    2376 2374.99 2373.97 2364.14 2358.38 2355.13 2353.68 2337.44 2337.15
 2330.95 2329.76 2322.89    2316    2308    2308    2308    2308    2308    2308
 2308.04 2309.26  2309.8 2310.37 2310.48 2310.54 2310.76 2310.95 2311.35 2311.47
 2311.71 2311.93 2312.39  2312.5 2313.34 2314.24 2314.67 2333.47 2342.39 2342.59
 2345.81 2347.11 2350.04 2350.31 2353.46 2353.54 2359.63 2366.99
    2270    2270    2270    2270    2270    2270    2270    2270    2270    2270
    2270    2270    2270    2270    2270    2270    2306    2306    2270    2270
    2270    2270    2270    2270    2270    2270    2270    2270    2270    2270
    2270    2270    2270    2270    2270    2270    2270    2270    2270    2270
    2270    2270    2270    2270    2270    2270    2270    2270
Abutment Skew #Up #Dn= , 2 , 2
    4928    4980
    2306 2293.07
    4928  4947.1
    2306 2298.85
Abutment Skew #Up #Dn= , 2 , 2
  5028.6    5072
 2293.27    2306
  5047.6    5072
  2298.5    2306
BR Coef= 1 , 1 , 0 ,1.25, 0 ,,,0.8,0,2,0,
WSPro=,,,, 1 ,,,, 0 ,,,, 0 ,,,,-1 ,-1 ,-1 , 0 , 0 , 0 , 0 , 0
BC Design=,, 0 ,, 0 ,,,,,,
BC HTab HWMax=2369.39

Type RM Length L Ch R = 1 ,25001   ,386,386,386
BEGIN DESCRIPTION:
XS 78
END DESCRIPTION:
XS GIS Cut Line= 4
       1046765.6       850130.81      1046662.61       850194.57
      1046541.23       850269.36      1046434.56       850326.98
#Sta/Elev= 30
  4822.5 2375.94  4833.5 2368.71  4845.8 2362.23  4861.4  2351.5  4870.1 2344.23
  4880.6 2337.95  4886.6 2335.06  4912.8 2317.51  4937.7 2299.45  4949.1 2297.94
  4961.9 2294.52  4965.8 2292.97  4969.1 2292.38    4990 2289.75  5008.9 2289.75
  5024.4 2294.34    5046 2297.66  5052.6 2299.41  5061.1 2303.17  5068.9  2308.4
  5078.4  2310.9  5092.8 2312.22    5127 2313.57  5163.1 2344.56  5164.5 2345.37
  5171.7 2347.67  5179.8 2351.38  5190.9 2355.27  5198.2 2359.46  5207.5 2362.69
#Mann= 3 ,-1 , 0
  4822.5     .09       0  4961.9     .05       0  5024.4     .09       0
#XS Ineff= 2 , 0
       0    4897 2329.98    5103       0 2311.53
Permanent Ineff=
       F       F
Bank Sta=4961.9,5024.4
Exp/Cntr=0.5,0.3

Type RM Length L Ch R = 1 ,24615   ,429,429,429
BEGIN DESCRIPTION:
XS 77
END DESCRIPTION:
XS GIS Cut Line= 5
      1046488.76       849744.39      1046408.44       849895.58
      1046315.98       849974.81      1046219.45       850037.33
      1046124.95       850098.75
#Sta/Elev= 30
  4756.7 2396.17  4774.8 2394.83    4801 2387.55  4813.7  2384.9  4840.4 2373.67
  4881.8 2351.22  4886.7  2352.4    4949 2292.97  4968.7 2289.52  4979.6 2286.14
  5017.9 2286.14  5023.6 2289.01  5038.1 2291.62  5047.7 2293.52  5056.6 2296.87
  5086.6 2313.62  5120.4 2314.85  5142.9 2313.17  5150.9 2314.44  5167.2 2312.91
  5168.9 2315.06  5172.4 2314.03  5173.5 2314.44    5175 2316.44  5187.8 2321.98
  5198.7 2322.86  5205.9 2328.92  5238.3 2334.65  5259.1 2336.44  5277.4 2339.16
#Mann= 3 ,-1 , 0
  4756.7     .09       0    4949     .05       0  5038.1     .09       0
Bank Sta=4949,5038.1
Exp/Cntr=0.3,0.1

Type RM Length L Ch R = 1 ,24186   ,373,373,373
BEGIN DESCRIPTION:
XS 76
END DESCRIPTION:
XS GIS Cut Line= 3
      1046282.09       849530.88      1046149.93       849557.99
      1045950.13       849723.13
#Sta/Elev= 30
  4790.3  2355.4  4803.5 2355.33  4811.4 2355.07  4823.6 2353.72  4842.6 2343.34
    4861 2332.61  4895.2 2311.99  4907.8 2303.25  4918.9 2292.47  4919.8 2291.79
  4925.7 2291.05    4937 2290.61  4959.3 2286.16  4960.8 2286.01  4968.4  2283.6
  5031.6  2283.6  5038.3 2286.71  5049.8 2290.11  5061.3 2294.49  5085.8 2304.39
  5098.1 2304.32    5108 2303.86  5110.6 2304.05  5123.7  2310.8  5134.9 2317.65
  5141.6 2320.79  5157.2    2329  5169.4 2336.35    5177 2340.54  5184.4 2345.19
#Mann= 3 , 0 , 0
  4790.3     .09       0  4959.3     .05       0  5038.3     .09       0
Bank Sta=4959.3,5038.3
Exp/Cntr=0.3,0.1

Type RM Length L Ch R = 1 ,23813   ,380,380,380
BEGIN DESCRIPTION:
XS 75
END DESCRIPTION:
XS GIS Cut Line= 4
      1046048.26       849168.28      1045990.66       849246.22
      1045872.05         849314.      1045756.83       849432.61
#Sta/Elev= 30
  4803.8  2312.4  4812.7 2309.59  4837.3 2296.63  4849.9 2293.31  4880.2 2291.58
  4888.7  2287.4  4890.2 2287.98  4893.7  2290.9  4949.2 2286.14  4955.7 2285.35
  4970.6 2282.37  4982.7  2279.3  4985.3 2277.83  5017.7 2277.83  5023.9 2282.31
  5028.7 2284.24  5037.3 2291.63  5047.3 2298.87    5061 2299.75  5069.2 2300.05
    5114 2298.72  5124.7 2299.49  5126.4 2300.04    5128 2305.01  5135.6 2323.59
  5145.9 2335.51    5161 2346.25  5183.2 2356.04  5193.4  2358.8  5202.7 2363.17
#Mann= 4 ,-1 , 0
  4803.8     .09       0  4970.6     .05       0  5023.9     .09       0
    5061     .07       0
Bank Sta=4970.6,5023.9
Exp/Cntr=0.5,0.3