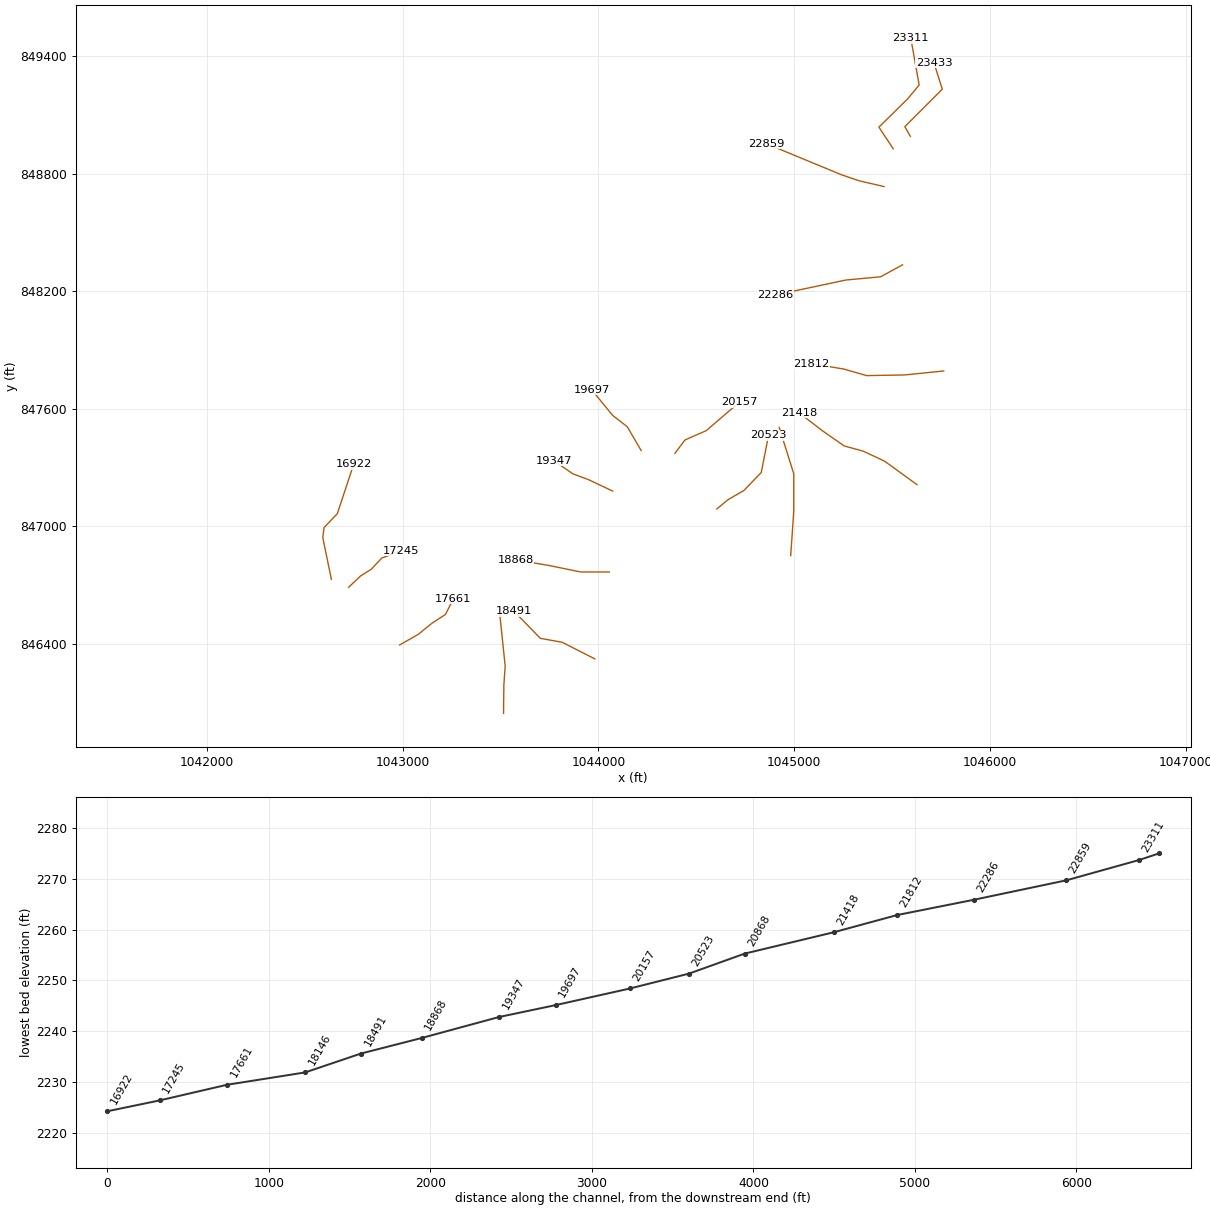
HEC-RAS study lds_big_rock_crk.prj: Big Rock Creek Limited Detail Study

--- lds_big_rock_crk.g01 (geometry) --- (continued)

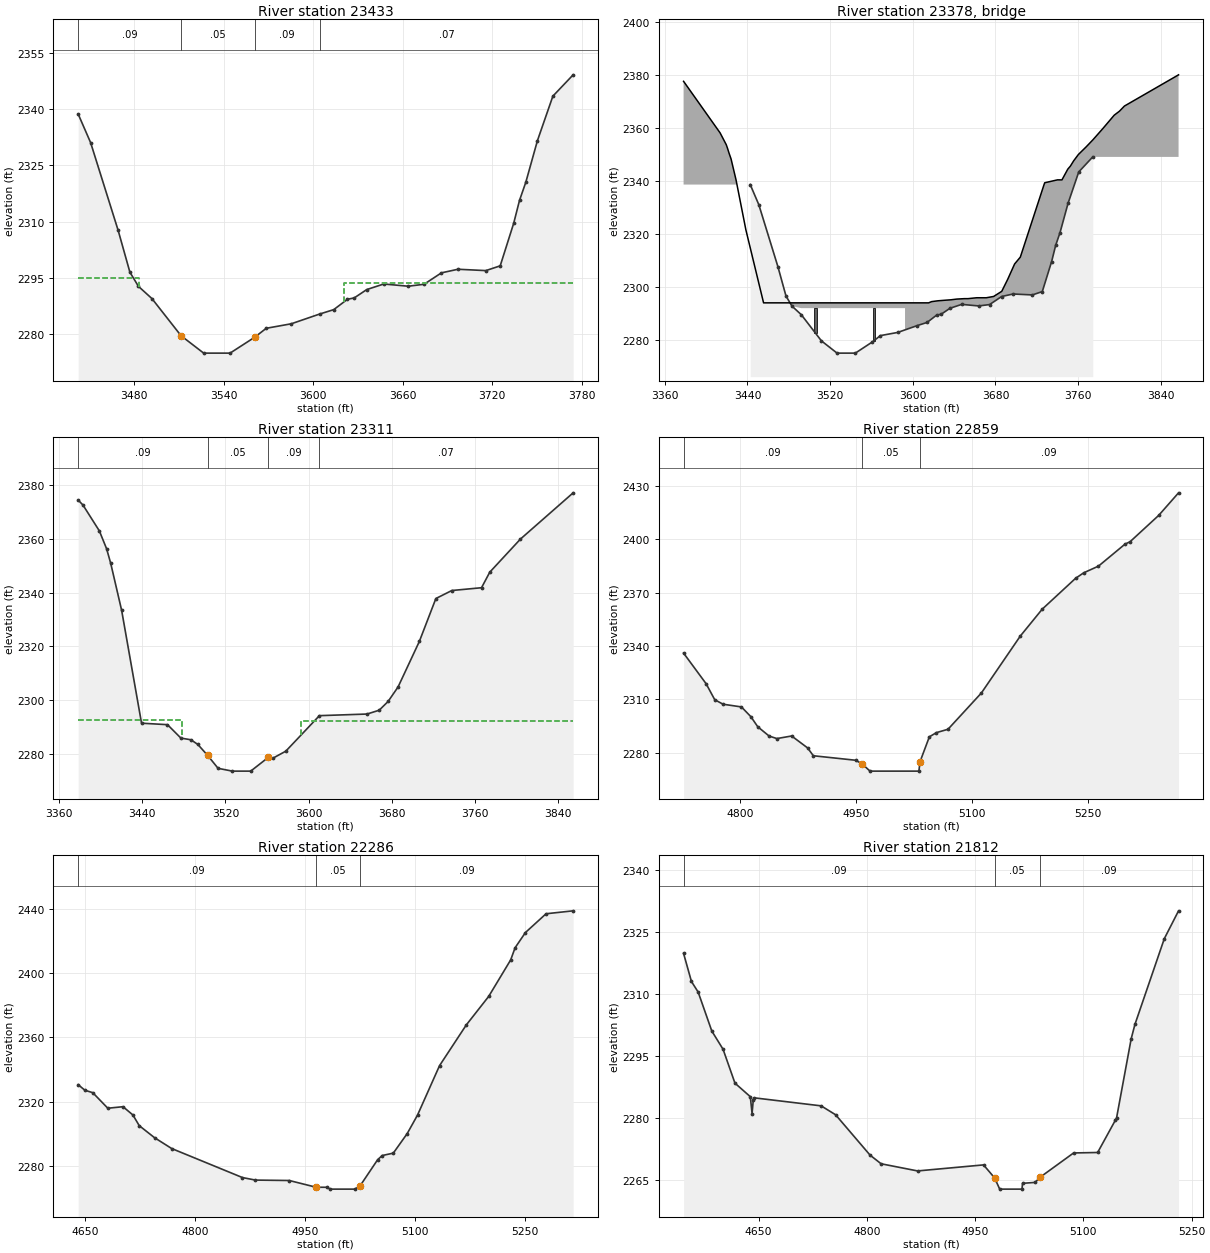
Type RM Length L Ch R = 1 ,23433   ,122,122,122
BEGIN DESCRIPTION:
XS 74
END DESCRIPTION:
XS GIS Cut Line= 5
       1045593.4       848990.77      1045565.05       849040.38
      1045702.07        849177.4      1045756.41       849231.74
      1045713.88        849366.4
#Sta/Elev= 30
 3442.62 2338.713450.964 2331.093469.419 2307.693477.268 2296.573482.996 2292.79
3492.047 2289.533511.563 2279.633526.695    22753544.373    22753560.778 2279.21
3568.626 2281.623585.385 2282.823604.335 2285.413613.811 2286.593623.003 2289.35
3627.529 2289.713635.943 2291.943647.327 2293.423663.732 2292.833674.339 2293.35
3685.936 2296.393697.037 2297.353715.705 2296.993725.321 2298.263734.372 2309.62
3738.261 2315.713742.504 2320.573750.282 2331.653760.606 2343.483774.182 2349.16
#Mann= 4 ,-1 , 0
 3442.62     .09       03511.563     .05       03560.778     .09       0
3604.335     .07       0
#XS Ineff= 2 , 0
       0 3483.67    2295    3621       0 2293.56
Permanent Ineff=
       F       T
Bank Sta=3511.563,3560.778
Skew Angle= 45
Exp/Cntr=0.5,0.3

Type RM Length L Ch R = 3 ,23378   ,,,
BEGIN DESCRIPTION:
XS 73 TOR
Structure ID: XS 73 tor
Approximate Survey Structure
END DESCRIPTION:
Bridge Culvert--1,0,-1,-1, 0
Deck Dist Width WeirC Skew NumUp NumDn MinLoCord MaxHiCord MaxSubmerge Is_Ogee
35,40,3,45, 42, 42, , , , 0, 1,1,,
3378.1323413.4873419.427  3420.73422.1143424.0943428.9023438.448 3455.563478.612
3478.6123592.4563592.4563615.2953618.1243624.2763637.145 3642.663649.8733653.338
3661.8233671.1573678.2283686.0773691.8753698.5223704.0373726.8063727.6553740.029
3744.3423749.9993752.4743755.6563760.2523767.6773774.2533783.799  3794.93800.062
  3804.83857.197
 2377.73 2358.24 2353.79 2352.38 2350.62  2348.4 2340.49 2321.57    2294    2294
    2294    2294    2294    2294 2294.46 2294.78 2295.17 2295.43 2295.59 2295.59
 2295.93 2295.93 2296.42 2298.36 2302.93  2308.7 2311.28 2338.45 2339.39 2340.49
 2340.48 2344.54 2345.67 2347.67 2350.07 2352.92  2355.6 2359.82 2364.92 2366.46
 2368.38 2380.18
    2255    2255    2255    2255    2255    2255    2255    2255    2255    2255
    2292    2292    2255    2255    2255    2255    2255    2255    2255    2255
    2255    2255    2255    2255    2255    2255    2255    2255    2255    2255
    2255    2255    2255    2255    2255    2255    2255    2255    2255    2255
    2255    2255
3378.1323413.4873419.427  3420.73422.1143424.0943428.9023438.448 3455.563478.612
3478.6123592.4563592.4563615.2953618.1243624.2763637.145 3642.663649.8733653.338
3661.8233671.1573678.2283686.0773691.8753698.5223704.0373726.8063727.6553740.029
3744.3423749.9993752.4743755.6563760.2523767.6773774.2533783.799  3794.93800.062
  3804.83857.197
 2377.73 2358.24 2353.79 2352.38 2350.62  2348.4 2340.49 2321.57    2294    2294
    2294    2294    2294    2294 2294.46 2294.78 2295.17 2295.43 2295.59 2295.59
 2295.93 2295.93 2296.42 2298.36 2302.93  2308.7 2311.28 2338.45 2339.39 2340.49
 2340.48 2344.54 2345.67 2347.67 2350.07 2352.92  2355.6 2359.82 2364.92 2366.46
 2368.38 2380.18
    2255    2255    2255    2255    2255    2255    2255    2255    2255    2255
    2292    2292    2255    2255    2255    2255    2255    2255    2255    2255
    2255    2255    2255    2255    2255    2255    2255    2255    2255    2255
    2255    2255    2255    2255    2255    2255    2255    2255    2255    2255
    2255    2255
Pier Skew, UpSta & Num, DnSta & Num=  ,3505.835, 2 ,3503.007, 2 , 0 , 0 , 0 ,,
       2       2
    2279    2292
       2       2
    2279    2292
Pier Skew, UpSta & Num, DnSta & Num=  ,3562.404, 2 ,3558.868, 2 , 0 , 0 , 0 ,,
       2       2
  2277.5    2292
       2       2
  2277.5    2292
BR Coef= 1 , 1 , 0 ,1.25, 0 ,,,0.8,0,2,0,
WSPro=,,,, 1 ,,,, 0 ,,,, 0 ,,,,-1 ,-1 ,-1 , 0 , 0 , 0 , 0 , 0
BC Design=,, 0 ,, 0 ,,,,,,
BC HTab HWMax=2349.16

Type RM Length L Ch R = 1 ,23311   ,452,452,452
BEGIN DESCRIPTION:
XS 72
END DESCRIPTION:
XS GIS Cut Line= 5
      1045505.99       848926.98      1045432.76       849038.02
      1045579.23       849182.13      1045638.29         849253.
      1045595.76       849491.61
#Sta/Elev= 30
3378.415 2374.383383.082  2372.5 3398.78 2362.93 3405.78 2356.27 3409.74 2350.84
3420.205 2333.453439.367 2291.513464.328 2290.963477.198 2285.983486.885 2285.35
3493.532 2283.61 3502.97 2279.533512.977 2274.753526.695 2273.713544.373 2273.71
3561.202  2278.83565.586 2278.493578.102 2281.123610.417 2294.313656.237 2294.91
3667.904 2296.33 3676.46 2299.573686.077 2304.973706.512 2321.853722.422 2337.81
3737.766 2340.783766.333 2341.823774.253 2347.593803.739 2359.883854.439 2377.06
#Mann= 4 ,-1 , 0
3378.415     .09       0 3502.97     .05       03561.202     .09       0
3610.417     .07       0
#XS Ineff= 2 , 0
       0 3478.33 2292.62 3592.53       0 2292.43
Permanent Ineff=
       T       T
Bank Sta=3502.97,3561.202
Skew Angle= 45
Exp/Cntr=0.5,0.3

Type RM Length L Ch R = 1 ,22859   ,573,573,573
BEGIN DESCRIPTION:
XS 71
END DESCRIPTION:
XS GIS Cut Line= 4
      1045458.62       848734.52      1045331.17       848763.98
       1045241.4       848794.69      1044858.68       848952.97
#Sta/Elev= 30
  4727.4    2336  4756.5 2318.82  4767.7  2309.8  4778.5 2307.28  4802.2 2305.76
  4814.4 2300.28  4823.3 2294.61    4838  2289.4    4848 2287.99  4867.1 2289.44
  4887.8 2282.71  4895.1 2278.34  4949.8 2275.81 4958.17 2273.78  4968.4  2269.7
  5031.6  2269.7 5032.98 2274.93  5045.1 2288.97  5054.2 2291.33  5069.2 2293.21
  5112.3 2313.57  5162.7  2345.6    5191 2360.69    5234 2377.97  5244.6  2381.1
  5263.7 2384.86    5298 2397.21  5304.5 2398.55  5341.5 2413.34  5367.2 2426.03
#Mann= 3 , 0 , 0
  4727.4     .09       0 4958.17     .05       0 5032.98     .09       0
Bank Sta=4958.17,5032.98
Exp/Cntr=0.3,0.1

Type RM Length L Ch R = 1 ,22286   ,474,474,474
BEGIN DESCRIPTION:
XS 70
END DESCRIPTION:
XS GIS Cut Line= 4
       1045553.5       848334.64      1045441.67       848273.64
      1045262.07        848256.7      1044903.57       848180.45
#Sta/Elev= 30
  4641.1 2330.71  4650.2 2327.25    4661 2325.72  4681.5 2316.07  4702.2 2317.02
  4715.7 2311.87  4724.3 2305.26  4745.1  2297.8  4768.5 2291.06  4864.9 2273.05
  4882.6 2271.48  4928.7 2271.22  4965.2 2267.05  4979.9 2267.01  4984.4 2265.87
  5017.9 2265.87  5024.9 2267.73  5049.1 2284.15  5055.3 2286.72  5070.4 2288.21
  5089.3  2300.3  5103.4 2311.82  5133.4  2342.5  5169.8 2367.73  5200.3 2385.43
  5230.3 2408.11  5236.3 2415.64  5250.4  2425.1  5278.5 2436.75  5315.4 2438.57
#Mann= 3 , 0 , 0
  4641.1     .09       0  4965.2     .05       0  5024.9     .09       0
Bank Sta=4965.2,5024.9
Exp/Cntr=0.3,0.1

Type RM Length L Ch R = 1 ,21812   ,394,394,394
BEGIN DESCRIPTION:
XS 69
END DESCRIPTION:
XS GIS Cut Line= 5
      1045763.61       847792.44      1045563.67        847772.1
      1045370.51       847768.71       1045251.9        847802.6
      1045085.85       847829.71
#Sta/Elev= 30
    4546 2319.88  4556.9 2313.09  4566.2 2310.53  4585.1 2301.11  4600.7  2296.7
  4617.2  2288.5  4638.5 2285.22  4640.9 2281.13  4642.6 2284.54  4643.8 2284.95
  4736.6 2283.01  4756.6 2280.86  4804.4 2271.09  4819.7    2269  4870.2 2267.27
  4961.6 2268.73    4977 2265.57    4984 2262.87  5014.9 2262.87  5015.6 2264.27
  5033.1  2264.5  5039.7 2265.71  5086.4 2271.62  5119.7 2271.73  5144.2 2279.52
    5146 2280.17  5166.2 2299.26  5171.4 2302.73  5212.1 2323.46  5231.8 2330.18
#Mann= 3 ,-1 , 0
    4546     .09       0    4977     .05       0  5039.7     .09       0
Bank Sta=4977,5039.7
Exp/Cntr=0.3,0.1

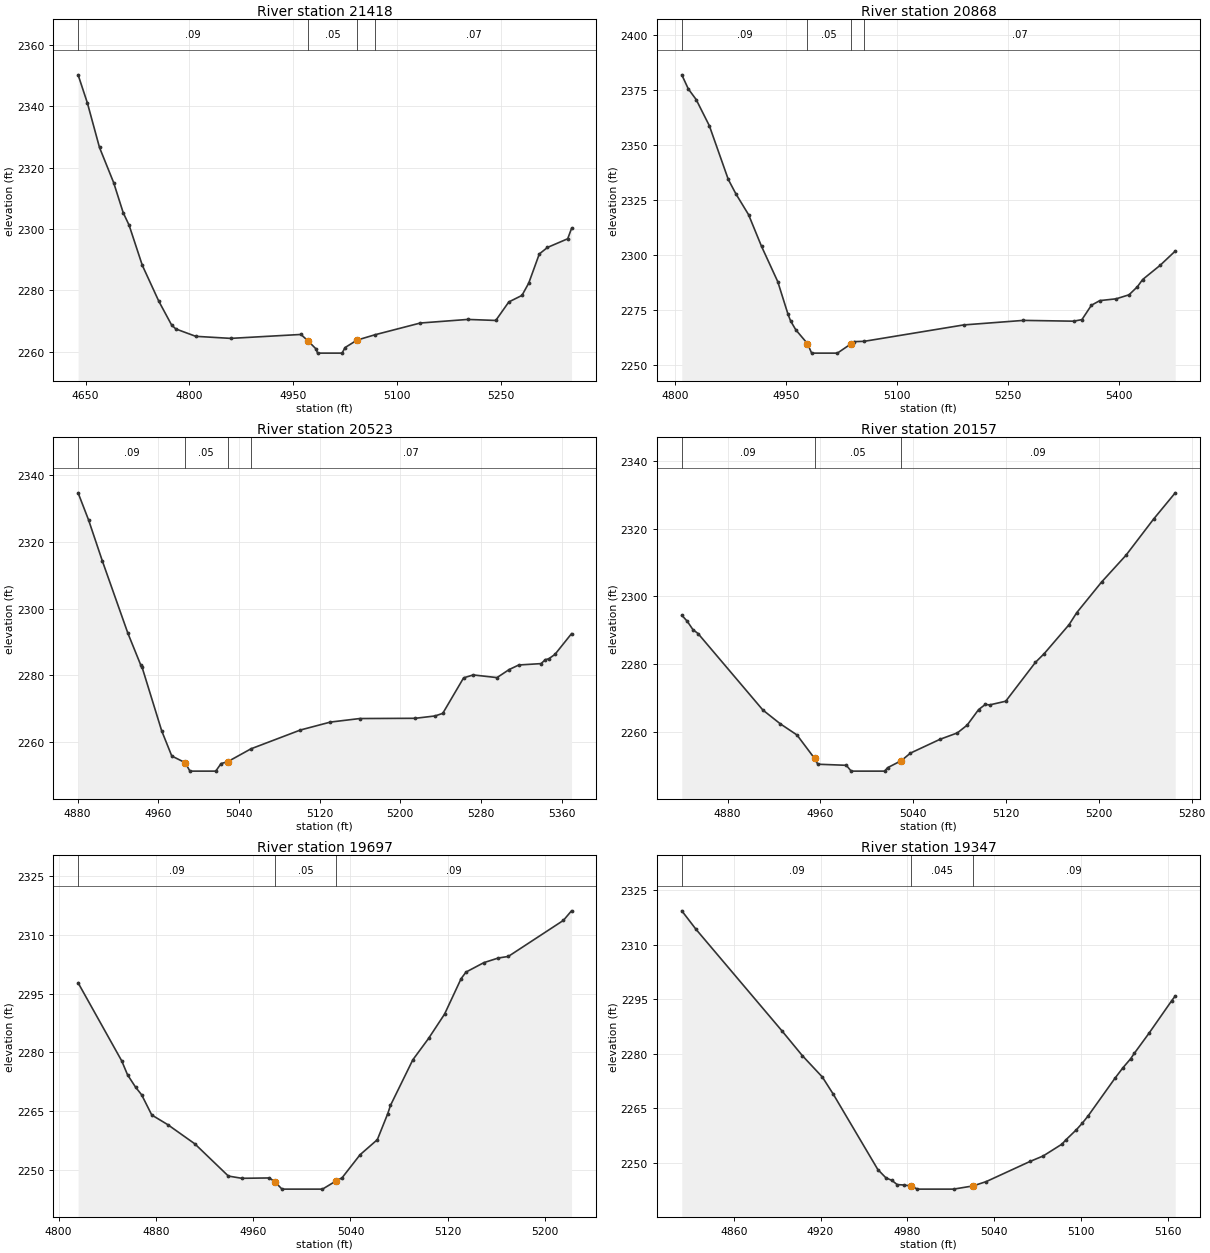
Type RM Length L Ch R = 1 ,21418   ,550,550,550
BEGIN DESCRIPTION:
XS 68
END DESCRIPTION:
XS GIS Cut Line= 6
      1045627.18       847211.62        1045462.       847331.56
      1045353.56       847382.39      1045255.29        847409.5
      1045143.46       847487.44      1045024.85       847578.94
#Sta/Elev= 30
  4639.3 2350.24  4652.7 2341.07  4670.2 2326.54  4690.6 2315.09  4704.4 2305.27
  4712.9  2301.2    4732 2288.09  4755.8 2276.39  4774.3 2268.62  4780.4 2267.35
  4809.1 2264.95  4859.5 2264.28  4960.9 2265.56  4970.7 2263.54  4982.7 2260.83
  4984.8 2259.47  5020.2 2259.47  5024.5 2261.28  5041.8 2263.72  5068.2 2265.49
  5133.1 2269.29  5201.5 2270.46    5242 2270.13  5260.8 2276.16  5279.8  2278.3
  5289.6 2282.33  5304.8 2291.81  5316.6 2293.94  5345.8 2296.77  5351.3 2300.14
#Mann= 4 ,-1 , 0
  4639.3     .09       0  4970.7     .05       0  5041.8     .09       0
  5068.2     .07       0
Bank Sta=4970.7,5041.8
Exp/Cntr=0.3,0.1

Type RM Length L Ch R = 1 ,20868   ,345,345,345
BEGIN DESCRIPTION:
XS 67
END DESCRIPTION:
XS GIS Cut Line= 4
      1044982.14       846848.94      1044997.74        847077.4
      1044997.74       847267.17      1044923.19       847504.39
#Sta/Elev= 30
  4808.7 2381.95  4817.5 2375.54  4828.1 2370.71  4845.9 2358.82  4871.6 2334.31
  4881.9 2327.75    4899  2318.3  4916.5 2303.91  4938.5  2287.8  4952.4 2272.92
  4955.9  2269.9  4962.9 2265.88  4978.7  2259.6  4984.3 2255.28  5019.1 2255.28
  5037.7 2259.53  5041.8 2260.51  5055.3 2260.65  5189.9 2268.11  5270.8 2270.18
  5338.7 2269.82  5349.9 2270.54  5362.7 2277.07  5374.1 2279.19  5396.2    2280
  5413.6 2281.83  5424.9 2285.49    5432 2288.78  5455.6 2295.23  5476.1 2301.73
#Mann= 4 ,-1 , 0
  4808.7     .09       0  4978.7     .05       0  5037.7     .09       0
  5055.3     .07       0
Bank Sta=4978.7,5037.7
Exp/Cntr=0.3,0.1

Type RM Length L Ch R = 1 ,20523   ,366,366,366
BEGIN DESCRIPTION:
XS 66
END DESCRIPTION:
XS GIS Cut Line= 5
      1044604.64       847087.57      1044662.25       847135.01
      1044743.58       847182.45      1044831.69       847273.95
      1044868.97       847463.72
#Sta/Elev= 30
  4880.5 2334.69  4890.9 2326.56  4904.7 2314.16  4929.9 2292.62  4942.6 2283.14
    4944 2282.41  4963.4 2263.41  4973.4 2255.87 4986.71 2253.87  4991.4 2251.34
    5017 2251.34 5022.29 2253.61 5028.72 2254.14    5052 2258.03    5101 2263.66
  5130.7 2266.03  5159.8 2267.09  5214.7 2267.16  5234.4 2267.86  5242.1 2268.64
  5262.8 2279.28  5272.3 2280.15  5295.9 2279.35    5308 2281.77  5317.5 2283.13
  5339.6 2283.54  5343.8 2284.72  5347.2 2284.99  5353.3 2286.28  5369.8 2292.51
#Mann= 4 ,-1 , 0
  4880.5     .09       0 4986.07     .05       0 5028.72     .09       0
    5052     .07       0
Bank Sta=4986.71,5028.72
Exp/Cntr=0.3,0.1

Type RM Length L Ch R = 1 ,20157   ,460,460,460
BEGIN DESCRIPTION:
XS 65
END DESCRIPTION:
XS GIS Cut Line= 4
      1044391.15       847372.23      1044441.98         847440.
      1044550.42       847487.44      1044719.06       847632.13
#Sta/Elev= 30
  4840.5 2294.46  4845.1 2292.72  4850.1 2290.21  4854.5 2289.05  4910.4 2266.45
  4925.3 2262.41  4939.8 2259.08 4954.92 2252.17  4957.7 2250.45  4982.3 2250.13
  4986.5 2248.41  5015.3 2248.41  5017.8 2249.41  5029.7  2251.5  5037.6 2253.74
  5063.1 2257.82    5078  2259.7  5086.4 2261.98  5096.3 2266.58  5102.1 2268.11
  5105.8 2267.97  5119.7 2269.06  5145.3 2280.54  5152.9 2283.13  5174.3 2291.68
  5180.9 2295.22  5202.3 2304.26  5223.3 2312.16  5247.1 2322.85  5265.8 2330.62
#Mann= 3 , 0 , 0
  4840.5     .09       0 4954.92     .05       0  5029.7     .09       0
Bank Sta=4954.92,5029.7
Exp/Cntr=0.3,0.1

Type RM Length L Ch R = 1 ,19697   ,350,350,350
BEGIN DESCRIPTION:
XS 64
END DESCRIPTION:
XS GIS Cut Line= 4
      1044218.32       847385.78      1044147.16       847507.78
       1044072.6       847565.39       1043964.6       847697.15
#Sta/Elev= 30
    4816 2297.75  4851.9 2277.83  4856.7 2274.27  4863.3 2271.13  4868.3 2269.17
  4876.6 2264.04  4889.7 2261.59    4912 2256.69  4939.6 2248.47  4950.7  2247.9
 4973.34 2247.99 4977.82 2247.01  4983.7 2245.14    5017 2245.14    5028  2247.2
  5033.1 2248.03  5047.9 2253.91  5062.1 2257.75  5070.7 2264.41  5072.9 2266.49
  5091.3 2278.12  5104.2 2283.55  5117.4 2289.77    5131 2298.81    5135 2300.48
  5149.7 2302.89  5161.6 2304.07  5169.8 2304.47  5215.1 2313.66  5221.8  2316.1
#Mann= 3 , 0 , 0
    4816     .09       0 4977.82     .05       0    5028     .09       0
Bank Sta=4977.82,5028
Exp/Cntr=0.3,0.1

Type RM Length L Ch R = 1 ,19347   ,479,479,479
BEGIN DESCRIPTION:
XS 63
END DESCRIPTION:
XS GIS Cut Line= 4
       1044072.6       847179.07      1043950.61       847236.67
      1043869.28       847267.17        1043771.       847334.95
#Sta/Elev= 30
  4824.1 2319.29  4833.8 2314.27  4893.5 2286.22  4907.4  2279.5  4921.3 2273.59
  4928.8  2268.9  4959.6 2248.19  4965.2  2245.9  4969.3 2245.21    4973 2244.04
  4977.5 2243.94  4982.8 2243.64    4987  2242.8    5012  2242.8  5025.5 2243.69
 5034.53 2244.87    5065 2250.44  5073.9 2251.91  5086.9 2255.17  5089.5  2256.3
  5096.9 2259.14  5100.9 2260.91  5104.9 2262.88  5123.5 2273.26  5129.1 2276.19
  5134.3  2278.6  5136.9 2280.12  5147.1 2285.67  5162.7 2294.56  5165.2 2295.88
#Mann= 3 , 0 , 0
  4824.1     .09       0  4982.8    .045       0  5025.5     .09       0
Bank Sta=4982.8,5025.5
Exp/Cntr=0.3,0.1

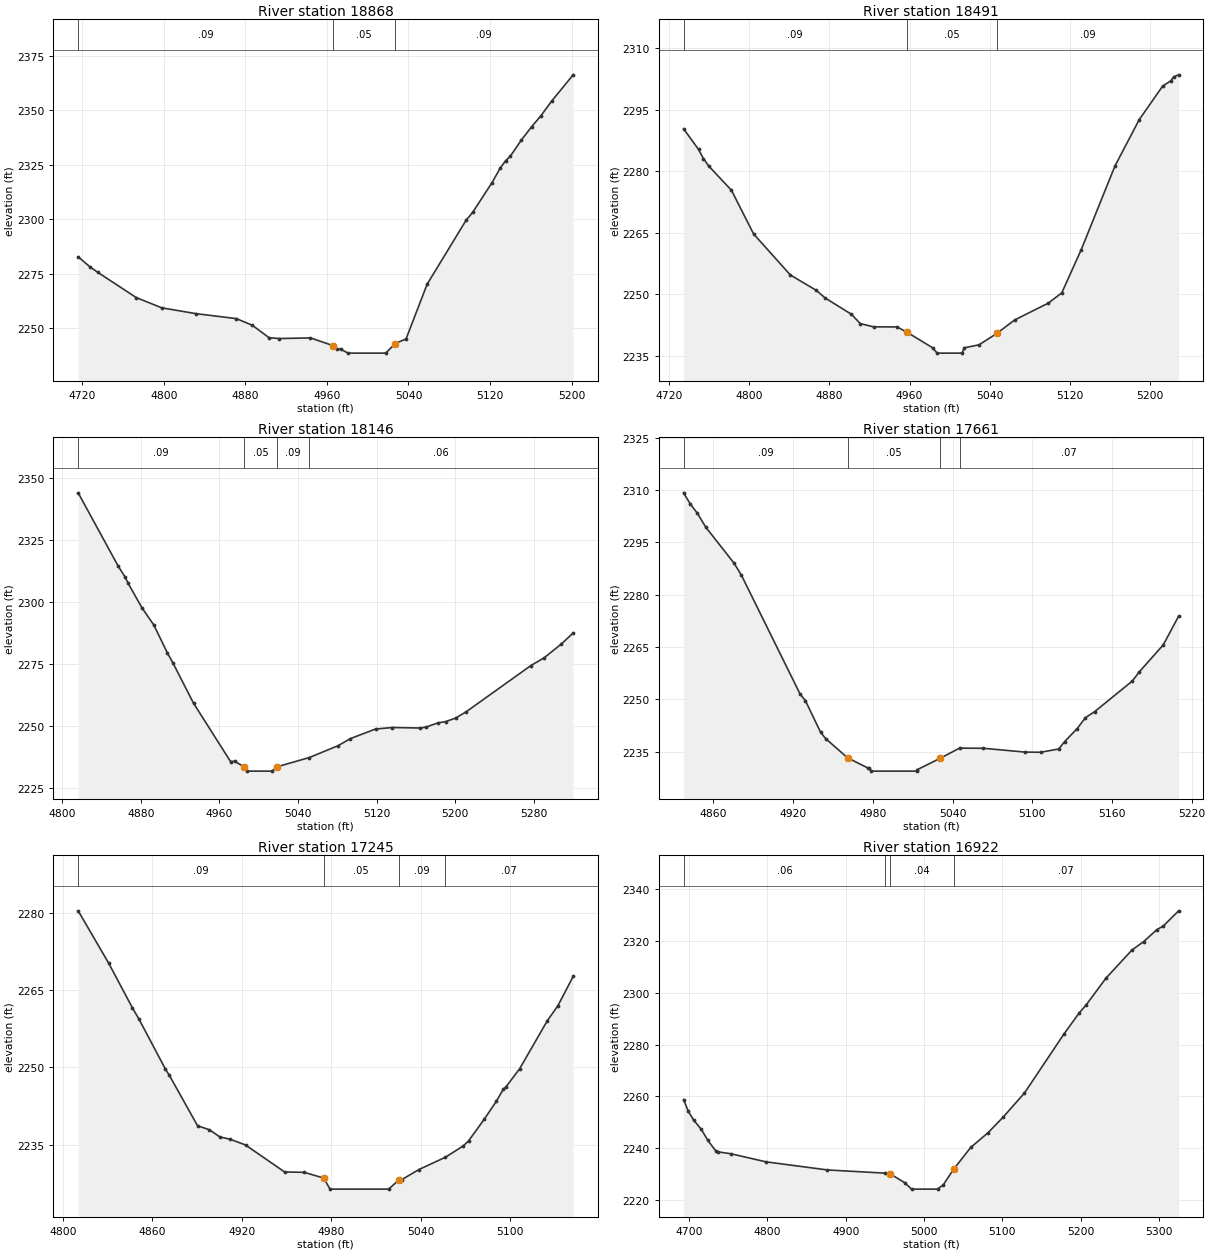
Type RM Length L Ch R = 1 ,18868   ,377,377,377
BEGIN DESCRIPTION:
XS 62
END DESCRIPTION:
XS GIS Cut Line= 4
      1044055.66       846765.63      1043909.94       846765.63
      1043743.89       846799.52      1043576.02       846827.77
#Sta/Elev= 30
  4716.1 2282.78  4727.6 2278.24  4735.5 2275.62  4773.1 2264.11    4798 2259.43
  4831.7 2256.75  4871.3 2254.48    4887  2251.4  4903.2 2245.76  4913.3 2245.35
  4943.9 2245.65 4966.04 2242.11    4970 2240.65  4973.4 2240.52  4980.7 2238.67
  5017.6 2238.67 5027.09 2243.07  5037.6 2245.16  5058.3 2270.24  5096.5 2299.55
    5103 2303.18  5121.9 2316.77  5129.8 2323.29  5135.4 2326.91  5139.7 2328.75
  5150.7 2336.29  5160.8 2342.42  5169.5 2347.18  5180.7  2354.3  5201.5 2366.16
#Mann= 3 , 0 , 0
  4716.1     .09       0 4966.04     .05       0 5027.09     .09       0
Bank Sta=4966.04,5027.09
Exp/Cntr=0.3,0.1

Type RM Length L Ch R = 1 ,18491   ,345,345,345
BEGIN DESCRIPTION:
XS 61
END DESCRIPTION:
XS GIS Cut Line= 4
      1043981.41       846321.68      1043815.06       846406.42
      1043703.23       846426.75      1043567.67        846565.7
#Sta/Elev= 30
  4734.3 2290.35  4749.2 2285.33  4754.1 2283.09  4759.3 2281.29  4782.1 2275.35
  4804.2  2264.7  4840.9 2254.68  4866.4 2250.99  4875.7 2249.06  4901.8  2245.1
  4910.8  2242.8    4924 2242.02  4947.5 2241.99 4957.36 2240.71  4983.1 2236.89
  4987.5  2235.6  5012.4  2235.6  5014.6  2236.9  5029.3 2237.62 5047.29 2240.43
  5064.9 2243.69  5098.6 2247.81    5112 2250.31  5131.4 2260.84  5165.1 2281.26
  5189.3 2292.57  5212.7 2300.76    5221 2302.09  5223.8 2303.05  5228.7 2303.53
#Mann= 3 , 0 , 0
  4734.3     .09       0 4957.36     .05       0 5047.29     .09       0
Bank Sta=4957.36,5047.29
Exp/Cntr=0.3,0.1

Type RM Length L Ch R = 1 ,18146   ,485,485,485
BEGIN DESCRIPTION:
XS 60
END DESCRIPTION:
XS GIS Cut Line= 4
      1043515.17       846043.35      1043516.84       846189.54
      1043523.62       846284.43      1043496.51       846545.36
#Sta/Elev= 30
  4816.2 2344.04  4857.1 2314.38  4863.9 2310.14  4867.1 2307.54    4881 2297.79
  4893.3 2290.71  4906.9 2279.58  4912.6 2275.52  4933.6 2259.25  4971.3 2235.72
  4975.3 2235.87  4985.2 2233.63  4987.6 2231.89  5013.7 2231.89  5018.4 2233.62
  5051.3 2237.35  5080.6 2242.13  5093.3 2245.01  5118.8 2248.86    5136 2249.47
  5164.5 2249.26  5170.3 2249.65  5182.2 2251.33  5190.2 2251.85  5200.5 2253.31
  5211.3 2255.88  5276.6 2274.36  5290.4 2277.56  5307.7 2283.06  5319.9 2287.57
#Mann= 4 ,-1 , 0
  4816.2     .09       0  4985.2     .05       0  5018.4     .09       0
  5051.3     .06       0
Bank Sta=4985.2,5018.4
Exp/Cntr=0.3,0.1

Type RM Length L Ch R = 1 ,17661   ,416,416,416
BEGIN DESCRIPTION:
XS 59
END DESCRIPTION:
XS GIS Cut Line= 5
       1042984.8       846392.87      1043079.69       846447.09
      1043150.85        846504.7      1043218.63       846548.75
      1043259.29       846630.08
#Sta/Elev= 30
  4837.5 2309.16  4842.4 2306.04  4847.8 2303.33  4854.3 2299.26  4875.6 2288.95
    4881 2285.58  4925.2  2251.5  4929.2 2249.63  4940.6 2240.59  4944.5 2238.73
  4960.9 2233.27  4976.3 2230.33  4977.3 2230.31  4978.7 2229.45    5013 2229.45
  5013.2 2229.83  5030.8 2233.17  5045.2 2236.03  5063.1    2236  5094.2 2234.91
  5106.3 2234.85  5119.9  2235.8  5124.3 2237.91  5133.8 2241.65  5139.9 2244.73
    5147 2246.52  5175.3 2255.27  5180.3 2257.79  5198.6 2265.64  5210.1 2273.84
#Mann= 4 ,-1 , 0
  4837.5     .09       0  4960.9     .05       0  5030.8     .09       0
  5045.2     .07       0
#XS Ineff= 2 , 0
       0                    5075       0
Permanent Ineff=
       F       T
Bank Sta=4960.9,5030.8
Exp/Cntr=0.3,0.1

Type RM Length L Ch R = 1 ,17245   ,323,323,323
BEGIN DESCRIPTION:
XS 58
END DESCRIPTION:
XS GIS Cut Line= 5
      1042723.87       846687.69      1042784.86        846745.3
      1042839.09       846779.19      1042893.31        846836.8
      1042991.58       846874.07
#Sta/Elev= 30
  4810.3 2280.38  4830.8 2270.21  4846.7 2261.55  4851.1 2259.37  4868.8 2249.69
  4871.3 2248.55  4890.4 2238.68  4898.4 2237.89  4905.4  2236.5  4912.3 2236.06
  4922.6 2234.94  4948.8 2229.71  4961.9 2229.64    4975 2228.53  4979.3 2226.38
  5018.6 2226.38  5025.3 2228.12  5027.4 2228.22  5038.9 2230.18  5056.7 2232.57
  5068.6 2234.75  5072.2 2235.73  5082.8 2239.97  5090.8  2243.4  5095.5 2245.75
  5097.4 2246.25  5106.5 2249.74    5125 2259.03  5132.1 2261.94  5142.4 2267.65
#Mann= 4 ,-1 , 0
  4810.3     .09       0    4975     .05       0  5025.3     .09       0
  5056.7     .07       0
Bank Sta=4975,5025.3
Exp/Cntr=0.3,0.1

Type RM Length L Ch R = 1 ,16922   ,492,492,492
BEGIN DESCRIPTION:
XS 57
END DESCRIPTION:
XS GIS Cut Line= 5
      1042635.76       846728.36       1042591.7       846941.85
      1042598.48       846992.68      1042666.26       847063.85
      1042749.41        847314.9
#Sta/Elev= 30
    4693 2258.77  4699.1 2254.19  4705.8 2250.91  4715.6 2247.29  4723.9 2243.07
  4734.3 2238.88  4736.3 2238.65  4753.5 2237.88  4798.2 2234.77  4876.5 2231.65
  4950.6 2230.41  4956.1 2230.23  4975.1 2226.77  4984.1 2224.25  5017.2 2224.25
  5024.7 2225.99  5037.6 2231.87  5059.7 2240.36  5081.8 2246.03  5101.3 2252.12
  5128.2 2261.31  5178.3 2283.93  5197.7 2292.03    5207  2295.3  5232.4 2305.65
  5265.4 2316.43  5280.5 2319.72  5297.1 2324.27  5305.5 2325.72    5325 2331.56
#Mann= 4 ,-1 , 0
    4693     .06       0  4950.6     .07       0  4956.1     .04       0
  5037.6     .07       0
#XS Ineff= 2 , 0
       0    4900                       0
Permanent Ineff=
       T       F
Bank Sta=4956.1,5037.6
Exp/Cntr=0.3,0.1