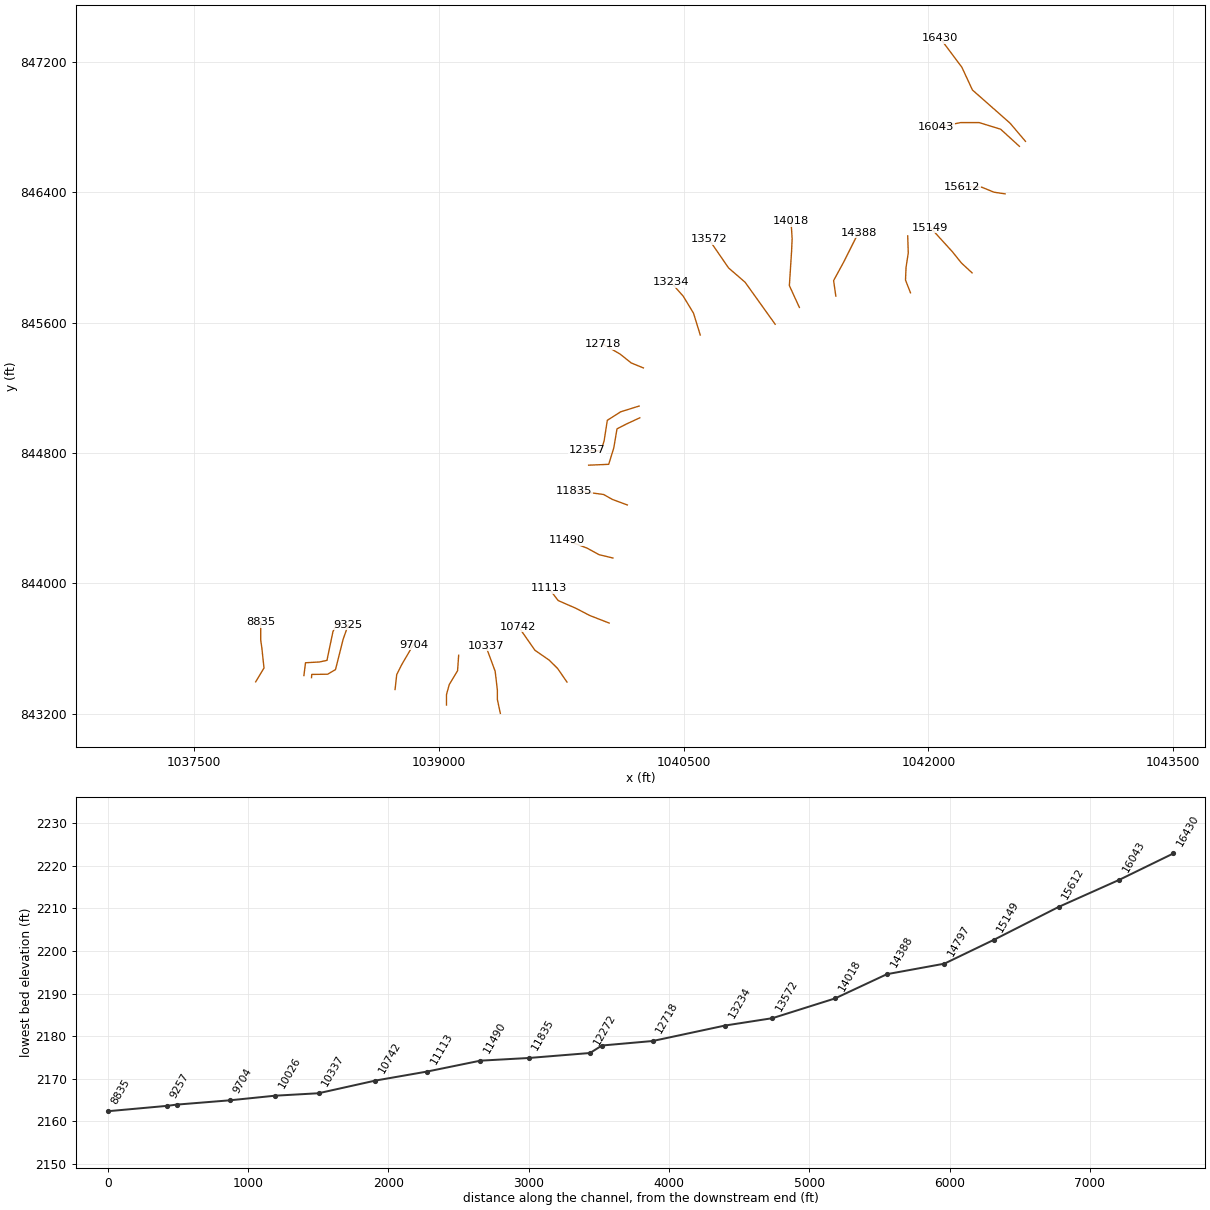
HEC-RAS study lds_big_rock_crk.prj: Big Rock Creek Limited Detail Study

--- lds_big_rock_crk.g01 (geometry) --- (continued)

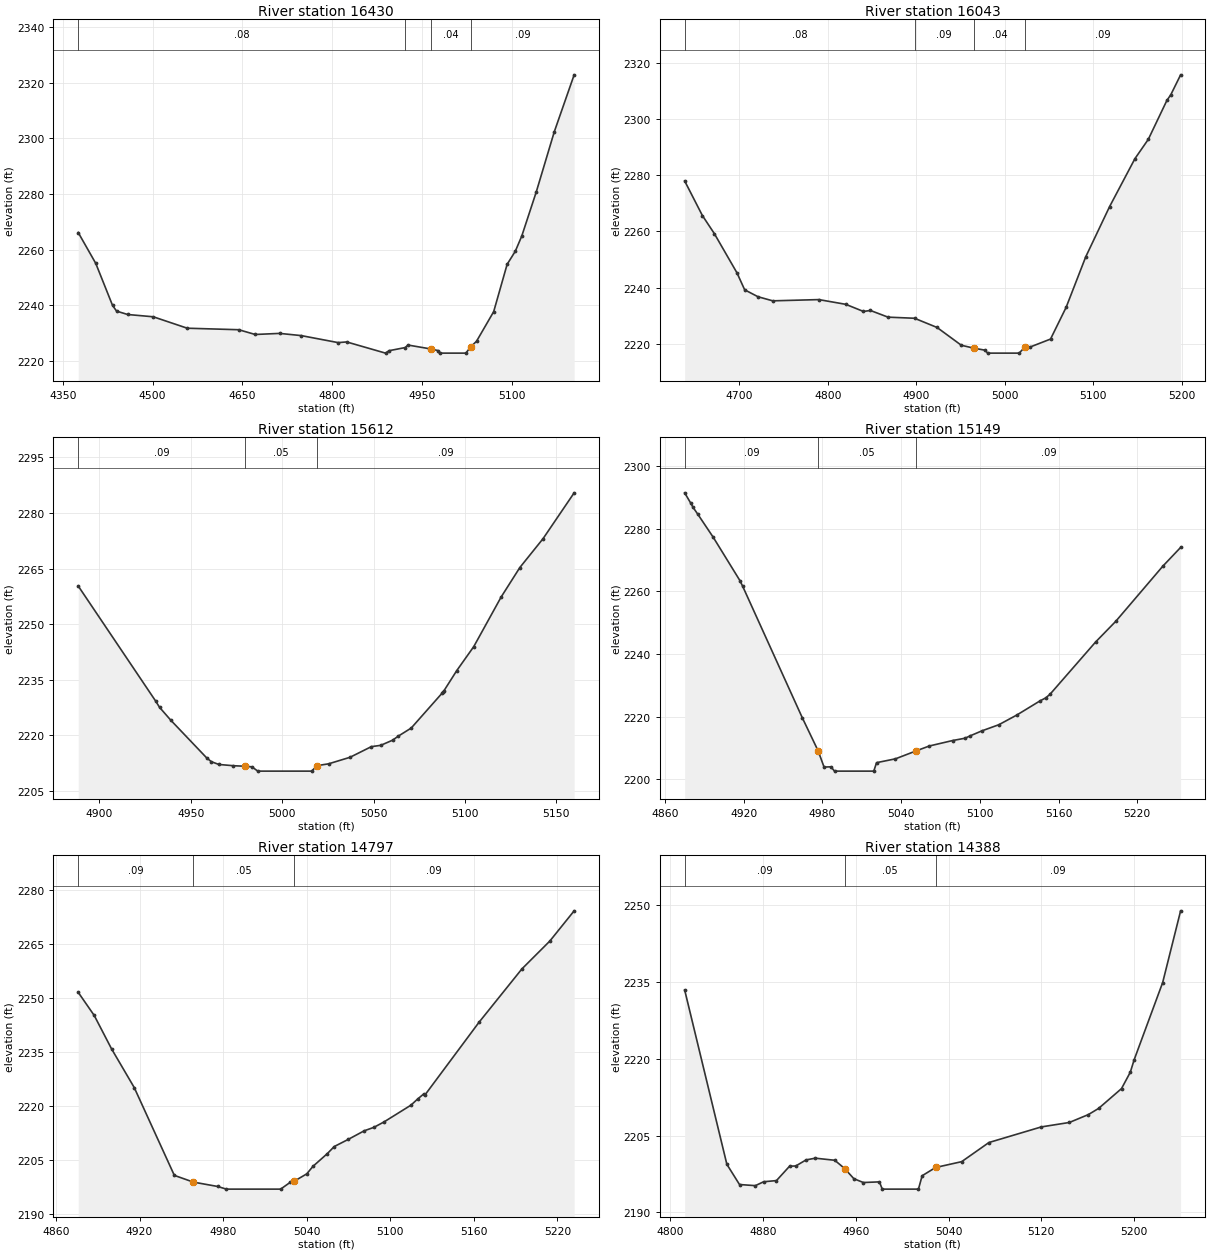
Type RM Length L Ch R = 1 ,16430   ,387,387,387
BEGIN DESCRIPTION:
XS 56
END DESCRIPTION:
XS GIS Cut Line= 5
      1042595.09       846711.41      1042500.21       846823.24
      1042269.77       847026.57      1042205.38       847165.51
      1042072.66       847343.16
#Sta/Elev= 30
  4375.7 2266.21    4405 2255.13  4433.1 2240.01  4439.8 2237.97  4458.3 2236.75
  4501.1 2235.93    4558 2231.82    4644 2231.28  4671.5 2229.57  4712.4 2229.96
  4748.4 2229.17  4810.1 2226.65  4824.4 2226.89  4889.3 2222.87  4895.2 2223.74
  4922.2 2224.87  4926.8 2225.78  4965.3 2224.36  4976.9 2223.79  4979.7 2222.87
  5023.6 2222.87    5032 2225.21  5041.4 2227.12  5070.1 2237.77  5092.6 2254.79
  5106.2 2259.46    5117 2264.91  5141.2 2280.74  5171.4 2302.41  5204.6 2322.87
#Mann= 4 ,-1 , 0
  4375.7     .08       0  4922.2     .09       0  4965.3     .04       0
    5032     .09       0
#XS Ineff= 2 , 0
       0    4750                       0
Permanent Ineff=
       T       F
Bank Sta=4965.3,5032
Exp/Cntr=0.3,0.1

Type RM Length L Ch R = 1 ,16043   ,431,431,431
BEGIN DESCRIPTION:
XS 55
END DESCRIPTION:
XS GIS Cut Line= 5
      1042557.82       846680.91       1042442.6       846785.97
      1042310.43       846826.63       1042198.6       846826.63
      1042047.23       846796.39
#Sta/Elev= 30
  4638.3 2277.93  4658.3 2265.63  4671.8  2259.2  4697.3 2245.28  4706.1 2239.19
  4721.2 2236.72  4737.8 2235.27  4789.9 2235.71  4820.3 2234.03  4840.3 2231.49
  4848.2 2231.84  4868.1 2229.46    4898 2229.07  4923.5 2225.79  4950.9 2219.46
  4965.3 2218.41  4977.8  2217.7  4980.6 2216.66  5016.3 2216.66  5022.5 2218.77
    5029 2218.88  5051.7 2221.66  5069.3 2232.93  5091.5 2250.94  5118.5 2268.84
  5147.1 2285.88  5162.2 2292.75  5183.2  2306.6  5187.6 2308.61  5198.7  2315.7
#Mann= 4 ,-1 , 0
  4638.3     .08       0    4898     .09       0  4965.3     .04       0
  5022.5     .09       0
Bank Sta=4965.3,5022.5
Exp/Cntr=0.3,0.1

Type RM Length L Ch R = 1 ,15612   ,463,463,463
BEGIN DESCRIPTION:
XS 54
END DESCRIPTION:
XS GIS Cut Line= 4
      1042469.71       846389.48      1042401.93       846399.64
      1042327.38       846430.14      1042205.38       846433.53
#Sta/Elev= 29
  4888.5 2260.31  4930.8 2229.27    4933 2227.53  4939.1 2224.08  4958.7 2213.92
  4961.3 2212.87  4965.4 2212.12  4973.4 2211.78  4979.7 2211.64  4983.5 2211.48
  4986.7 2210.32  5016.1 2210.32  5019.2 2211.81  5025.4 2212.29  5037.1 2214.05
  5048.8 2216.93  5053.9 2217.28  5060.4 2218.67  5063.6 2219.79  5070.6 2221.95
  5087.4 2231.32  5088.1 2231.61  5088.4 2231.94  5095.5 2237.46  5104.8 2243.94
  5119.8 2257.35    5130 2265.29  5142.7 2273.09  5159.7 2285.46
#Mann= 3 , 0 , 0
  4888.5     .09       0  4979.7     .05       0  5019.2     .09       0
Bank Sta=4979.7,5019.2
Exp/Cntr=0.3,0.1

Type RM Length L Ch R = 1 ,15149   ,352,352,352
BEGIN DESCRIPTION:
XS 53
END DESCRIPTION:
XS GIS Cut Line= 4
      1042267.64       845904.89      1042201.99       845965.88
      1042147.77       846033.66      1042012.22       846182.76
#Sta/Elev= 30
  4875.1 2291.51  4879.8 2288.15  4881.5 2286.85  4885.1 2284.67  4896.9 2277.28
  4917.2 2263.46  4919.3 2261.64  4964.7 2219.66  4976.8 2209.05  4981.3 2203.88
  4986.5 2203.96  4989.3 2202.58  5019.2 2202.58  5021.3 2205.28  5035.7 2206.51
  5051.4 2209.04  5061.5 2210.61  5079.3 2212.36  5088.8  2213.1  5092.6 2213.85
  5101.7 2215.47  5114.5 2217.41  5128.2 2220.51  5145.8 2225.01  5150.1 2225.96
  5153.4  2227.1  5188.3 2243.88  5203.6 2250.46  5239.5  2268.1    5253 2274.06
#Mann= 3 ,-1 , 0
  4875.1     .09       0  4976.8     .05       0  5051.4     .09       0
Bank Sta=4976.8,5051.4
Exp/Cntr=0.3,0.1

Type RM Length L Ch R = 1 ,14797   ,409,409,409
BEGIN DESCRIPTION:
XS 52
END DESCRIPTION:
XS GIS Cut Line= 5
      1041890.23       845782.89      1041859.73       845860.83
      1041863.12       845938.77      1041876.67       846026.88
      1041873.28       846131.93
#Sta/Elev= 28
    4876 2251.52  4887.5 2245.11  4899.9 2235.88  4916.2 2225.15    4945 2200.81
  4958.6 2198.95  4976.2 2197.73  4982.3    2197  5021.3    2197  5028.1 2198.86
    5030 2198.98  5030.8 2199.14  5040.1 2201.24  5044.5 2203.31  5054.8 2206.83
  5059.8  2208.8  5069.7 2210.75  5081.3 2213.16  5088.2 2214.11  5095.4 2215.59
  5114.8 2220.25  5119.7 2221.98    5124 2223.36  5125.1 2223.19  5163.6 2243.17
  5194.5 2258.01  5214.5 2265.71    5232  2274.1
#Mann= 3 , 0 , 0
    4876     .09       0  4958.6     .05       0  5030.8     .09       0
Bank Sta=4958.6,5030.8
Exp/Cntr=0.3,0.1

Type RM Length L Ch R = 1 ,14388   ,370,370,370
BEGIN DESCRIPTION:
XS 51
END DESCRIPTION:
XS GIS Cut Line= 4
      1041432.74       845762.55      1041419.18       845857.44
      1041483.57       845976.05      1041571.68       846152.26
#Sta/Elev= 30
  4812.3 2233.46  4848.7 2199.39  4859.6 2195.44  4873.3 2195.22  4880.4 2195.98
  4891.5 2196.21  4902.8 2199.02  4908.2 2199.07    4917 2200.25    4925 2200.59
  4941.8 2200.18  4950.3 2198.57  4958.3 2196.57  4966.5 2195.83  4980.3 2195.96
  4982.8 2194.54    5014 2194.54  5017.2 2197.16  5028.8 2198.77  5051.3 2199.91
  5074.8 2203.65    5120  2206.7  5144.2 2207.57  5160.6 2209.11  5169.4 2210.31
  5189.2 2214.19  5196.8  2217.4  5200.1 2219.82  5224.7 2234.91  5240.2 2248.94
#Mann= 3 ,-1 , 0
  4812.3     .09       0  4950.3     .05       0  5028.8     .09       0
#XS Ineff= 2 , 0
       0    4900                       0
Permanent Ineff=
       T       F
Bank Sta=4950.3,5028.8
Exp/Cntr=0.3,0.1

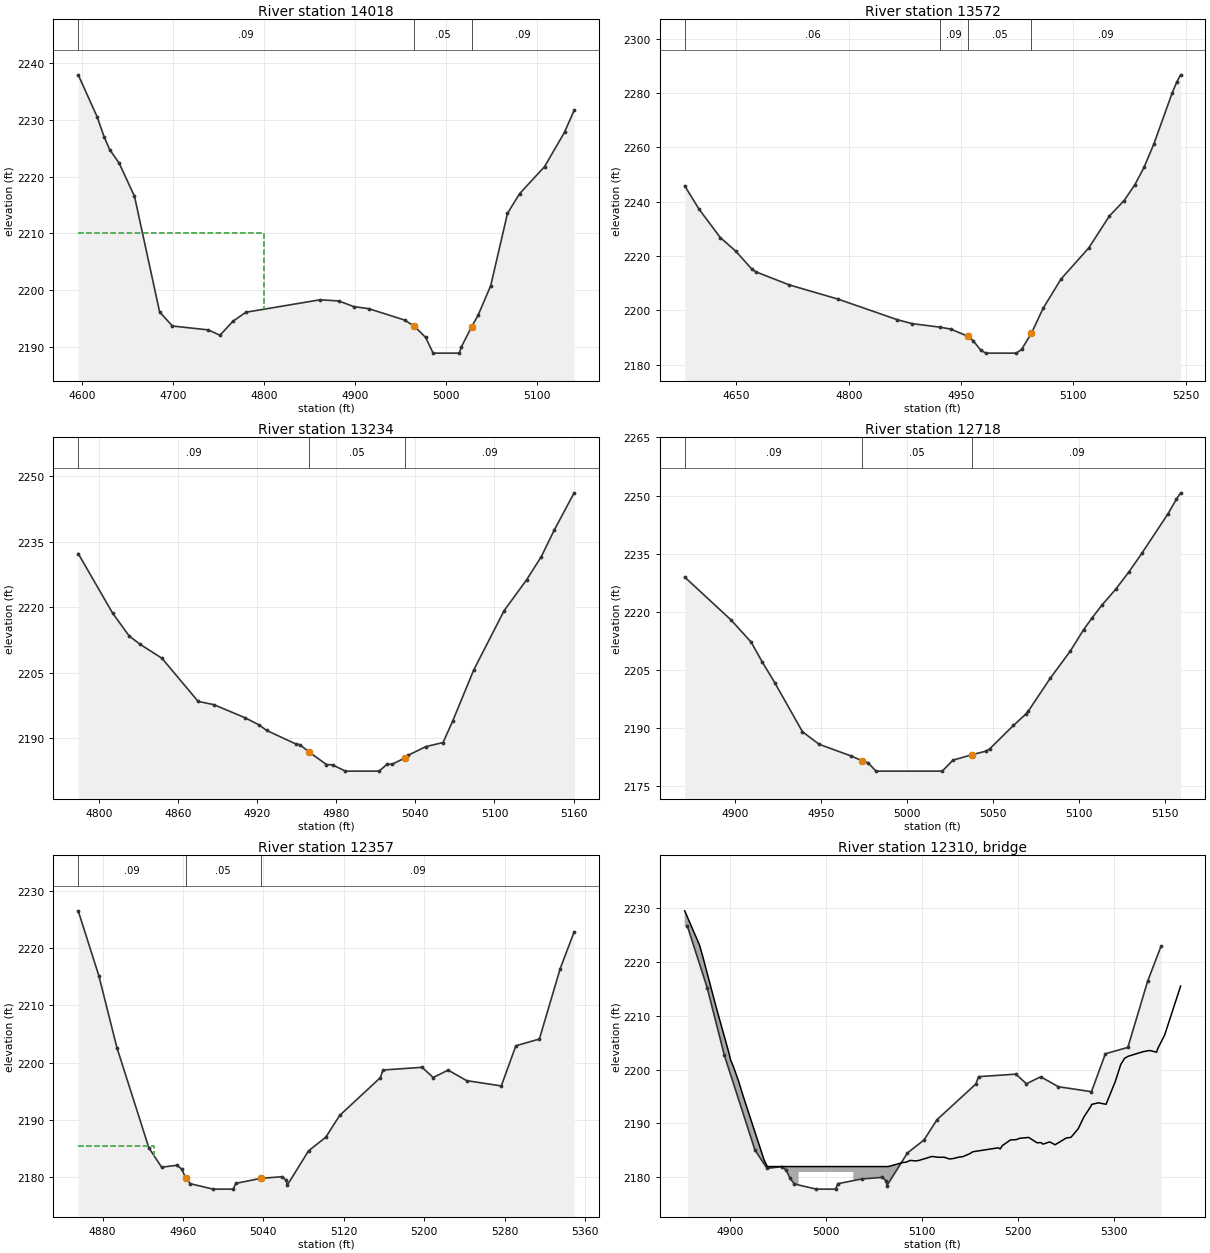
Type RM Length L Ch R = 1 ,14018   ,446,446,446
BEGIN DESCRIPTION:
XS 50
END DESCRIPTION:
XS GIS Cut Line= 5
      1041209.42       845692.96      1041148.08       845826.94
      1041161.64       846037.04      1041165.03       846114.99
      1041158.25       846223.43
#Sta/Elev= 30
  4595.9 2237.98  4616.7 2230.56  4624.4 2227.01  4630.5 2224.77  4640.8  2222.4
  4657.7 2216.54  4685.3 2196.12  4699.3 2193.64  4738.7 2192.95  4751.6 2192.01
  4765.9 2194.49  4780.1 2196.07  4861.6 2198.27    4882 2198.06  4898.2 2197.08
  4915.1 2196.69  4954.3 2194.69    4965  2193.6  4977.5 2191.61  4985.6 2188.85
  5014.4 2188.85  5016.5  2189.9  5027.8 2193.48    5035 2195.53  5048.9 2200.77
  5067.3 2213.53  5080.6    2217    5108 2221.77  5129.9 2227.84  5140.5  2231.7
#Mann= 3 ,-1 , 0
  4595.9     .09       0    4965     .05       0  5027.8     .09       0
#XS Ineff= 2 , 0
       0    4800    2210               0
Permanent Ineff=
       F       F
Bank Sta=4965,5027.8
Exp/Cntr=0.3,0.1

Type RM Length L Ch R = 1 ,13572   ,338,338,338
BEGIN DESCRIPTION:
XS 49
END DESCRIPTION:
XS GIS Cut Line= 4
      1041061.07       845589.83      1040876.98       845847.27
      1040775.32       845935.38      1040655.59       846109.75
#Sta/Elev= 30
  4580.9 2245.87  4600.1 2237.27  4628.5 2226.79  4649.1 2221.81  4670.8 2215.11
  4676.3 2214.14  4720.6 2209.36  4785.9 2204.11  4865.1 2196.52  4884.9 2195.08
  4922.1 2193.78  4936.5 2193.07  4959.7 2190.37  4966.3 2188.78  4976.5 2185.26
  4983.3 2184.22  5023.9 2184.22  5030.9 2185.56    5044  2191.5  5059.8 2200.77
  5083.8 2211.58  5120.7 2222.98  5148.3 2234.76    5168 2240.45  5182.4 2246.33
  5194.5 2252.66  5207.6 2261.24  5231.9 2279.91  5238.2  2284.1  5243.4 2286.76
#Mann= 4 ,-1 , 0
  4580.9     .06       0  4922.1     .09       0  4959.7     .05       0
    5044     .09       0
Bank Sta=4959.7,5044
Exp/Cntr=0.3,0.1

Type RM Length L Ch R = 1 ,13234   ,516,516,516
BEGIN DESCRIPTION:
XS 47
END DESCRIPTION:
XS GIS Cut Line= 4
      1040601.98       845524.18      1040560.71       845657.64
      1040497.42        845762.2      1040421.74       845847.51
#Sta/Elev= 30
  4784.4 2232.27  4810.5 2218.63    4823 2213.42  4831.4 2211.49  4847.9 2208.31
  4875.3 2198.45  4887.2  2197.7  4910.6 2194.74  4921.8 2193.02  4927.2 2191.81
  4949.4  2188.7  4952.5 2188.54  4959.4 2186.87  4972.6    2184  4977.2 2183.92
    4987 2182.49  5012.5 2182.49  5018.5 2184.05  5022.4 2184.07  5032.1  2185.5
  5034.4 2186.09  5047.9  2188.1    5061 2189.03  5068.2 2193.88  5084.3 2205.66
  5107.3  2219.2  5124.4 2226.28  5135.5 2231.57  5145.3 2237.63  5160.4 2246.16
#Mann= 3 ,-1 , 0
  4784.4     .09       0  4959.4     .05       0  5032.1     .09       0
Bank Sta=4959.4,5032.1
Exp/Cntr=0.3,0.1

Type RM Length L Ch R = 1 ,12718   ,361,361,361
BEGIN DESCRIPTION:
XS 45
END DESCRIPTION:
XS GIS Cut Line= 4
      1040253.44       845322.01      1040178.89       845352.51
      1040111.11       845406.73      1040006.06       845467.73
#Sta/Elev= 30
  4870.5 2228.96  4897.5 2217.89  4909.3 2212.12  4915.7 2207.01  4922.9 2201.74
  4939.1 2189.02  4948.8 2185.79  4967.5 2182.76    4974 2181.49  4977.3 2181.02
  4981.9 2178.86  5020.5 2178.86  5026.7 2181.69  5037.9 2183.11    5046 2184.03
  5048.2 2184.64  5061.9 2190.64  5069.1 2193.56  5070.6 2194.35  5083.3 2202.79
  5095.1 2209.88  5102.8 2215.38  5107.9 2218.51  5113.4 2221.68  5121.4 2225.77
  5129.2  2230.3  5136.7 2235.09  5151.9 2245.26  5156.9  2249.1  5159.3 2250.71
#Mann= 3 ,-1 , 0
  4870.5     .09       0    4974     .05       0  5037.9     .09       0
Bank Sta=4974,5037.9
Exp/Cntr=0.5,0.3

Type RM Length L Ch R = 1 ,12357   ,85,85,85
BEGIN DESCRIPTION:
XS 44
END DESCRIPTION:
XS GIS Cut Line= 6
       1040227.5       845088.27      1040114.47       845052.95
      1040032.52       845000.67      1040012.75       844873.52
      1039992.97       844812.77      1039907.79       844817.08
#Sta/Elev= 30
  4855.7 2226.59  4876.2 2215.23  4894.2 2202.62    4926 2185.06  4938.7 2181.65
  4953.8 2181.99  4958.6 2181.35  4962.6 2179.79  4967.2 2178.76    4990 2177.81
    5010 2177.81  5012.5 2178.82  5037.1 2179.69  5058.7 2179.99  5062.8 2179.33
  5063.6 2178.47  5084.9 2184.52  5102.1 2186.92  5115.9 2190.73  5156.3 2197.34
    5159 2198.69  5197.9 2199.16  5208.9 2197.37  5223.8 2198.67  5242.3 2196.82
  5276.7  2195.9  5291.2 2202.94  5314.6 2204.12  5335.3 2216.45  5349.2 2222.91
#Mann= 3 ,-1 , 0
  4855.7     .09       0  4962.6     .05       0  5037.1     .09       0
#XS Ineff= 2 , 0
       0  4931.5 2185.43  5068.5       0
Permanent Ineff=
       F       T
Bank Sta=4962.6,5037.1
Exp/Cntr=0.5,0.3

Type RM Length L Ch R = 3 ,12310   ,,,
BEGIN DESCRIPTION:
XS 43 TOR
Structure ID: XS 43
Approximate Survey Structure
END DESCRIPTION:
Bridge Culvert--1,0,-1,-1, 0
Deck Dist Width WeirC Skew NumUp NumDn MinLoCord MaxHiCord MaxSubmerge Is_Ogee
40,14,3,0, 60, 60, , , , 0, 1,1,,
  4852.8  4868.3  4871.9  4885.7  4898.4  4900.8  4903.5  4909.1  4914.1  4935.5
  4938.9  4971.5  4971.5  5028.5  5028.5    5065  5079.9  5083.9  5087.8  5093.6
  5097.1  5110.6  5116.7  5123.3  5128.7  5132.9  5138.7  5142.4  5149.7  5153.1
  5179.7  5181.6  5183.7  5192.3  5198.3  5201.9  5211.2    5220  5223.9  5226.1
  5233.2  5238.8  5250.5  5255.3  5262.9  5268.8  5276.1  5276.9    5284  5291.9
  5301.5  5307.2  5311.3    5315  5330.5  5337.3  5344.6  5345.8  5352.9  5369.6
 2229.48 2223.11 2220.83 2211.53 2203.42 2201.71  2200.6 2197.78  2194.9 2183.25
    2182    2182    2182    2182    2182    2182 2182.74 2182.83 2183.15 2183.04
 2183.15 2183.88 2183.72 2183.73 2183.41 2183.49 2183.76 2183.83 2184.37 2184.75
 2185.48 2185.26 2185.88 2186.94    2187 2187.25 2187.41 2186.41 2186.46 2186.16
 2186.58 2186.05 2187.31 2187.42 2189.02 2191.21 2193.19 2193.54 2193.84 2193.56
 2197.78 2200.94 2202.12 2202.48 2203.33 2203.55 2203.23 2203.92 2206.39 2215.51
 2157.83 2157.83 2157.83 2157.83 2157.83 2157.83 2157.83 2157.83 2157.83 2157.83
 2157.83 2157.83    2181    2181 2157.83 2157.83 2157.83 2157.83 2157.83 2157.83
 2157.83 2157.83 2157.83 2157.83 2157.83 2157.83 2157.83 2157.83 2157.83 2157.83
 2157.83 2157.83 2157.83 2157.83 2157.83 2157.83 2157.83 2157.83 2157.83 2157.83
 2157.83 2157.83 2157.83 2157.83 2157.83 2157.83 2157.83 2157.83 2157.83 2157.83
 2157.83 2157.83 2157.83 2157.83 2157.83 2157.83 2157.83 2157.83 2157.83 2157.83
  4852.8  4868.3  4871.9  4885.7  4898.4  4900.8  4903.5  4909.1  4914.1  4935.5
  4938.9  4971.5  4971.5  5028.5  5028.5    5065  5079.9  5083.9  5087.8  5093.6
  5097.1  5110.6  5116.7  5123.3  5128.7  5132.9  5138.7  5142.4  5149.7  5153.1
  5179.7  5181.6  5183.7  5192.3  5198.3  5201.9  5211.2    5220  5223.9  5226.1
  5233.2  5238.8  5250.5  5255.3  5262.9  5268.8  5276.1  5276.9    5284  5291.9
  5301.5  5307.2  5311.3    5315  5330.5  5337.3  5344.6  5345.8  5352.9  5369.6
 2229.48 2223.11 2220.83 2211.53 2203.42 2201.71  2200.6 2197.78  2194.9 2183.25
    2182    2182    2182    2182    2182    2182 2182.74 2182.83 2183.15 2183.04
 2183.15 2183.88 2183.72 2183.73 2183.41 2183.49 2183.76 2183.83 2184.37 2184.75
 2185.48 2185.26 2185.88 2186.94    2187 2187.25 2187.41 2186.41 2186.46 2186.16
 2186.58 2186.05 2187.31 2187.42 2189.02 2191.21 2193.19 2193.54 2193.84 2193.56
 2197.78 2200.94 2202.12 2202.48 2203.33 2203.55 2203.23 2203.92 2206.39 2215.51
 2157.83 2157.83 2157.83 2157.83 2157.83 2157.83 2157.83 2157.83 2157.83 2157.83
 2157.83 2157.83    2181    2181 2157.83 2157.83 2157.83 2157.83 2157.83 2157.83
 2157.83 2157.83 2157.83 2157.83 2157.83 2157.83 2157.83 2157.83 2157.83 2157.83
 2157.83 2157.83 2157.83 2157.83 2157.83 2157.83 2157.83 2157.83 2157.83 2157.83
 2157.83 2157.83 2157.83 2157.83 2157.83 2157.83 2157.83 2157.83 2157.83 2157.83
 2157.83 2157.83 2157.83 2157.83 2157.83 2157.83 2157.83 2157.83 2157.83 2157.83
Abutment Skew #Up #Dn= , 2 , 2
  4971.5    4985
    2181 2178.39
  4971.5  4979.2
    2181  2177.5
Abutment Skew #Up #Dn= , 2 , 2
    5015  5028.5
 2179.56    2181
  5020.7  5028.5
 2178.66    2181
BR Coef= 1 , 1 , 0 ,1.25, 0 ,,,0.8,0,2,0,
WSPro=,,,, 1 ,,,, 0 ,,,, 0 ,,,,-1 ,-1 ,-1 , 0 , 0 , 0 , 0 , 0
BC Design=,, 0 ,, 0 ,,,,,,
BC HTab HWMax=2226.59

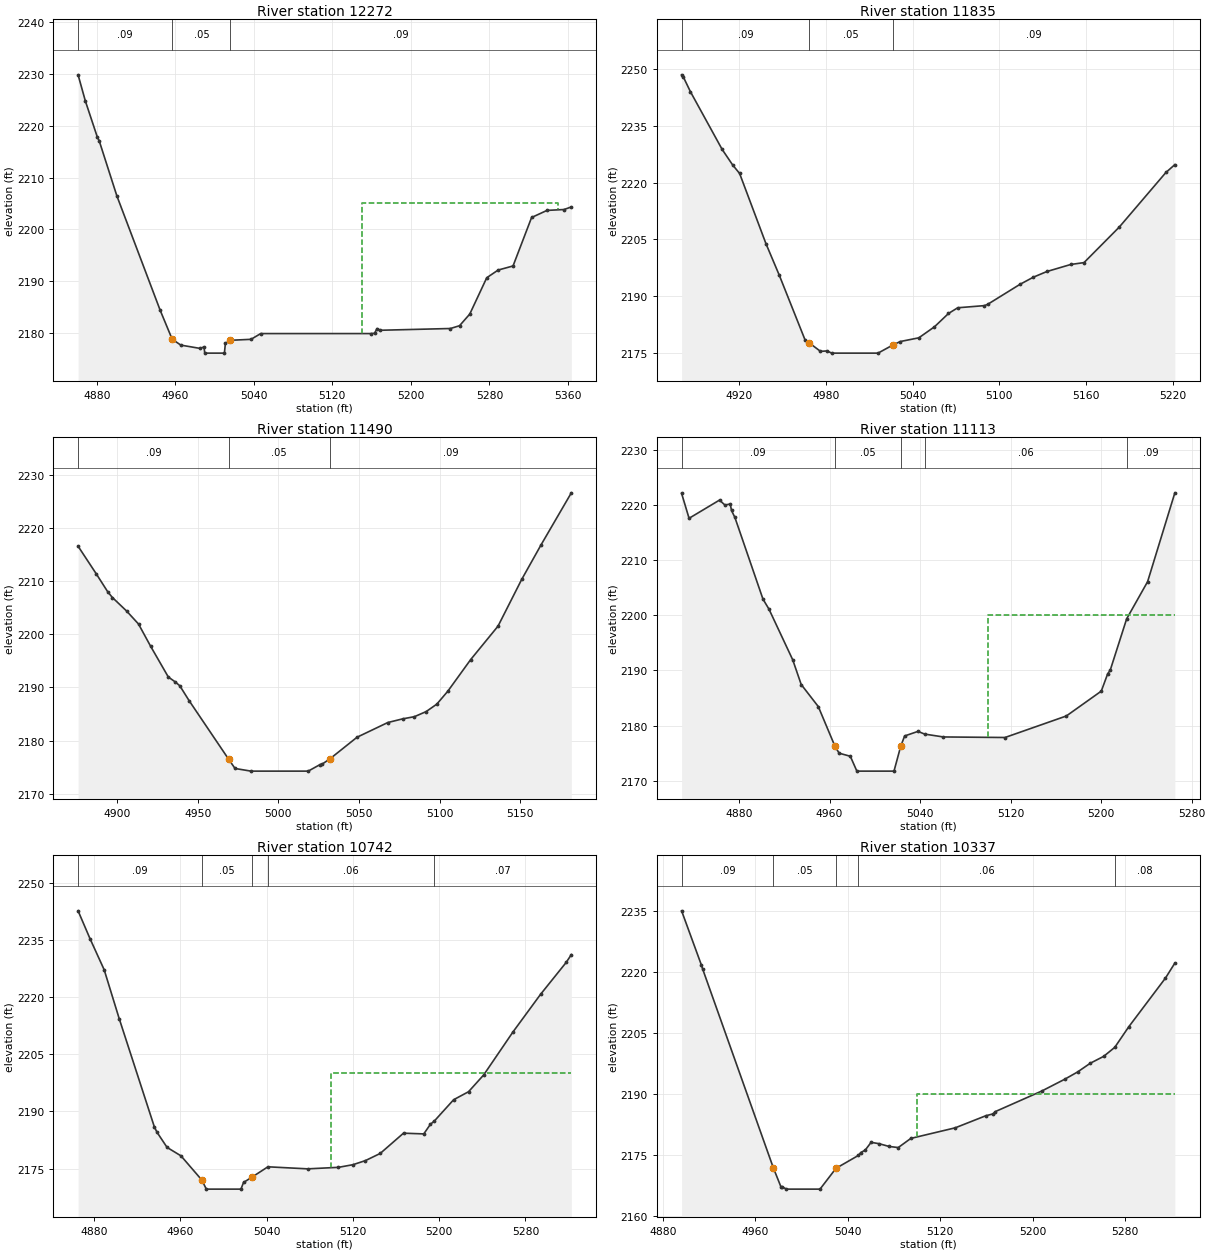
Type RM Length L Ch R = 1 ,12272   ,437,437,437
BEGIN DESCRIPTION:
XS 42
END DESCRIPTION:
XS GIS Cut Line= 6
      1040231.74       845016.21      1040149.79       844978.07
      1040091.86        844948.4      1040072.08       844831.13
        1040041.       844730.82      1039917.95       844725.58
#Sta/Elev= 30
  4860.9 2229.85  4868.3  2224.8  4880.6 2217.76  4882.4 2217.11  4900.4 2206.46
  4944.6 2184.31  4956.8 2178.73  4965.6  2177.6  4985.3 2176.96  4989.2 2177.25
    4990 2176.05    5010 2176.05    5011 2177.94  5016.2 2178.53  5037.1 2178.72
    5047 2179.83  5159.3 2179.83    5163 2179.89  5165.5  2180.8  5168.9 2180.47
  5240.3 2180.81  5249.6 2181.35    5260  2183.6  5277.3 2190.62  5288.9 2192.11
  5304.1  2192.9    5323 2202.27  5338.7 2203.64    5356 2203.81  5363.5 2204.31
#Mann= 3 ,-1 , 0
  4860.9     .09       0  4956.8     .05       0  5016.2     .09       0
#XS Ineff= 3 ,-1
    4900  4940.5    2182  5059.5    5150            5150    5350    2205
Permanent Ineff=
       F       T       F
Bank Sta=4956.8,5016.2
Exp/Cntr=0.5,0.3

Type RM Length L Ch R = 1 ,11835   ,345,345,345
BEGIN DESCRIPTION:
XS 41
END DESCRIPTION:
XS GIS Cut Line= 4
      1040155.17       844481.59      1040063.67       844515.48
      1040009.45       844545.98      1039829.84        844569.7
#Sta/Elev= 30
  4880.3 2248.51  4881.6 2247.87  4886.4 2244.05  4908.3  2228.8  4915.6 2224.66
  4920.4 2222.42  4938.6 2203.86  4947.8 2195.52  4965.8 2178.23  4968.7 2177.55
  4976.3 2175.35    4981 2175.46    4984 2174.88  5016.1 2174.88  5026.5 2177.06
  5031.5 2177.95  5044.3 2178.93  5055.1 2181.84  5064.8 2185.37  5071.2 2186.88
  5089.7 2187.45  5091.9 2187.79  5114.1 2193.05  5123.4 2194.96  5132.9 2196.48
  5149.4 2198.34  5158.5 2198.83  5182.9 2208.24  5215.1 2222.67  5221.3 2224.75
#Mann= 3 ,-1 , 0
  4880.3     .09       0  4968.7     .05       0  5026.5     .09       0
Bank Sta=4968.7,5026.5
Exp/Cntr=0.3,0.1

Type RM Length L Ch R = 1 ,11490   ,377,377,377
BEGIN DESCRIPTION:
XS 40
END DESCRIPTION:
XS GIS Cut Line= 4
      1040067.06       844156.27      1039982.34        844176.6
      1039907.79       844217.27       1039782.4       844264.71
#Sta/Elev= 30
  4875.7  2216.6    4887 2211.39  4894.2 2207.97    4897 2206.94  4905.8  2204.4
  4913.2 2201.95  4920.7 2197.77  4931.7 2191.97  4935.9 2191.07  4938.8 2190.33
  4944.6 2187.52  4969.2 2176.46  4973.1 2174.75    4983 2174.25  5018.5 2174.25
  5025.9 2175.49  5027.2 2175.58  5031.9 2176.54  5048.8 2180.63  5067.9  2183.4
  5077.1 2184.09  5084.4  2184.5  5091.7 2185.46  5098.3 2186.86  5105.1 2189.28
  5119.3 2195.24  5136.3 2201.55    5151 2210.35    5163 2216.85  5181.8 2226.65
#Mann= 3 ,-1 , 0
  4875.7     .09       0  4969.2     .05       0  5031.9     .09       0
Bank Sta=4969.2,5031.9
Exp/Cntr=0.3,0.1

Type RM Length L Ch R = 1 ,11113   ,371,371,371
BEGIN DESCRIPTION:
XS 39
END DESCRIPTION:
XS GIS Cut Line= 5
      1040043.83       843757.37      1039924.73       843803.84
      1039840.01       843847.89      1039731.57       843895.33
      1039673.96       843969.89
#Sta/Elev= 30
  4829.2 2222.18  4835.8 2217.65  4862.7 2220.96  4867.5 2220.06  4872.2 2220.25
  4873.3 2219.07  4876.3 2217.81  4901.1 2202.97  4906.4 2201.15  4927.4 2191.94
  4934.9 2187.45    4950 2183.44  4964.6 2176.29  4968.4 2174.97  4978.3 2174.41
  4984.1 2171.71  5016.9 2171.71  5022.8  2176.2  5026.3  2178.1  5038.1 2178.93
    5044 2178.44  5060.5 2177.92    5115 2177.82  5169.2 2181.73  5200.1 2186.25
  5205.7 2189.38    5208 2190.06  5222.5 2199.38    5241 2206.13  5265.1 2222.28
#Mann= 5 ,-1 , 0
  4829.2     .09       0  4964.6     .05       0  5022.8     .09       0
    5044     .06       0  5222.5     .09       0
#XS Ineff= 2 , 0
       0                    5100       0    2200
Permanent Ineff=
       F       F
Bank Sta=4964.6,5022.8
Exp/Cntr=0.3,0.1

Type RM Length L Ch R = 1 ,10742   ,405,405,405
BEGIN DESCRIPTION:
XS 38
END DESCRIPTION:
XS GIS Cut Line= 5
      1039785.28       843395.69      1039728.18       843478.51
      1039677.35       843529.34      1039589.24       843590.34
      1039487.58       843736.06
#Sta/Elev= 30
  4865.2 2242.75  4876.2 2235.47  4889.4 2227.25  4903.3 2214.43  4935.9 2185.96
  4938.4 2184.52  4947.7 2180.55  4960.6 2178.33  4979.9 2171.98  4984.1 2169.58
  5016.2 2169.58  5018.6 2171.34  5026.6 2172.76  5041.2 2175.45  5078.1 2174.91
  5106.6 2175.31    5120    2176  5131.6 2177.08  5145.3 2178.96  5166.9 2184.29
  5185.7  2184.1  5191.8 2186.61  5195.6 2187.52  5213.4 2193.09  5227.2 2195.19
  5241.2 2199.59  5268.3 2210.87    5294 2220.81  5317.7 2229.18  5322.5 2231.24
#Mann= 5 ,-1 , 0
  4865.2     .09       0  4979.9     .05       0  5026.6     .09       0
  5041.2     .06       0  5195.6     .07       0
#XS Ineff= 2 , 0
       0                    5100       0    2200
Permanent Ineff=
       F       F
Bank Sta=4979.9,5026.6
Exp/Cntr=0.3,0.1

Type RM Length L Ch R = 1 ,10337   ,311,311,311
BEGIN DESCRIPTION:
XS 37
END DESCRIPTION:
XS GIS Cut Line= 5
      1039376.97       843203.54       1039358.8       843288.74
       1039358.8       843346.35      1039345.25       843461.57
      1039287.64       843617.45
#Sta/Elev= 30
  4896.3 2235.03  4913.3 2221.81  4914.4 2220.82  4975.7 2171.84  4982.3 2167.16
  4983.4 2167.19    4987 2166.61  5016.1 2166.61  5029.9 2171.72  5049.4 2174.91
  5051.3 2175.59  5055.2  2176.2  5060.3 2178.11  5067.1 2177.79  5075.9  2177.1
  5083.8 2176.83  5094.7 2179.08  5133.1 2181.68  5159.5 2184.64  5165.9 2185.11
  5167.8 2185.67  5207.9 2190.71  5227.9 2193.63    5239 2195.41    5250 2197.56
  5261.6 2199.25  5271.2 2201.47  5283.3 2206.52  5315.1 2218.51  5323.2 2222.18
#Mann= 5 ,-1 , 0
  4896.3     .09       0  4975.7     .05       0  5029.9     .09       0
  5049.4     .06       0  5271.2     .08       0
#XS Ineff= 2 , 0
       0                    5100       0    2190
Permanent Ineff=
       F       F
Bank Sta=4975.7,5029.9
Exp/Cntr=0.3,0.1

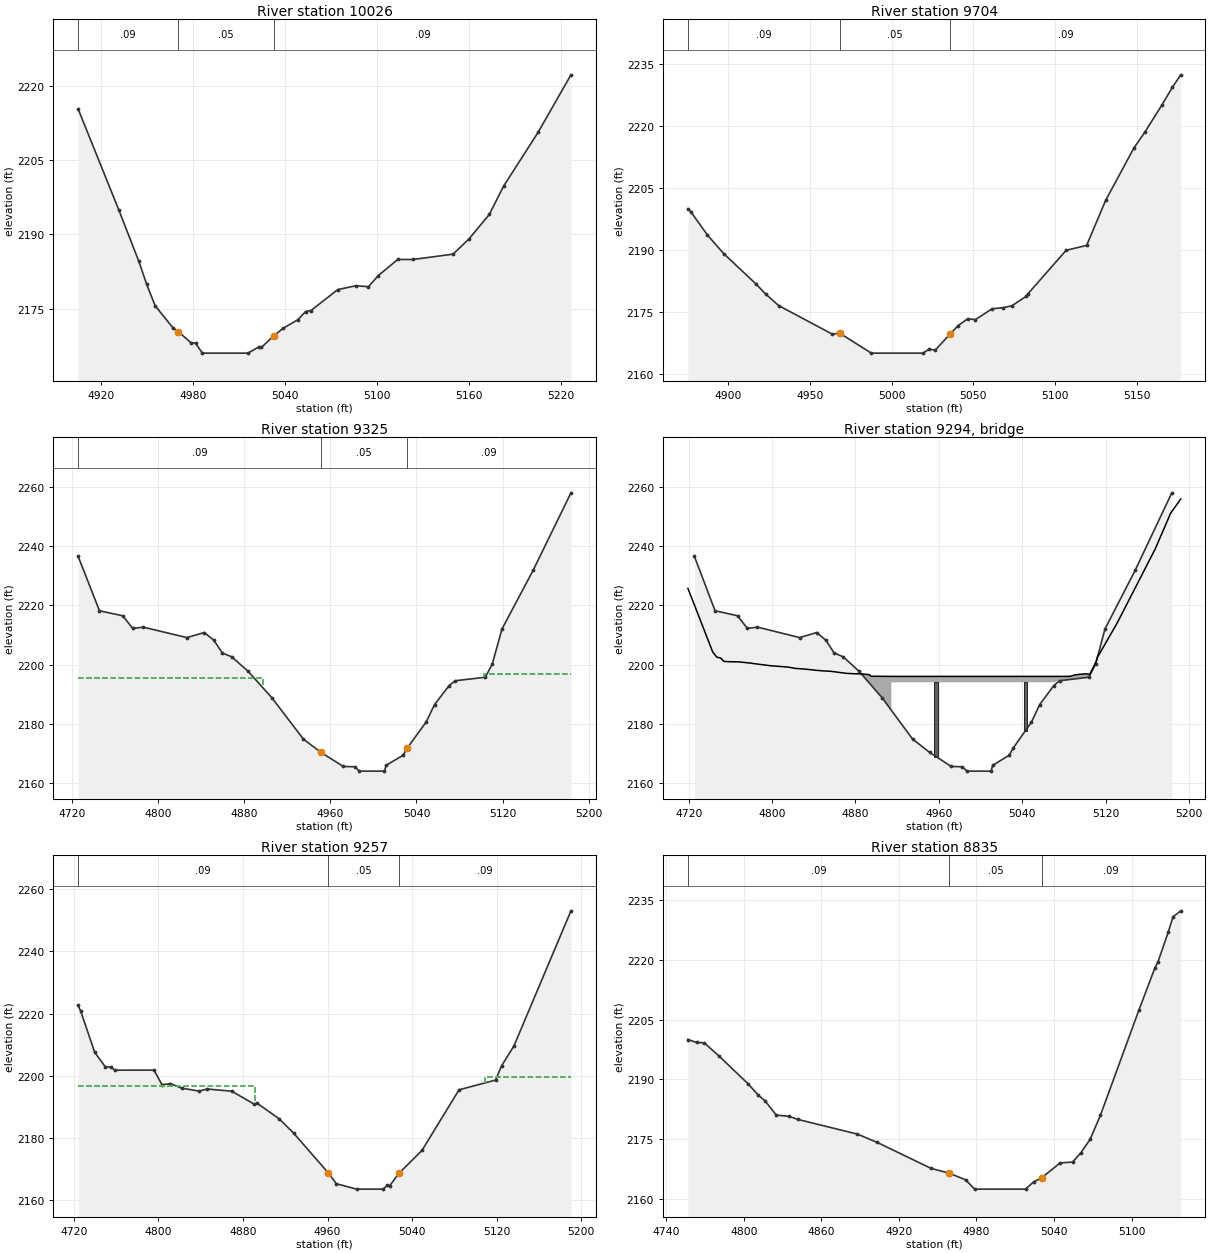
Type RM Length L Ch R = 1 ,10026   ,322,322,322
BEGIN DESCRIPTION:
XS 36
END DESCRIPTION:
XS GIS Cut Line= 5
      1039047.03       843254.85      1039047.03       843319.24
      1039063.98       843380.24      1039114.81       843464.96
      1039121.59       843559.84
#Sta/Elev= 30
    4905 2215.31  4931.6  2194.9  4944.6 2184.59  4949.8 2179.88  4955.3 2175.58
    4967  2171.1  4970.4 2170.37  4978.5 2168.17  4981.7 2168.02  4986.1 2166.03
  5015.9 2166.03  5023.2 2167.34  5024.6 2167.17  5032.7 2169.53  5038.9 2171.06
  5048.3 2172.75  5053.4  2174.4  5056.9 2174.61  5074.5 2178.85  5086.3 2179.62
  5094.5 2179.43  5100.8 2181.65  5113.6 2184.92  5123.6 2184.92  5149.6 2185.99
  5159.9    2189  5173.3 2193.99  5182.7 2199.74  5205.2 2210.58  5226.6 2222.16
#Mann= 3 ,-1 , 0
    4905     .09       0  4970.4     .05       0  5032.7     .09       0
Bank Sta=4970.4,5032.7
Exp/Cntr=0.3,0.1

Type RM Length L Ch R = 1 ,9704    ,379,379,379
BEGIN DESCRIPTION:
XS 35
END DESCRIPTION:
XS GIS Cut Line= 4
      1038731.88       843349.74      1038742.04       843441.24
      1038772.54       843502.23      1038843.71       843624.23
#Sta/Elev= 30
  4875.4 2199.97  4877.2 2199.25  4887.4 2193.57  4897.4 2189.05  4917.1 2181.71
  4922.9 2179.32  4930.9 2176.49  4963.6 2169.58  4968.3 2169.78  4987.6 2164.95
  5019.3 2164.95  5022.8 2165.88  5026.8 2165.72  5035.7 2169.53  5040.7 2171.63
  5046.6 2173.29  5051.3 2173.08  5061.5 2175.71  5068.4 2175.97  5073.6 2176.44
  5082.5 2178.76  5083.3 2179.29  5106.8 2189.89  5119.3 2191.07    5131 2202.04
  5148.3 2214.74  5154.8 2218.46  5165.3 2225.09  5171.8 2229.44  5176.9 2232.44
#Mann= 3 ,-1 , 0
  4875.4     .09       0  4968.3     .05       0  5035.7     .09       0
Bank Sta=4968.3,5035.7
Exp/Cntr=0.5,0.3

Type RM Length L Ch R = 1 ,9325    ,68,68,68
BEGIN DESCRIPTION:
XS 34
END DESCRIPTION:
XS GIS Cut Line= 6
      1038219.85       843422.53      1038221.27       843442.31
      1038318.75       843443.72      1038366.79       843471.98
      1038413.41       843657.06      1038444.49       843746.07
#Sta/Elev= 30
  4725.4 2236.69  4745.3  2218.2  4766.9 2216.51  4776.3 2212.22    4786 2212.67
  4826.6 2209.13  4842.8 2210.85  4851.7  2208.2  4859.5 2203.93  4868.3 2202.62
  4883.5 2197.71  4905.5  2188.8  4934.9 2174.76 4951.31 2170.26  4971.9 2165.52
  4982.7 2165.41  4986.9 2163.94  5010.2 2163.94  5011.7 2165.89  5027.5 2169.31
  5031.5  2171.8  5048.9 2180.52  5056.8 2186.46  5070.4 2192.91    5076 2194.53
    5104 2195.71  5110.5 2200.22  5119.5 2212.07  5148.4 2231.87  5183.6 2258.12
#Mann= 3 , 0 , 0
  4725.4     .09       0 4951.31     .05       0  5031.5     .09       0
#XS Ineff= 2 , 0
       0    4897 2195.37    5103       0 2196.79
Permanent Ineff=
       F       F
Bank Sta=4951.31,5031.5
Exp/Cntr=0.5,0.3

Type RM Length L Ch R = 3 ,9294    ,,,
BEGIN DESCRIPTION:
XS 33 TOR
Structure ID: XS 33
Approximate Survey Structure
END DESCRIPTION:
Bridge Culvert--1,0,-1,-1, 0
Deck Dist Width WeirC Skew NumUp NumDn MinLoCord MaxHiCord MaxSubmerge Is_Ogee
17.5,27,3,0, 46, 46, , , , 0, 1,1,,
  4719.2  4719.5  4720.7  4723.4    4743    4747  4750.7  4753.8  4760.7  4761.7
  4769.2  4770.4  4780.2  4782.4  4797.7  4814.5  4816.4  4822.4  4830.4  4831.9
  4839.7  4840.5  4844.4  4848.7  4856.1  4871.6  4879.8  4886.8    4887  4893.5
  4894.7  4914.5  4914.5  5085.5  5085.5    5091  5093.5  5100.7  5104.9    5111
  5112.7  5113.4  5131.4  5167.7  5182.5  5192.2
 2225.76 2225.53 2224.44 2222.06 2204.27  2202.5 2202.21 2201.06 2200.95 2200.96
 2200.89 2200.82 2200.47 2200.33 2199.64 2199.17 2199.08  2198.7 2198.51 2198.45
 2198.17 2198.11    2198 2197.87 2197.73 2197.02 2196.88 2196.83 2196.82 2196.57
 2196.06    2196    2196    2196    2196 2196.54 2196.64 2196.88 2196.72 2201.04
 2202.95 2203.17 2214.22 2239.15 2251.25 2256.03
  2142.5  2142.5  2142.5  2142.5  2142.5  2142.5  2142.5  2142.5  2142.5  2142.5
  2142.5  2142.5  2142.5  2142.5  2142.5  2142.5  2142.5  2142.5  2142.5  2142.5
  2142.5  2142.5  2142.5  2142.5  2142.5  2142.5  2142.5  2142.5  2142.5  2142.5
  2142.5  2142.5    2194    2194  2142.5  2142.5  2142.5  2142.5  2142.5  2142.5
  2142.5  2142.5  2142.5  2142.5  2142.5  2142.5
  4719.2  4719.5  4720.7  4723.4    4743    4747  4750.7  4753.8  4760.7  4761.7
  4769.2  4770.4  4780.2  4782.4  4797.7  4814.5  4816.4  4822.4  4830.4  4831.9
  4839.7  4840.5  4844.4  4848.7  4856.1  4871.6  4879.8  4886.8    4887  4893.5
  4894.7  4914.5  4914.5  5085.5  5085.5    5091  5093.5  5100.7  5104.9    5111
  5112.7  5113.4  5131.4  5167.7  5182.5  5192.2
 2225.76 2225.53 2224.44 2222.06 2204.27  2202.5 2202.21 2201.06 2200.95 2200.96
 2200.89 2200.82 2200.47 2200.33 2199.64 2199.17 2199.08  2198.7 2198.51 2198.45
 2198.17 2198.11    2198 2197.87 2197.73 2197.02 2196.88 2196.83 2196.82 2196.57
 2196.06    2196    2196    2196    2196 2196.54 2196.64 2196.88 2196.72 2201.04
 2202.95 2203.17 2214.22 2239.15 2251.25 2256.03
  2142.5  2142.5  2142.5  2142.5  2142.5  2142.5  2142.5  2142.5  2142.5  2142.5
  2142.5  2142.5  2142.5  2142.5  2142.5  2142.5  2142.5  2142.5  2142.5  2142.5
  2142.5  2142.5  2142.5  2142.5  2142.5  2142.5  2142.5  2142.5  2142.5  2142.5
  2142.5  2142.5    2194    2194  2142.5  2142.5  2142.5  2142.5  2142.5  2142.5
  2142.5  2142.5  2142.5  2142.5  2142.5  2142.5
Pier Skew, UpSta & Num, DnSta & Num=  ,4957.3, 2 ,4957.3, 2 , 0 , 0 , 0 ,0,0
       3       3
 2169.22    2194
       3       3
 2169.78    2194
Pier Skew, UpSta & Num, DnSta & Num=  ,5042.8, 2 ,5042.8, 2 , 0 , 0 , 0 ,0,0
       3       3
 2177.19    2194
       3       3
 2174.19    2194
Abutment Skew #Up #Dn= , 2 , 2
  4914.5    4975
    2194 2165.58
  4914.5  4940.7
    2194 2176.53
Abutment Skew #Up #Dn= , 2 , 2
    5025  5085.5
 2169.73    2194
    5025  5085.5
 2167.37    2194
BR Coef= 1 , 1 , 0 ,1.25, 0 ,,,0.8,0,2,0,
WSPro=,,,, 1 ,,,, 0 ,,,, 0 ,,,,-1 ,-1 ,-1 , 0 , 0 , 0 , 0 , 0
BC Design=,, 0 ,, 0 ,,,,,,
BC HTab HWMax=2258.12

Type RM Length L Ch R = 1 ,9257    ,422,422,422
BEGIN DESCRIPTION:
XS 32
END DESCRIPTION:
XS GIS Cut Line= 6
      1038173.23       843435.25      1038183.06       843514.08
      1038267.89       843518.61      1038314.51        843528.5
      1038351.25        843705.1      1038383.74        843771.5
#Sta/Elev= 30
  4723.9 2222.63  4726.3  2220.9  4739.7 2207.55  4749.6 2202.95  4755.4 2202.76
  4758.6 2201.86  4795.8 2201.87  4803.3 2197.18  4811.2 2197.55  4821.9 2196.08
  4838.5 2195.14  4846.2  2195.8  4869.4  2195.1  4890.5 2190.94    4893 2191.32
  4914.2 2186.23  4927.9 2181.63  4960.5 2168.94  4968.3 2165.39  4987.5 2163.65
  5012.5 2163.65  5016.7 2164.89  5018.8 2164.75  5027.7 2168.79  5049.3 2176.06
  5084.4 2195.55    5119 2198.68  5124.7 2203.29  5136.3  2209.6  5190.3 2253.03
#Mann= 3 ,-1 , 0
  4723.9     .09       0  4960.5     .05       0  5027.7     .09       0
#XS Ineff= 2 , 0
       0    4891 2196.67    5109       0 2199.62
Permanent Ineff=
       F       F
Bank Sta=4960.5,5027.7
Exp/Cntr=0.5,0.3

Type RM Length L Ch R = 1 ,8835    ,484,484,484
BEGIN DESCRIPTION:
XS 31
END DESCRIPTION:
XS GIS Cut Line= 5
       1037877.9       843397.18      1037928.74        843481.9
      1037915.18       843607.29       1037908.4       843654.73
       1037908.4       843763.17
#Sta/Elev= 30
  4756.8    2200  4763.5 2199.27  4769.5 2199.16  4781.1 2195.78  4803.3 2188.89
  4811.3 2186.01  4816.4 2184.62  4825.2    2181  4834.8  2180.7  4841.8 2179.92
    4888 2176.22  4903.3 2174.13  4945.1 2167.58  4958.9 2166.41  4971.6 2164.73
  4978.7 2162.39    5018 2162.39  5024.2  2164.2  5030.4 2165.21  5044.8 2168.98
  5054.4 2169.19  5060.8 2171.52    5068 2174.92  5075.9 2180.92  5105.6  2207.3
  5118.1 2218.01  5120.5 2219.54  5128.5 2227.11  5132.1 2230.85  5138.1 2232.35
#Mann= 3 ,-1 , 0
  4756.8     .09       0  4958.9     .05       0  5030.4     .09       0
Bank Sta=4958.9,5030.4
Exp/Cntr=0.3,0.1