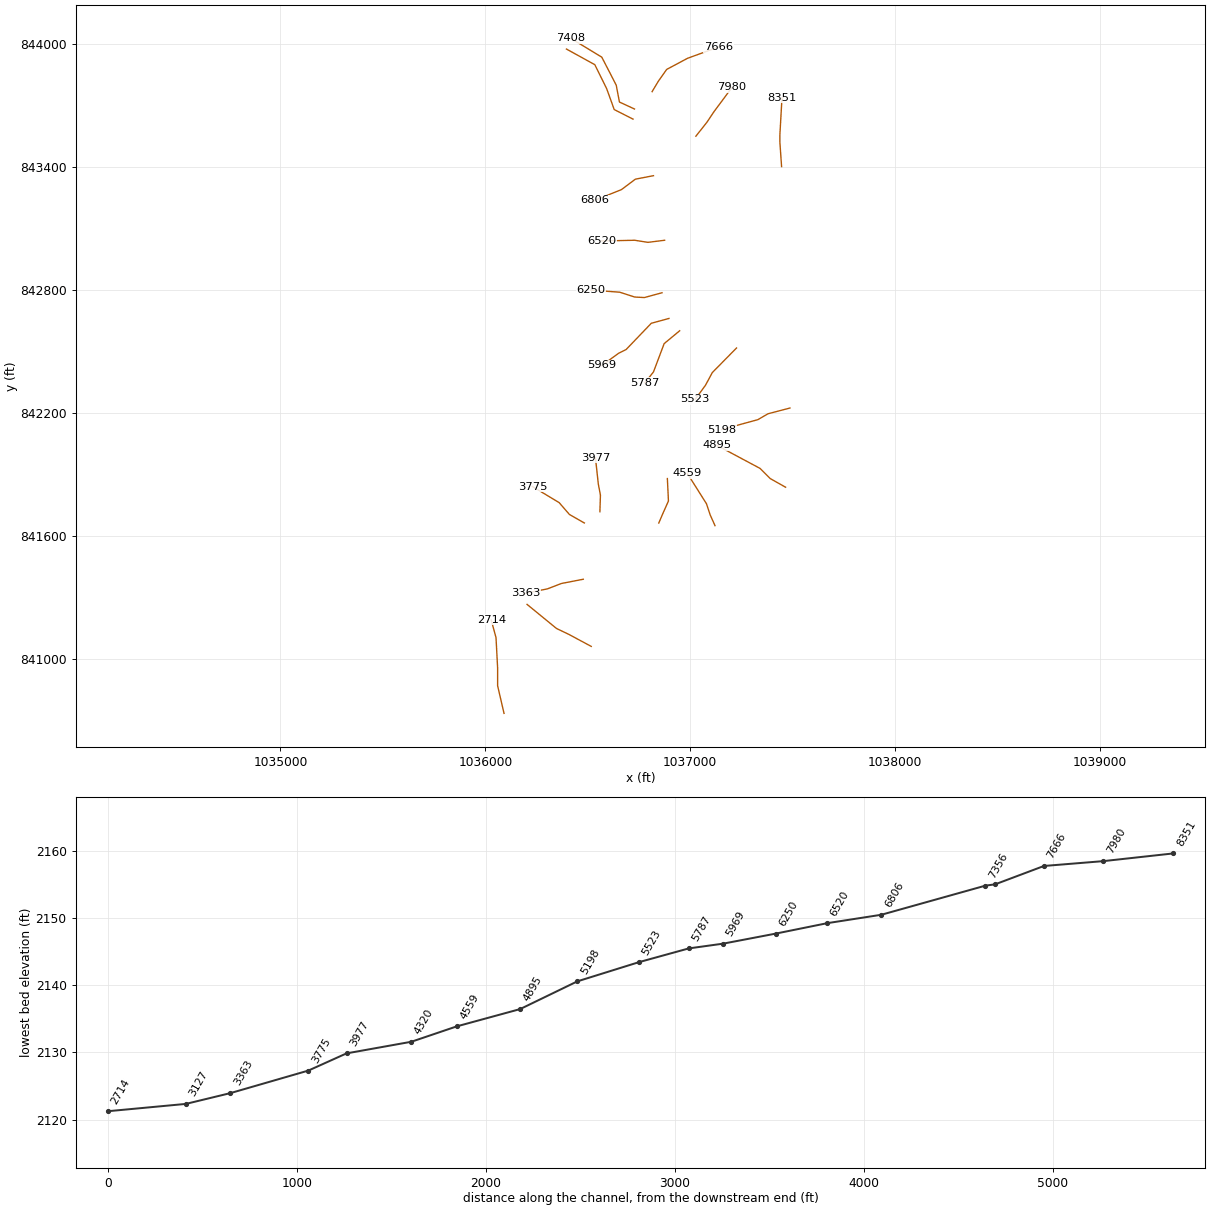
HEC-RAS study lds_big_rock_crk.prj: Big Rock Creek Limited Detail Study

--- lds_big_rock_crk.g01 (geometry) --- (continued)

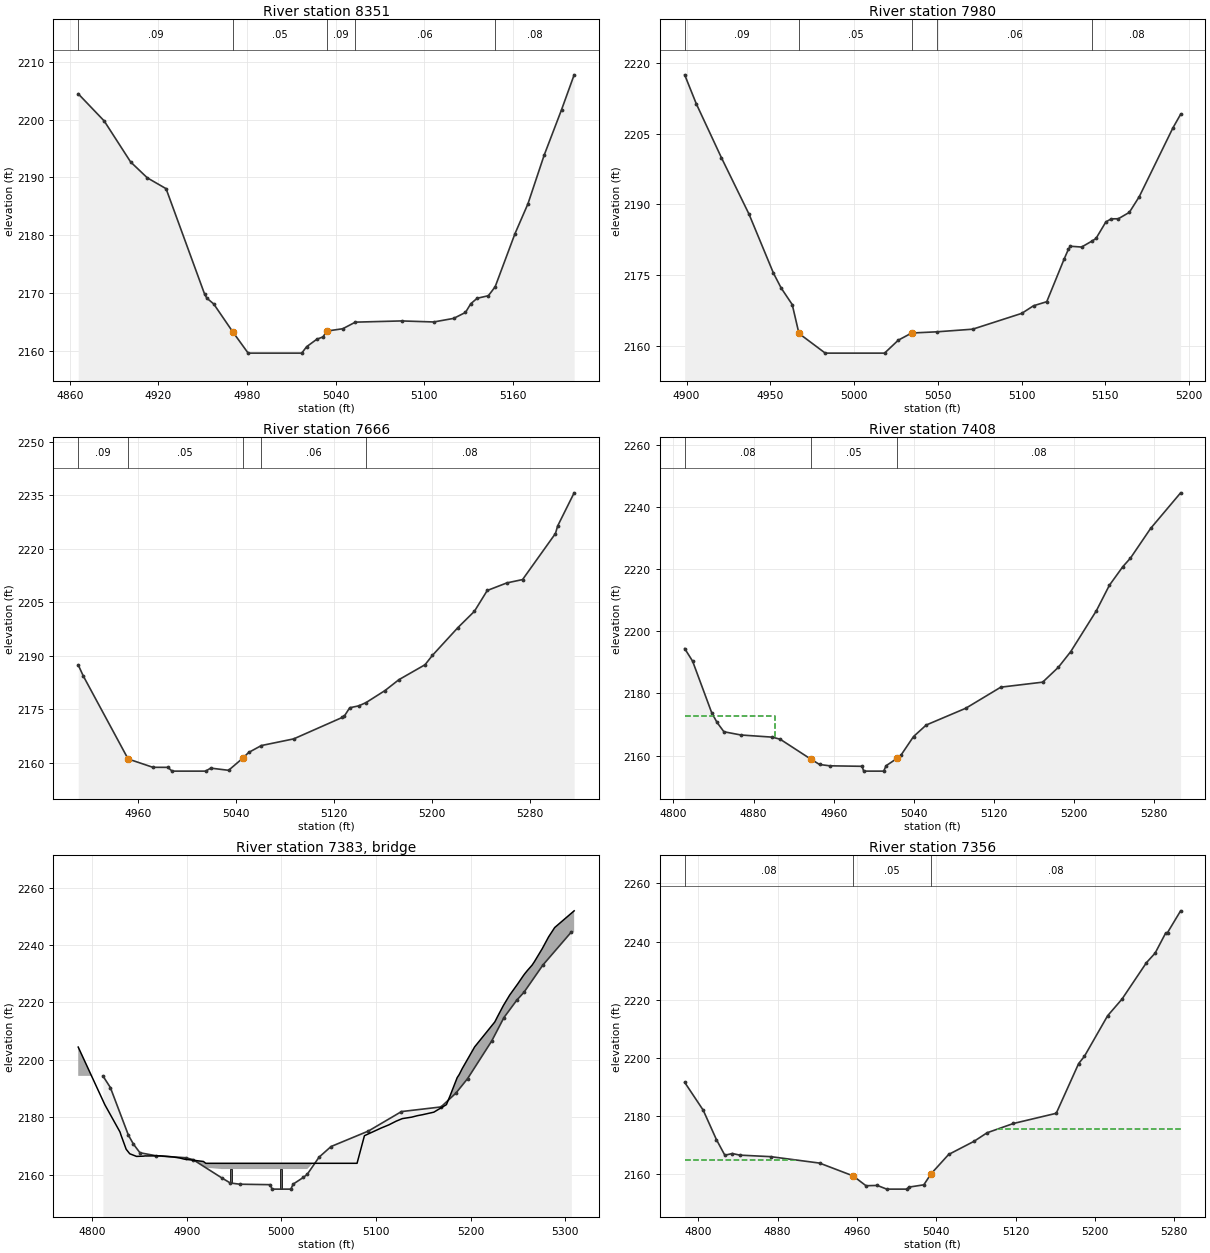
Type RM Length L Ch R = 1 ,8351    ,371,371,371
BEGIN DESCRIPTION:
XS 30
END DESCRIPTION:
XS GIS Cut Line= 4
      1037445.62       843404.17      1037437.36       843522.57
      1037437.36       843559.84      1037447.53       843739.45
#Sta/Elev= 30
  4865.7 2204.47  4883.3 2199.77  4901.2 2192.68  4912.5 2189.93  4925.2 2188.06
  4951.3 2169.82  4952.8 2169.13  4957.5 2168.11  4970.3 2163.32  4980.8 2159.61
  5017.1 2159.61  5020.4 2160.72  5027.3 2162.01  5031.6 2162.43  5033.9 2163.42
  5044.9 2163.83  5053.4 2164.97  5084.7 2165.18  5106.5    2165    5120 2165.62
    5128 2166.65  5131.6 2168.16  5135.9  2169.1  5143.5 2169.54  5148.1 2171.09
  5161.5 2180.26  5170.3 2185.44  5181.3 2193.86  5193.1 2201.74  5201.6 2207.75
#Mann= 5 ,-1 , 0
  4865.7     .09       0  4970.3     .05       0  5033.9     .09       0
  5053.4     .06       0  5148.1     .08       0
Bank Sta=4970.3,5033.9
Exp/Cntr=0.3,0.1

Type RM Length L Ch R = 1 ,7980    ,314,314,314
BEGIN DESCRIPTION:
XS 29
END DESCRIPTION:
XS GIS Cut Line= 4
      1037027.42       843552.51      1037081.54       843620.84
      1037115.43       843671.67      1037203.54       843790.28
#Sta/Elev= 30
  4898.9 2217.51  4905.8 2211.39  4920.8 2199.95  4937.3 2187.95  4951.9 2175.42
  4956.5 2172.27  4963.1 2168.76  4967.1 2162.64  4982.8 2158.46  5018.2 2158.46
  5026.4 2161.21  5034.4 2162.73  5049.3 2162.98  5070.8 2163.54  5100.1  2166.9
  5107.1 2168.51    5115 2169.37  5125.4 2178.44  5127.9 2180.48  5129.1 2181.14
  5135.8 2180.97  5142.3  2182.3  5144.4 2182.79  5150.3 2186.31  5153.5 2186.95
  5157.7 2186.97  5164.3 2188.33  5170.2 2191.65  5190.3 2206.25  5194.9 2209.14
#Mann= 5 ,-1 , 0
  4898.9     .09       0  4967.1     .05       0  5034.4     .09       0
  5049.3     .06       0  5142.3     .08       0
Bank Sta=4967.1,5034.4
Exp/Cntr=0.3,0.1

Type RM Length L Ch R = 1 ,7666    ,258,258,258
BEGIN DESCRIPTION:
XS 28
END DESCRIPTION:
XS GIS Cut Line= 5
      1036813.83       843769.95      1036844.32       843820.78
      1036884.99       843878.39      1036986.65       843932.61
      1037137.62       843987.67
#Sta/Elev= 30
  4910.7 2187.48  4914.9 2184.35  4951.5 2161.15  4971.8 2158.81    4984  2158.8
  4987.5 2157.74  5014.9 2157.74  5019.1 2158.58  5033.7 2157.97  5045.1  2161.3
  5050.1 2162.96  5060.5  2164.9    5087 2166.77  5126.8 2172.79  5128.3  2173.1
  5132.8 2175.48  5140.2 2176.02  5146.1 2176.92  5161.7 2180.31    5173 2183.34
  5194.4 2187.53  5200.5 2190.17  5221.3 2197.93  5234.8 2202.49  5245.3 2208.32
  5261.3 2210.44  5274.2 2211.38  5301.1 2224.28  5302.9 2226.39  5316.4 2235.67
#Mann= 5 ,-1 , 0
  4910.7     .09       0  4951.5     .05       0  5045.1     .09       0
  5060.5     .06       0  5146.1     .08       0
Bank Sta=4951.5,5045.1
Exp/Cntr=0.5,0.3

Type RM Length L Ch R = 1 ,7408    ,52,52,52
BEGIN DESCRIPTION:
XS 27
END DESCRIPTION:
XS GIS Cut Line= 6
       1036727.9       843685.32      1036654.43       843719.23
      1036638.89       843801.17      1036609.22        843859.1
      1036568.24       843938.22      1036417.07       844030.05
#Sta/Elev= 30
  4811.2 2194.43  4819.1 2190.38  4838.2 2173.78  4843.5 2170.68  4850.4 2167.67
  4867.4 2166.63  4898.6 2165.94  4906.6 2165.27  4936.9 2158.93  4945.9 2157.15
    4956 2156.72  4988.4 2156.56    4990 2155.01    5010 2155.01  5012.4 2156.75
  5023.2 2159.08  5027.3 2160.16  5039.8 2166.13  5052.5 2169.84    5092 2175.23
    5127 2182.01  5168.8 2183.62  5184.5 2188.41  5196.9 2193.47  5222.5 2206.62
  5235.4 2214.75  5248.9 2220.77  5256.5 2223.51  5276.6 2233.04  5306.6  2244.5
#Mann= 3 ,-1 , 0
  4811.2     .08       0  4936.9     .05       0  5023.2     .08       0
#XS Ineff= 2 , 0
       0 4900.93 2172.68    5099       0  2175.3
Permanent Ineff=
       F       F
Bank Sta=4936.9,5023.2
Exp/Cntr=0.5,0.3

Type RM Length L Ch R = 3 ,7383    ,,,
BEGIN DESCRIPTION:
XS 26 TOR
Structure ID: XS 26
Approximate Survey Structure
END DESCRIPTION:
Bridge Culvert--1,0,-1,-1, 0
Deck Dist Width WeirC Skew NumUp NumDn MinLoCord MaxHiCord MaxSubmerge Is_Ogee
19,12,3,0, 52, 52, , , , 0, 1,1,,
  4785.1  4813.3    4829  4829.4  4830.3  4835.8  4839.6  4846.8  4854.3  4856.1
    4857  4857.6  4871.9  4884.8  4892.5  4897.2  4917.5    4920    4920    5080
    5080  5087.8  5105.7  5113.5  5121.3  5127.9  5137.8    5144  5149.3  5161.2
  5174.5  5178.5  5185.9  5188.1  5191.2  5202.3  5204.3  5225.7  5229.1  5234.7
  5241.5  5249.9  5255.9  5257.6  5260.1  5265.1  5267.5  5275.8  5282.6  5286.9
    5289  5309.6
 2204.46 2184.37 2175.07  2174.8 2173.87  2168.9 2167.32  2166.4  2166.5 2166.58
 2166.55 2166.56  2166.6 2166.23 2165.85 2165.45 2164.64    2164    2164    2164
    2164 2173.61 2176.31 2177.36 2178.66 2179.56 2180.07 2180.59 2180.92  2181.8
 2184.42 2187.61 2193.83 2194.94 2196.96 2203.34  2204.5 2213.22 2215.41  2218.9
 2222.61 2226.45 2229.34 2230.09  2231.1 2232.98 2234.16 2238.69 2242.84    2245
 2246.07 2251.89
  2128.8  2128.8  2128.8  2128.8  2128.8  2128.8  2128.8  2128.8  2128.8  2128.8
  2128.8  2128.8  2128.8  2128.8  2128.8  2128.8  2128.8  2128.8    2162    2162
  2128.8  2128.8  2128.8  2128.8  2128.8  2128.8  2128.8  2128.8  2128.8  2128.8
  2128.8  2128.8  2128.8  2128.8  2128.8  2128.8  2128.8  2128.8  2128.8  2128.8
  2128.8  2128.8  2128.8  2128.8  2128.8  2128.8  2128.8  2128.8  2128.8  2128.8
  2128.8  2128.8
  4785.1  4813.3    4829  4829.4  4830.3  4835.8  4839.6  4846.8  4854.3  4856.1
    4857  4857.6  4871.9  4884.8  4892.5  4897.2  4917.5    4920    4920    5080
    5080  5087.8  5105.7  5113.5  5121.3  5127.9  5137.8    5144  5149.3  5161.2
  5174.5  5178.5  5185.9  5188.1  5191.2  5202.3  5204.3  5225.7  5229.1  5234.7
  5241.5  5249.9  5255.9  5257.6  5260.1  5265.1  5267.5  5275.8  5282.6  5286.9
    5289  5309.6
 2204.46 2184.37 2175.07  2174.8 2173.87  2168.9 2167.32  2166.4  2166.5 2166.58
 2166.55 2166.56  2166.6 2166.23 2165.85 2165.45 2164.64    2164    2164    2164
    2164 2173.61 2176.31 2177.36 2178.66 2179.56 2180.07 2180.59 2180.92  2181.8
 2184.42 2187.61 2193.83 2194.94 2196.96 2203.34  2204.5 2213.22 2215.41  2218.9
 2222.61 2226.45 2229.34 2230.09  2231.1 2232.98 2234.16 2238.69 2242.84    2245
 2246.07 2251.89
  2128.8  2128.8  2128.8  2128.8  2128.8  2128.8  2128.8  2128.8  2128.8  2128.8
  2128.8  2128.8  2128.8  2128.8  2128.8  2128.8  2128.8  2128.8    2162    2162
  2128.8  2128.8  2128.8  2128.8  2128.8  2128.8  2128.8  2128.8  2128.8  2128.8
  2128.8  2128.8  2128.8  2128.8  2128.8  2128.8  2128.8  2128.8  2128.8  2128.8
  2128.8  2128.8  2128.8  2128.8  2128.8  2128.8  2128.8  2128.8  2128.8  2128.8
  2128.8  2128.8
Pier Skew, UpSta & Num, DnSta & Num=  ,4946.7, 2 ,4946.7, 2 , 0 , 0 , 0 ,0,0
       2       2
 2157.12    2162
       2       2
 2159.79    2162
Pier Skew, UpSta & Num, DnSta & Num=  ,5000, 2 ,5000, 2 , 0 , 0 , 0 ,0,0
       2       2
  2148.8    2162
       2       2
 2148.55    2162
Pier Skew, UpSta & Num, DnSta & Num=  ,5053.3, 2 ,5053.3, 2 , 0 , 0 , 0 ,0,0
       2       2
 2169.95    2162
       2       2
  2166.9    2162
Abutment Skew #Up #Dn= , 2 , 2
    4920    4975
    2162 2156.77
    4920    4975
    2162 2155.72
Abutment Skew #Up #Dn= , 2 , 2
    5025    5080
 2159.55    2162
    5025    5080
 2154.57    2162
BR Coef= 1 , 1 , 0 ,1.25, 0 ,,,0.8,0,2,0,
WSPro=,,,, 1 ,,,, 0 ,,,, 0 ,,,,-1 ,-1 ,-1 , 0 , 0 , 0 , 0 , 0
BC Design=,, 0 ,, 0 ,,,,,,
BC HTab HWMax=2244.5

Type RM Length L Ch R = 1 ,7356    ,550,550,550
BEGIN DESCRIPTION:
XS 25
END DESCRIPTION:
XS GIS Cut Line= 5
      1036720.83       843635.87        1036629.       843682.49
      1036592.26       843784.22      1036534.34       843901.48
      1036395.88       843977.78
#Sta/Elev= 30
  4786.3 2191.55    4805 2181.96  4818.3 2171.85  4826.8 2166.47  4834.4 2167.06
  4841.8 2166.51  4873.1 2165.98  4922.3 2163.77 4955.99 2159.38  4969.1 2155.98
  4980.5 2156.08    4990 2154.81    5010 2154.81  5012.5 2155.51  5027.4 2156.29
  5034.7 2160.08  5052.4 2166.73    5078 2171.26  5091.2  2174.2  5117.7 2177.39
  5160.9  2180.9  5183.5 2198.02  5189.2 2200.45  5212.7 2214.46  5227.2 2220.19
  5251.9 2232.75  5260.6 2236.01  5271.2  2242.9  5273.1 2243.08  5286.3 2250.56
#Mann= 3 , 0 , 0
  4786.3     .08       0 4955.99     .05       0  5034.7     .08       0
#XS Ineff= 2 , 0
       0 4899.12    2165    5101       0  2175.6
Permanent Ineff=
       F       F
Bank Sta=4955.99,5034.7
Exp/Cntr=0.5,0.3

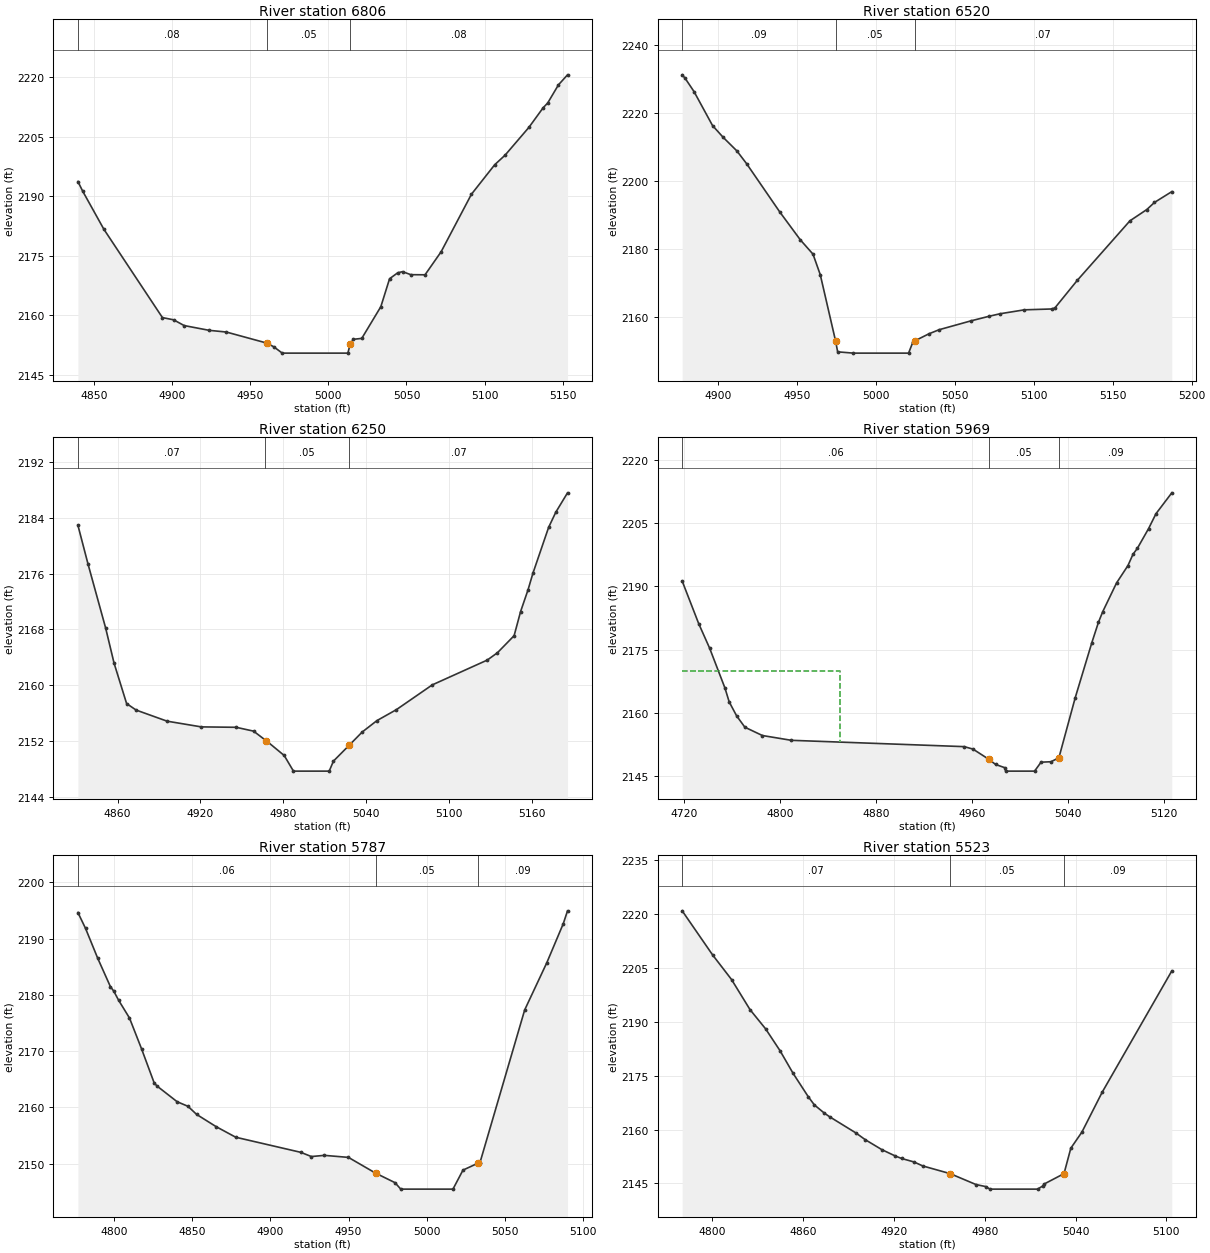
Type RM Length L Ch R = 1 ,6806    ,286,286,286
BEGIN DESCRIPTION:
XS 24
END DESCRIPTION:
XS GIS Cut Line= 4
       1036820.6        843359.9      1036732.49       843342.96
      1036664.72       843292.13      1036535.75       843240.28
#Sta/Elev= 30
  4839.7 2193.68  4842.8 2191.23  4856.3 2181.68  4893.8 2159.43    4901 2158.86
  4907.7 2157.42  4923.7 2156.22  4934.7 2155.79  4960.5 2153.02  4965.1 2152.07
  4970.5 2150.48  5012.5 2150.48  5014.1  2152.9  5016.1 2153.96  5021.4 2154.19
  5033.6 2162.17  5039.2 2169.21  5044.4  2170.7  5047.5 2170.99  5052.8 2170.23
  5061.9  2170.2  5072.2    2176  5091.6 2190.48  5106.5 2197.91  5113.1  2200.3
  5128.4 2207.32  5137.5 2212.25  5140.4 2213.44  5147.3 2218.02  5153.1 2220.54
#Mann= 3 , 0 , 0
  4839.7     .08       0  4960.5     .05       0  5014.1     .08       0
Bank Sta=4960.5,5014.1
Exp/Cntr=0.3,0.1

Type RM Length L Ch R = 1 ,6520    ,270,270,270
BEGIN DESCRIPTION:
XS 23
END DESCRIPTION:
XS GIS Cut Line= 4
      1036874.82       843044.75      1036793.49       843034.58
      1036729.11       843044.75      1036566.44       843041.36
#Sta/Elev= 30
  4877.5 2231.24  4879.3 2230.27    4885  2226.3  4896.7  2216.3  4903.4 2212.84
  4912.1 2208.83  4918.3 2205.04  4939.3 2190.81  4952.3  2182.6  4960.3  2178.4
  4964.9 2172.34  4974.6 2152.79  4975.9 2149.61  4985.9 2149.23  5020.8 2149.23
  5023.6 2152.59  5024.7 2152.84  5033.7 2154.93  5040.2 2156.14  5060.2 2158.73
  5071.9 2160.11  5078.8 2160.84  5094.1 2161.99  5111.3 2162.24  5113.4 2162.55
  5127.6 2170.69  5160.9 2188.22  5171.6 2191.55  5176.4 2193.63  5187.4 2196.82
#Mann= 3 ,-1 , 0
  4877.5     .09       0  4974.6     .05       0  5024.7     .07       0
Bank Sta=4974.6,5024.7
Exp/Cntr=0.3,0.1

Type RM Length L Ch R = 1 ,6250    ,281,281,281
BEGIN DESCRIPTION:
XS 22
END DESCRIPTION:
XS GIS Cut Line= 5
       1036862.2        842788.7      1036775.98       842765.19
      1036728.94        842767.8      1036655.79       842791.32
      1036514.69       842801.77
#Sta/Elev= 30
  4831.3 2182.93  4838.6 2177.39  4851.4  2168.2  4857.5 2163.17  4866.6 2157.37
  4873.5 2156.44  4895.9 2154.85  4920.7 2154.03    4946 2153.97  4958.6 2153.42
  4966.7  2152.2  4967.8 2152.05  4980.8 2149.93  4987.5 2147.69  5013.4 2147.69
  5016.5 2149.13  5027.9  2151.4  5037.3 2153.29    5048 2154.93  5062.1  2156.5
  5088.1 2160.05  5127.9  2163.6  5135.3 2164.65  5147.4  2167.1  5152.1 2170.56
  5157.5 2173.68    5161 2176.03  5172.4 2182.62  5177.6 2184.79  5186.1 2187.57
#Mann= 3 ,-1 , 0
  4831.3     .07       0  4966.7     .05       0  5027.9     .07       0
Bank Sta=4967.8,5027.9
Exp/Cntr=0.3,0.1

Type RM Length L Ch R = 1 ,5969    ,182,182,182
BEGIN DESCRIPTION:
XS 21
END DESCRIPTION:
XS GIS Cut Line= 5
      1036896.16       842663.29      1036809.94       842639.77
      1036687.14       842511.75      1036650.56       842493.46
      1036568.95       842434.25
#Sta/Elev= 30
  4718.4 2191.27  4732.2 2181.16  4741.3 2175.35  4754.1 2165.88  4757.6 2162.62
  4763.8  2159.3  4770.7  2156.6  4785.3 2154.63  4809.5 2153.49  4953.7 2151.99
    4961 2151.41    4974 2149.03  4979.9 2147.76  4987.4 2147.01  4988.3 2146.18
  5012.4 2146.18  5017.8  2148.3  5026.1 2148.41  5032.7 2149.35  5046.3 2163.58
  5060.2 2176.68  5065.7 2181.49  5069.3 2184.03  5080.8 2190.83  5090.3 2194.95
  5094.5 2197.62  5098.2 2199.06  5107.5 2203.71  5113.7 2207.26  5126.9 2212.21
#Mann= 3 ,-1 , 0
  4718.4     .06       0    4974     .05       0  5032.7     .09       0
#XS Ineff= 2 , 0
       0    4850    2170               0
Permanent Ineff=
       F       F
Bank Sta=4974,5032.7
Exp/Cntr=0.3,0.1

Type RM Length L Ch R = 1 ,5787    ,264,264,264
BEGIN DESCRIPTION:
XS 20
END DESCRIPTION:
XS GIS Cut Line= 4
      1036948.42       842603.19      1036872.65       842540.49
      1036820.39       842402.01      1036778.59       842349.75
#Sta/Elev= 30
  4776.8 2194.62  4781.7 2191.79  4789.5 2186.48  4797.6 2181.45  4799.7 2180.67
  4802.9 2179.01  4809.8 2175.88  4817.5 2170.42  4825.6 2164.35  4827.5 2163.77
  4840.3    2161  4847.2 2160.19  4852.8 2158.74  4865.2 2156.58  4877.8 2154.69
  4919.4 2152.01  4926.2 2151.26  4934.5 2151.47  4949.9 2151.11  4967.3 2148.31
  4979.7 2146.62  4983.4 2145.47  5016.8 2145.47  5023.2 2148.85  5032.8 2150.08
  5034.1  2150.2  5062.7 2177.32  5076.8 2185.67  5087.4 2192.65  5090.1 2194.92
#Mann= 3 ,-1 , 0
  4776.8     .06       0  4967.3     .05       0  5032.8     .09       0
Bank Sta=4967.3,5032.8
Exp/Cntr=0.3,0.1

Type RM Length L Ch R = 1 ,5523    ,325,325,325
BEGIN DESCRIPTION:
XS 19
END DESCRIPTION:
XS GIS Cut Line= 4
      1037225.64       842519.02       1037107.8       842399.39
      1037073.84       842336.69      1037024.19       842268.75
#Sta/Elev= 30
  4780.2 2220.84  4800.3 2208.57  4812.8 2201.73    4825 2193.36  4835.3 2188.01
  4844.8 2181.95  4853.5  2175.6  4863.4 2169.18  4867.5 2166.85  4874.2 2164.53
  4877.7 2163.52  4894.8 2159.09  4901.1 2157.18  4912.1  2154.4  4920.9 2152.65
  4925.1 2151.95  4933.3 2150.98  4939.1 2149.87  4957.2 2147.73  4974.3 2144.69
  4980.7 2144.13  4983.5 2143.42  5014.9 2143.42  5018.4  2144.3  5019.5 2144.89
  5032.4 2147.73  5036.9 2154.81  5044.2 2159.27  5057.6 2170.37  5103.6 2204.13
#Mann= 3 ,-1 , 0
  4780.2     .07       0  4957.2     .05       0  5032.4     .09       0
Bank Sta=4957.2,5032.4
Exp/Cntr=0.3,0.1

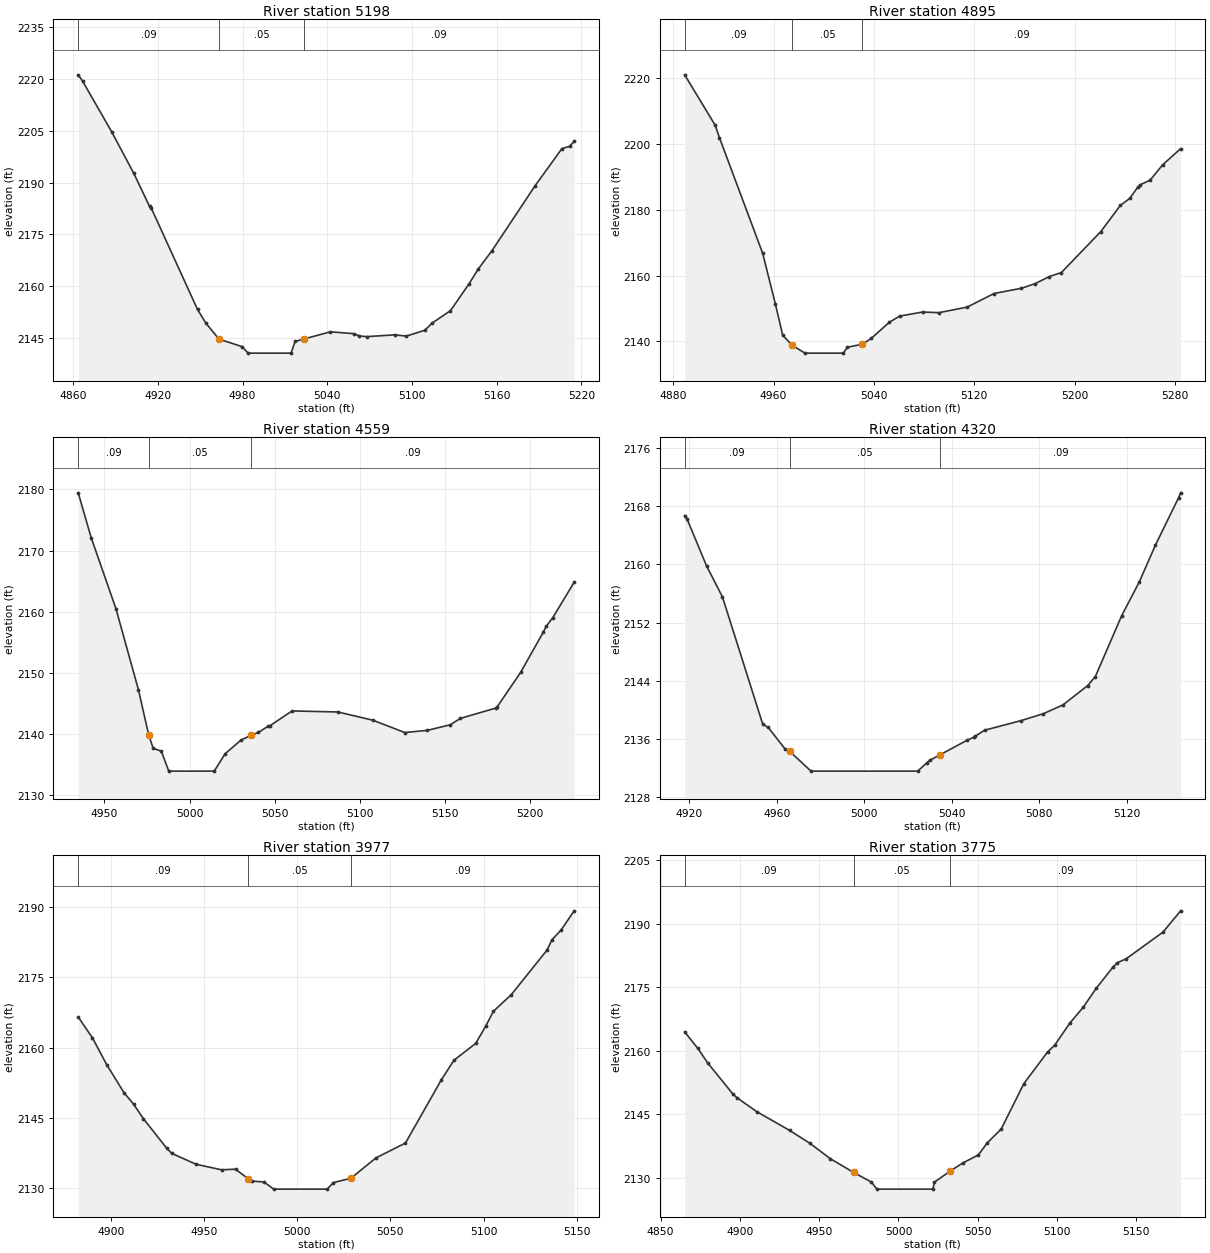
Type RM Length L Ch R = 1 ,5198    ,303,303,303
BEGIN DESCRIPTION:
XS 18
END DESCRIPTION:
XS GIS Cut Line= 4
      1037486.73       842226.28      1037379.54       842198.21
      1037329.89       842169.47       1037153.3       842121.17
#Sta/Elev= 30
  4863.6 2221.22  4866.8 2219.33  4887.3 2204.71  4902.9 2192.73  4914.1 2183.11
  4915.4 2182.54  4948.1 2153.23  4953.9 2149.34  4963.3 2144.64  4979.7 2142.45
  4983.9 2140.57  5014.4 2140.57  5017.2 2143.95  5023.8  2144.7  5042.3 2146.75
  5058.7 2146.21  5062.7 2145.55  5067.9 2145.35  5087.8 2145.87    5096  2145.5
  5109.1 2147.19  5114.2 2149.25  5127.3 2152.88  5140.5 2160.69  5146.9 2164.91
  5156.7 2170.26  5187.1 2188.99  5206.2 2199.83  5211.7  2200.5  5214.9 2201.94
#Mann= 3 ,-1 , 0
  4863.6     .09       0  4963.3     .05       0  5023.8     .09       0
Bank Sta=4963.3,5023.8
Exp/Cntr=0.3,0.1

Type RM Length L Ch R = 1 ,4895    ,336,336,336
BEGIN DESCRIPTION:
XS 17
END DESCRIPTION:
XS GIS Cut Line= 4
      1037465.26       841839.73      1037389.99       841882.06
      1037340.34        841931.7      1037129.57       842044.31
#Sta/Elev= 30
  4889.1 2221.03  4913.5 2205.65  4916.8 2201.95  4951.3 2166.78  4961.5 2151.27
  4967.3 2141.86  4974.9 2138.82    4985 2136.44  5015.7 2136.44  5018.8 2138.22
  5030.8 2139.15  5037.8 2140.89  5052.4 2145.85  5060.5 2147.69  5078.8 2148.93
  5091.9 2148.74  5114.4 2150.43  5135.8 2154.56  5157.7 2156.16  5168.6 2157.56
  5179.8  2159.7  5189.5 2160.93    5221  2173.4  5236.5 2181.32  5244.1 2183.49
  5250.5 2186.92  5252.2 2187.59  5260.3 2189.02  5270.2 2193.65  5284.6 2198.58
#Mann= 3 ,-1 , 0
  4889.1     .09       0  4974.9     .05       0  5030.8     .09       0
Bank Sta=4974.9,5030.8
Exp/Cntr=0.3,0.1

Type RM Length L Ch R = 1 ,4559    ,239,239,239
BEGIN DESCRIPTION:
XS 16
END DESCRIPTION:
XS GIS Cut Line= 4
      1037120.87       841652.13      1037097.35       841704.39
      1037079.06       841759.25        1036985.       841908.19
#Sta/Elev= 29
  4934.6 2179.45  4942.2 2172.12  4956.8 2160.44    4970 2147.16    4976 2139.78
  4978.6 2137.61  4983.4 2137.13  4987.8 2133.86  5014.5 2133.86  5020.9 2136.71
  5030.2 2138.94    5036 2139.72  5040.4 2140.19  5046.3 2141.25  5047.3 2141.31
  5060.2 2143.72  5087.1 2143.55  5107.7  2142.2  5126.4 2140.18  5139.7 2140.54
  5153.2 2141.46  5159.1  2142.5    5180  2144.2  5180.5 2144.32  5194.5 2150.05
  5207.8 2156.64  5209.4 2157.56  5213.3 2158.98  5225.9  2164.8
#Mann= 3 ,-1 , 0
  4934.6     .09       0    4976     .05       0    5036     .09       0
Bank Sta=4976,5036
Exp/Cntr=0.3,0.1

Type RM Length L Ch R = 1 ,4320    ,343,343,343
BEGIN DESCRIPTION:
XS 15
END DESCRIPTION:
XS GIS Cut Line= 4
      1036846.52       841665.19      1036870.04       841720.06
      1036893.55       841772.32      1036888.33       841882.06
#Sta/Elev= 27
  4917.8 2166.69  4918.9 2166.21  4927.8 2159.79  4935.1  2155.5  4953.5 2138.04
    4956 2137.59  4963.7 2134.64  4965.9 2134.28  4975.6 2131.58  5024.4 2131.58
  5028.5 2132.69    5030 2133.07  5034.8 2133.85  5047.1 2135.84  5050.1 2136.24
  5050.7 2136.37    5055  2137.2  5071.8 2138.53  5081.9 2139.47  5090.9 2140.68
  5102.2 2143.34  5105.7 2144.58  5117.7 2152.92  5125.8 2157.58  5133.2 2162.65
  5143.8 2169.17  5144.7 2169.82
#Mann= 3 ,-1 , 0
  4917.8     .09       0  4965.9     .05       0  5034.8     .09       0
Bank Sta=4965.9,5034.8
Exp/Cntr=0.3,0.1

Type RM Length L Ch R = 1 ,3977    ,202,202,202
BEGIN DESCRIPTION:
XS 14
END DESCRIPTION:
XS GIS Cut Line= 4
      1036559.11       841720.06      1036561.72       841801.06
      1036551.27       841855.93       1036537.3        841984.4
#Sta/Elev= 30
  4882.5 2166.54  4890.1 2162.11  4897.9  2156.3  4907.1 2150.39  4912.3 2147.92
  4917.4  2144.9  4930.1 2138.51  4932.7 2137.47  4945.8 2135.14  4959.4 2133.97
  4966.9  2134.1  4973.6 2132.09  4975.9 2131.55  4982.1 2131.38  4987.4 2129.85
  5016.1 2129.85  5019.4 2131.24  5028.8 2132.16  5042.2 2136.49  5058.1 2139.68
  5077.4 2153.18  5084.1 2157.32  5095.8 2160.92  5101.3  2164.7  5105.3 2167.77
  5114.9 2171.31    5134 2180.78  5136.7    2183  5141.6 2185.07  5148.6 2189.17
#Mann= 3 ,-1 , 0
  4882.5     .09       0  4973.6     .05       0  5028.8     .09       0
Bank Sta=4973.6,5028.8
Exp/Cntr=0.3,0.1

Type RM Length L Ch R = 1 ,3775    ,412,412,412
BEGIN DESCRIPTION:
XS 13
END DESCRIPTION:
XS GIS Cut Line= 4
      1036483.34       841665.19      1036410.18         841707.
      1036360.54       841764.48      1036229.87       841843.12
#Sta/Elev= 30
  4865.2 2164.44  4873.5 2160.56  4879.6 2157.18  4895.7 2149.72  4898.2 2148.88
  4910.7 2145.59  4931.3 2141.18    4944 2138.16  4957.1 2134.46  4971.7 2131.24
  4982.9 2128.96  4986.4 2127.29  5021.7 2127.29  5022.7 2128.95  5032.8  2131.6
  5040.6 2133.48  5050.4 2135.37  5055.9 2138.19  5064.8  2141.5  5079.1 2152.25
    5094  2159.7  5098.5 2161.31  5107.9 2166.46  5116.6 2170.33  5124.6 2174.72
  5135.4 2179.84  5138.1 2180.83  5143.5 2181.72  5166.8 2188.04  5177.9 2193.07
#Mann= 3 ,-1 , 0
  4865.2     .09       0  4971.7     .05       0  5032.8     .09       0
Bank Sta=4971.7,5032.8
Exp/Cntr=0.3,0.1

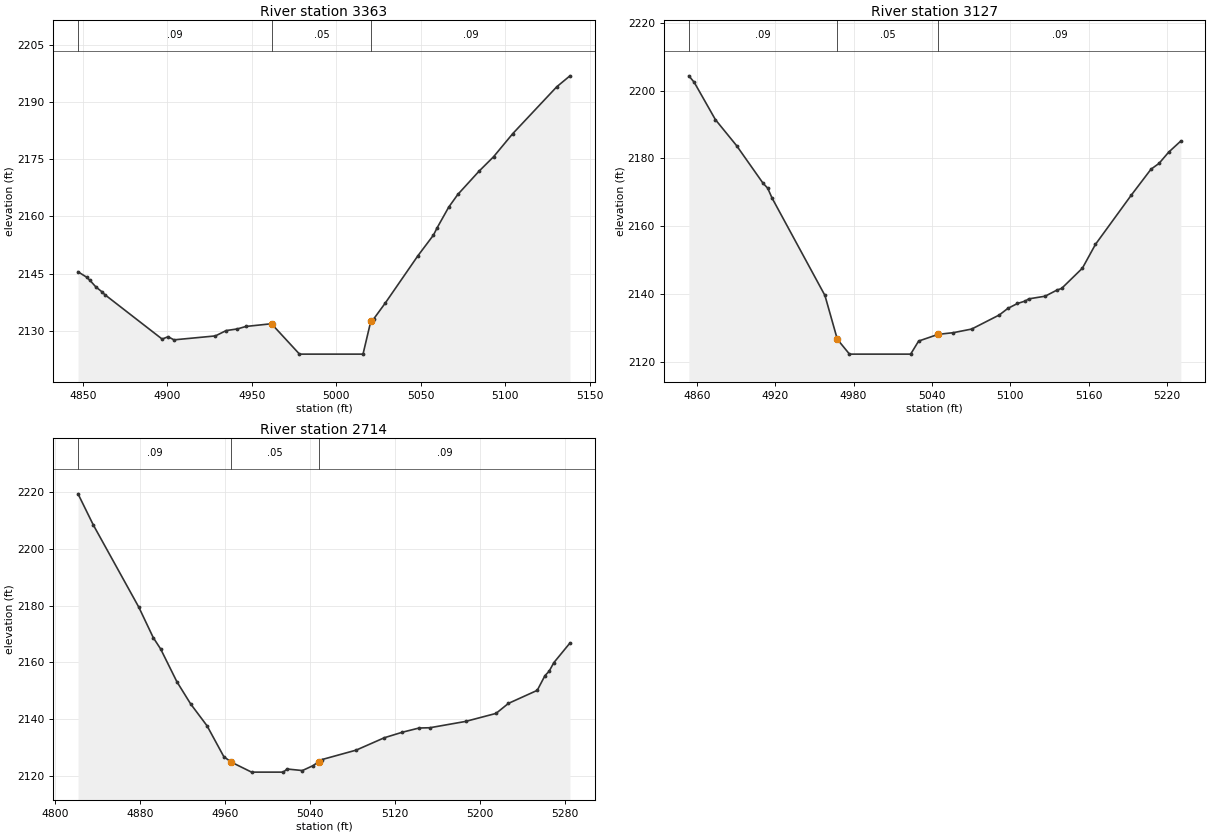
Type RM Length L Ch R = 1 ,3363    ,236,236,236
BEGIN DESCRIPTION:
XS 12
END DESCRIPTION:
XS GIS Cut Line= 4
      1036478.11       841390.85      1036370.99       841369.95
      1036303.06       841343.82      1036195.96       841322.06
#Sta/Elev= 30
  4847.2 2145.51  4852.3  2144.1  4854.3 2143.25  4857.8 2141.53  4861.3 2140.29
    4863 2139.55    4897 2127.88  4900.5  2128.5    4904 2127.68  4928.5 2128.71
  4934.9 2130.11  4941.5 2130.54  4946.6 2131.19  4961.5 2131.89  4961.9 2131.81
  4978.3 2123.94  5015.9 2123.94  5020.6 2132.74  5022.4 2133.27  5029.1 2137.34
  5048.4 2149.72  5057.6 2155.13  5059.7 2156.98  5066.6 2162.43    5072 2165.77
  5084.6 2171.88  5093.2 2175.66  5104.5 2181.69  5130.6 2193.99  5138.4 2196.85
#Mann= 3 ,-1 , 0
  4847.2     .09       0  4961.9     .05       0  5020.6     .09       0
Bank Sta=4961.9,5020.6
Exp/Cntr=0.3,0.1

Type RM Length L Ch R = 1 ,3127    ,413,413,413
BEGIN DESCRIPTION:
XS 11
END DESCRIPTION:
XS GIS Cut Line= 4
      1036516.86       841063.11      1036407.57       841121.73
      1036347.47       841150.47      1036203.77       841268.05
#Sta/Elev= 30
    4854 2204.34  4858.1 2202.43  4874.3 2191.44  4890.5 2183.78  4910.8 2172.67
  4914.3 2171.25  4917.6 2168.37  4958.1 2139.63  4967.6  2126.7  4976.9 2122.33
  5023.7 2122.33  5029.8 2126.18  5044.7 2128.15  5056.3 2128.65  5070.4 2129.72
  5091.6 2133.89    5098 2135.79  5105.4 2137.25  5111.5 2137.99    5114 2138.61
  5126.6  2139.4  5135.6  2141.2  5139.2 2141.69  5155.1 2147.66  5165.1 2154.68
  5192.5 2169.18  5207.6 2176.83  5213.7 2178.52  5221.1 2181.84  5230.4 2185.13
#Mann= 3 ,-1 , 0
    4854     .09       0  4967.6     .05       0  5044.7     .09       0
Bank Sta=4967.6,5044.7
Exp/Cntr=0.3,0.1

Type RM Length L Ch R = 1 ,2714    ,441,441,441
BEGIN DESCRIPTION:
XS 10
END DESCRIPTION:
XS GIS Cut Line= 5
      1036091.34        840736.3      1036060.06        840870.9
      1036060.06       840957.12      1036052.23       841106.05
      1036028.71       841192.27
#Sta/Elev= 30
  4821.7 2219.42  4836.1 2208.43  4878.9 2179.43  4892.5 2168.69  4899.4 2164.72
  4914.7 2153.15  4927.7 2145.29  4943.1 2137.59  4958.9  2126.7  4965.9 2124.77
    4985 2121.24  5014.9 2121.24  5018.4 2122.34  5032.8  2121.8    5043 2123.55
  5048.2 2124.97  5051.4 2125.69  5083.4    2129    5110 2133.38  5126.9 2135.32
  5142.6  2136.8  5152.8  2136.9  5186.3 2139.12    5215 2141.95  5226.7 2145.49
  5253.8 2150.09  5261.1 2155.31  5264.9 2156.78  5269.4 2159.85  5284.6  2166.8
#Mann= 3 ,-1 , 0
  4821.7     .09       0  4965.9     .05       0  5048.2     .09       0
Bank Sta=4965.9,5048.2
Exp/Cntr=0.3,0.1