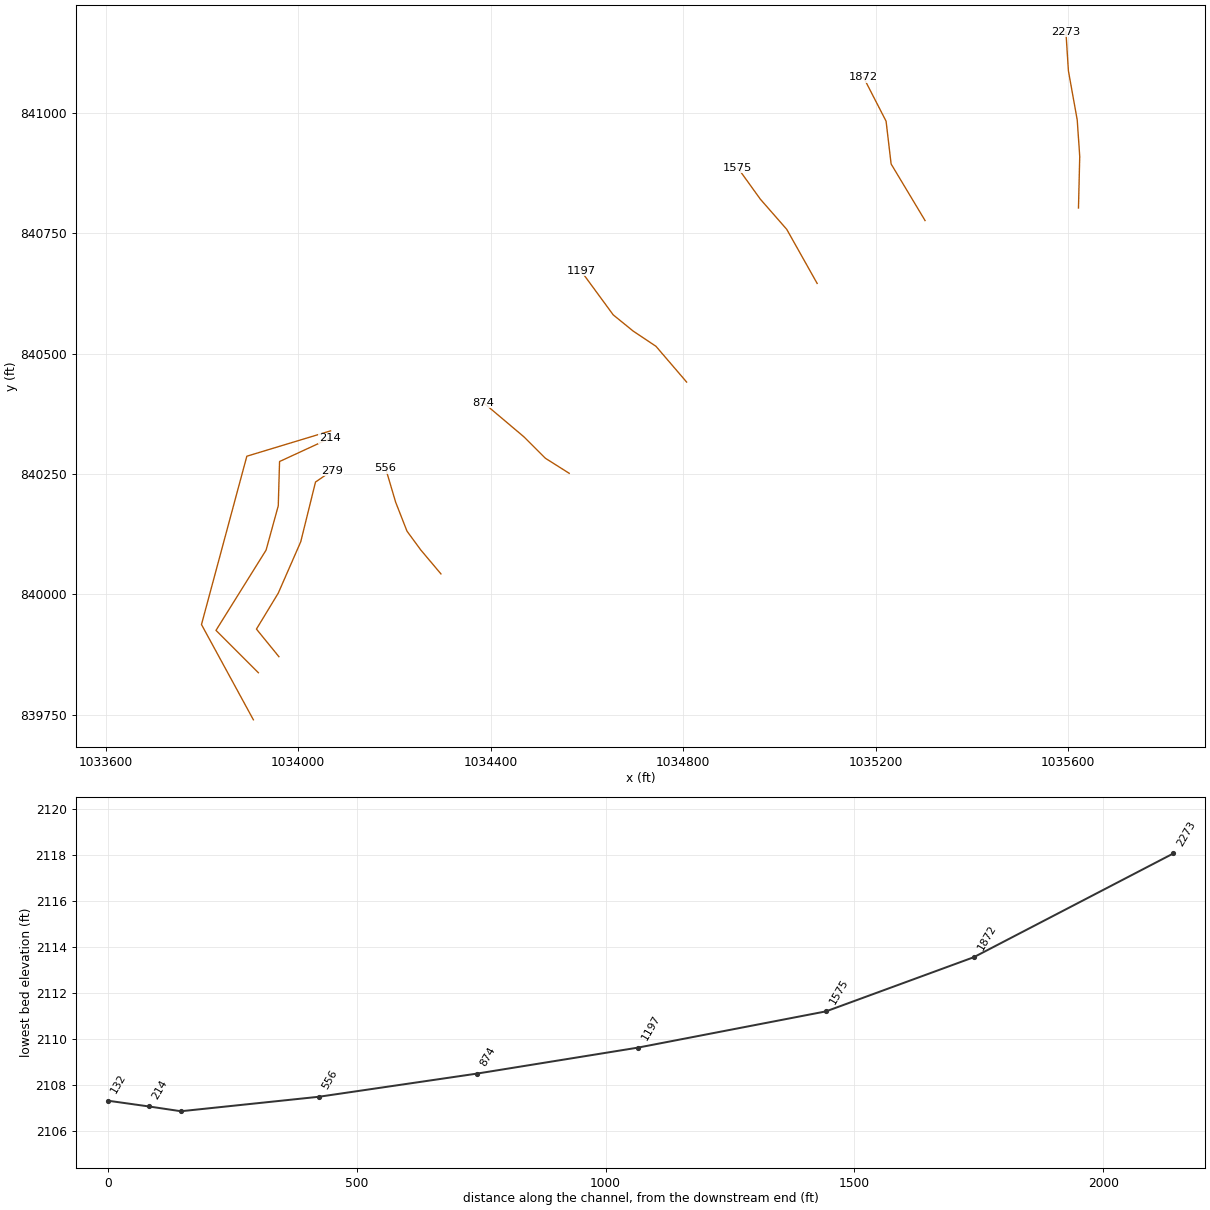
HEC-RAS study lds_big_rock_crk.prj: Big Rock Creek Limited Detail Study

--- lds_big_rock_crk.g01 (geometry) --- (continued)

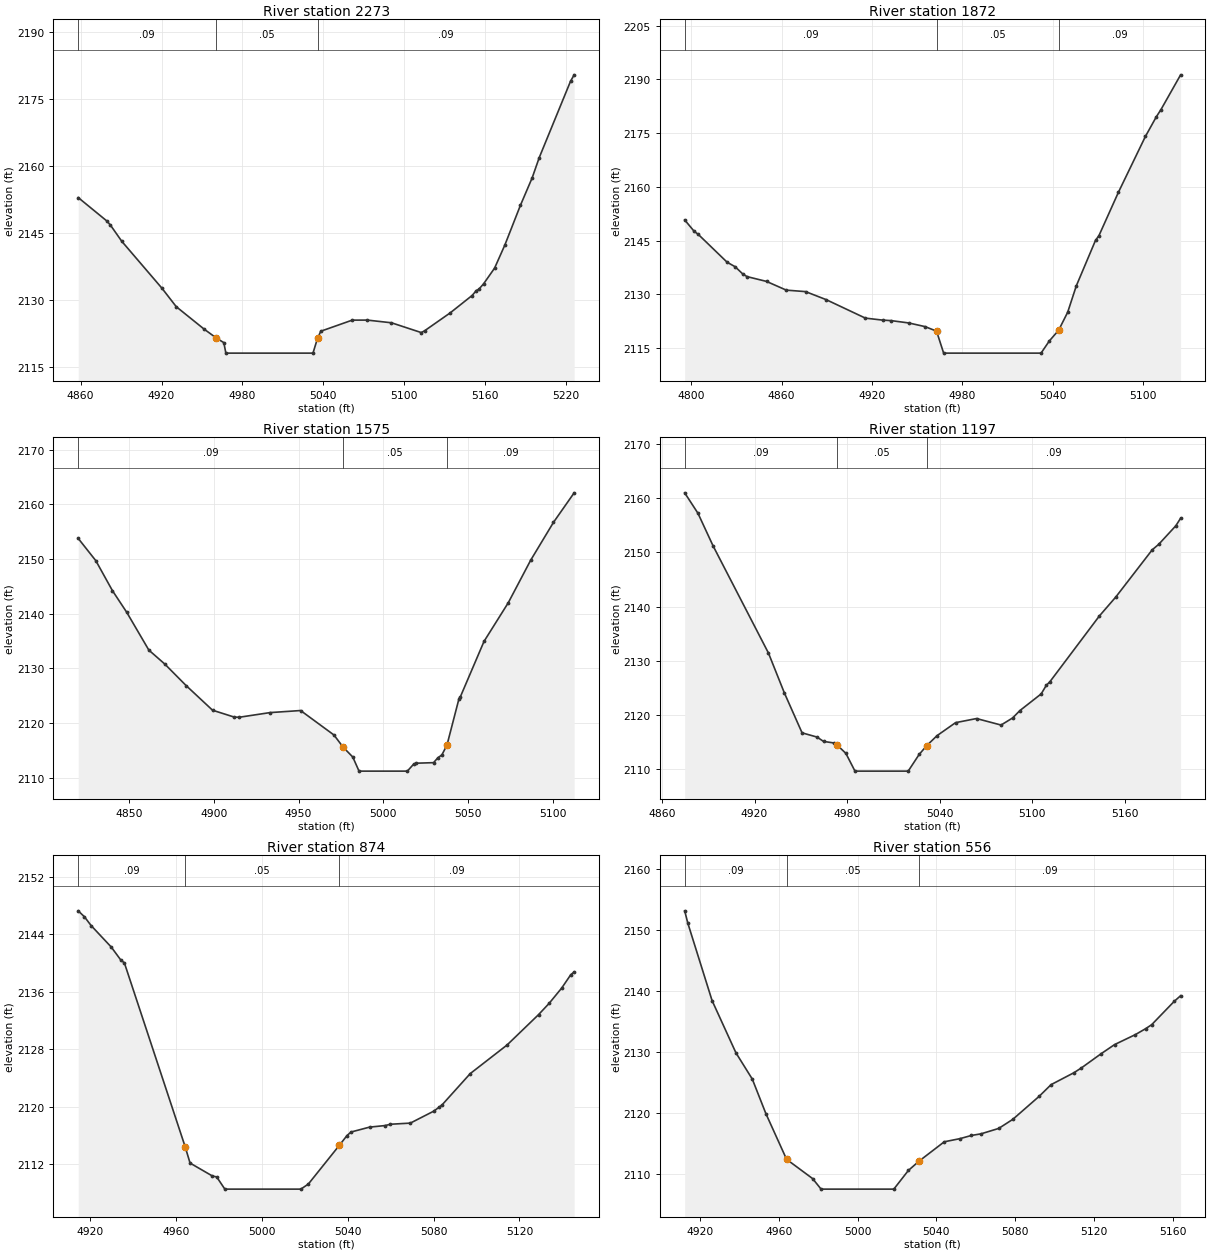
Type RM Length L Ch R = 1 ,2273    ,401,401,401
BEGIN DESCRIPTION:
XS 9
END DESCRIPTION:
XS GIS Cut Line= 5
      1035621.11       840802.96      1035623.72       840910.09
       1035618.5       840985.86      1035600.21       841087.76
      1035594.98       841168.76
#Sta/Elev= 30
  4858.2 2152.88  4879.4 2147.65  4882.1 2146.72  4890.5  2143.1  4920.3  2132.6
  4930.9 2128.47  4951.7 2123.42  4960.6 2121.47  4966.2 2120.42  4967.7 2118.08
  5032.3 2118.08  5035.7 2121.41  5038.1 2122.98  5061.4 2125.46  5072.6 2125.47
  5090.5 2124.87  5112.6 2122.68  5115.1 2123.08  5134.1 2127.09  5150.3 2130.97
  5153.5 2132.09  5155.2 2132.34  5158.8 2133.57    5167  2137.1  5174.6 2142.26
  5186.1 2151.11  5194.9 2157.32  5200.1 2161.82  5223.3 2178.89    5226 2180.34
#Mann= 3 ,-1 , 0
  4858.2     .09       0  4960.6     .05       0  5035.7     .09       0
Bank Sta=4960.6,5035.7
Exp/Cntr=0.3,0.1

Type RM Length L Ch R = 1 ,1872    ,297,297,297
BEGIN DESCRIPTION:
XS 8
END DESCRIPTION:
XS GIS Cut Line= 4
      1035302.35       840776.84       1035231.8       840894.41
      1035221.35       840983.25      1035174.32        841074.7
#Sta/Elev= 30
  4795.6 2150.76  4801.9 2147.58  4804.6 2146.73  4823.8 2138.94  4829.1 2137.69
  4834.2 2135.66    4837 2134.93    4850 2133.58  4863.1 2131.15  4875.9 2130.74
  4889.5 2128.51  4915.6 2123.34    4927 2122.78  4932.7 2122.64  4944.4 2121.99
  4955.2 2120.97  4962.9  2119.7  4967.6 2113.56  5032.3 2113.56  5037.8 2116.96
    5044 2119.97    5050 2124.99  5055.7 2132.33  5068.5 2145.08  5070.7 2146.33
  5083.7 2158.49  5101.6 2174.06  5108.9 2179.59  5111.9 2181.54    5125 2191.28
#Mann= 3 ,-1 , 0
  4795.6     .09       0  4962.9     .05       0    5044     .09       0
Bank Sta=4962.9,5044
Exp/Cntr=0.3,0.1

Type RM Length L Ch R = 1 ,1575    ,378,378,378
BEGIN DESCRIPTION:
XS 7
END DESCRIPTION:
XS GIS Cut Line= 4
      1035078.12       840646.16      1035014.94       840758.55
      1034960.07       840821.25      1034913.04       840886.57
#Sta/Elev= 30
  4819.9 2153.79  4830.3 2149.71  4840.1 2144.23  4848.5 2140.29  4861.6 2133.35
    4871  2130.8  4883.6 2126.86  4899.2 2122.35    4912 2121.09    4915 2121.06
  4933.1 2121.91  4951.2 2122.29  4970.9 2117.81  4976.3 2115.59    4982 2113.78
  4985.7  2111.2  5014.2  2111.2  5017.9 2112.46  5019.5 2112.65  5029.7 2112.75
  5032.2 2113.63  5034.6 2114.17  5037.6 2115.95  5044.7 2124.45  5045.5 2124.79
  5059.5 2134.95  5073.8 2142.01    5087 2149.78  5100.5 2156.73  5112.7 2162.13
#Mann= 3 ,-1 , 0
  4819.9     .09       0  4976.3     .05       0  5037.6     .09       0
Bank Sta=4976.3,5037.6
Exp/Cntr=0.3,0.1

Type RM Length L Ch R = 1 ,1197    ,323,323,323
BEGIN DESCRIPTION:
XS 6
END DESCRIPTION:
XS GIS Cut Line= 5
      1034806.89       840441.26       1034743.2       840515.55
      1034696.17       840546.91      1034654.37       840580.87
      1034587.44       840672.18
#Sta/Elev= 30
  4874.7 2161.01  4883.3 2157.24  4893.1 2151.22    4929 2131.43  4939.3 2124.08
  4950.8 2116.69  4960.5 2115.91  4964.7 2115.11  4971.7 2114.81  4973.6 2114.42
  4979.2  2112.9  4985.1 2109.62  5019.6 2109.62  5026.7  2112.7  5031.6 2114.33
  5038.3 2116.17  5050.3 2118.57  5063.9 2119.33  5079.8 2118.13  5087.3 2119.44
    5092  2120.8  5105.8 2123.88  5109.1 2125.45  5111.5 2126.14  5143.5 2138.26
  5154.2 2141.78  5177.8 2150.49    5182  2151.5  5193.1 2154.93  5196.2 2156.32
#Mann= 3 ,-1 , 0
  4874.7     .09       0  4973.6     .05       0  5031.6     .09       0
Bank Sta=4973.6,5031.6
Exp/Cntr=0.3,0.1

Type RM Length L Ch R = 1 ,874     ,318,318,318
BEGIN DESCRIPTION:
XS 5
END DESCRIPTION:
XS GIS Cut Line= 4
      1034562.92       840251.66      1034513.28       840283.01
      1034468.86       840327.43      1034385.25       840397.98
#Sta/Elev= 30
  4914.5 2147.27  4917.4 2146.44  4920.5 2145.22  4929.9 2142.22  4934.4 2140.39
    4936 2140.02  4964.3 2114.41  4966.6 2112.12    4977 2110.32    4979 2110.19
  4982.8 2108.49  5018.2 2108.49  5021.7  2109.2  5036.1 2114.58  5039.7 2115.96
  5041.6 2116.45  5050.2 2117.13  5057.5 2117.35  5059.9 2117.53  5069.2 2117.69
    5080 2119.34  5082.5 2119.88  5084.1 2120.27  5097.1 2124.59  5114.2 2128.56
  5128.9  2132.8  5133.8 2134.36  5139.7 2136.51  5143.9 2138.36  5145.5 2138.75
#Mann= 3 ,-1 , 0
  4914.5     .09       0  4964.3     .05       0  5036.1     .09       0
Bank Sta=4964.3,5036.1
Exp/Cntr=0.3,0.1

Type RM Length L Ch R = 1 ,556     ,277,277,277
BEGIN DESCRIPTION:
XS 4
END DESCRIPTION:
XS GIS Cut Line= 5
      1034296.41       840042.63      1034254.61       840092.28
      1034225.87       840131.47      1034202.35       840191.57
      1034181.45       840262.11
#Sta/Elev= 29
  4912.3 2153.15  4913.9 2151.12  4926.2 2138.42  4938.3 2129.85  4946.6 2125.54
  4953.5 2119.87    4964 2112.37  4977.2 2109.21  4981.5 2107.48  5018.4 2107.48
  5025.8 2110.55  5031.3  2112.1    5044 2115.25  5051.9 2115.76  5057.8 2116.29
  5062.6 2116.55  5071.6 2117.44  5078.8 2118.94  5092.1  2122.7  5098.2 2124.63
  5109.7 2126.57  5113.6 2127.38  5123.7 2129.73  5130.4  2131.2  5140.9 2132.83
  5146.1  2133.8  5149.2 2134.46  5160.7 2138.31  5163.9 2139.22
#Mann= 3 ,-1 , 0
  4912.3     .09       0    4964     .05       0  5031.3     .09       0
Bank Sta=4964,5031.3
Exp/Cntr=0.5,0.3

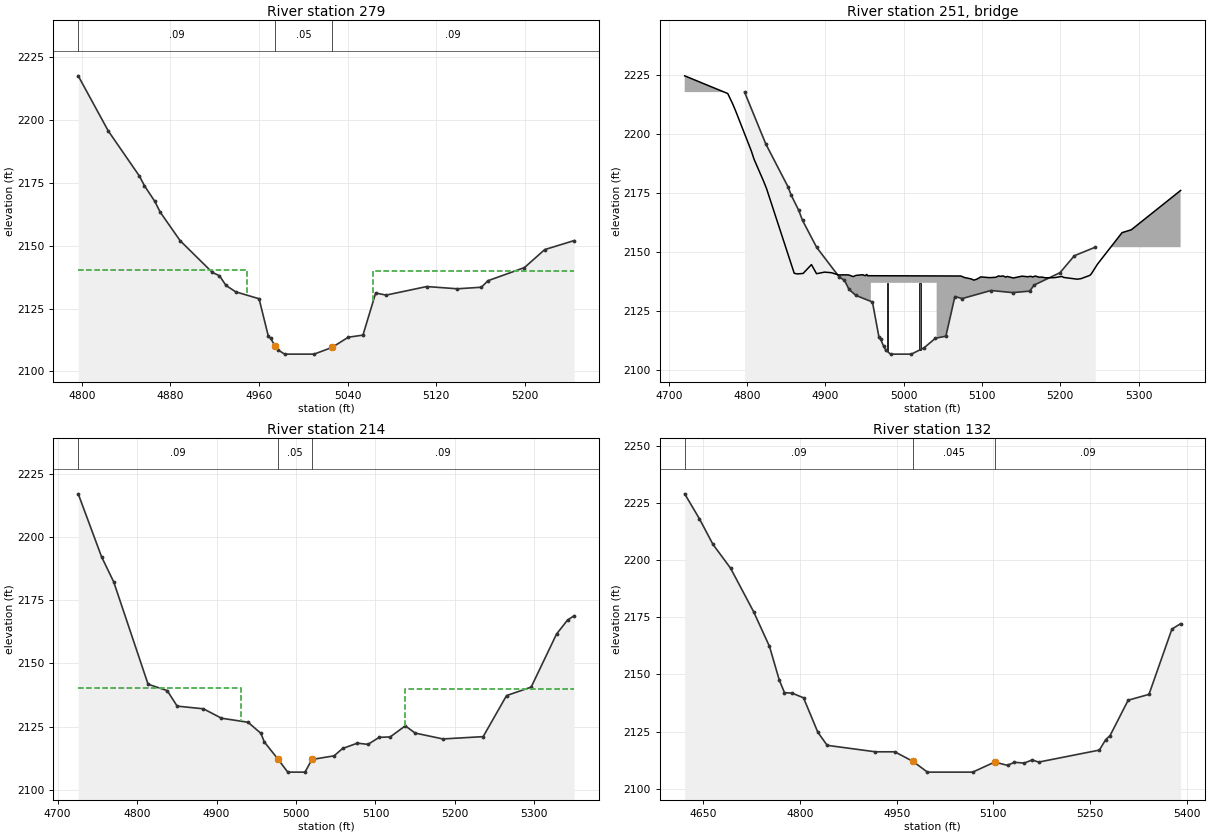
Type RM Length L Ch R = 1 ,279     ,65,65,65
BEGIN DESCRIPTION:
XS 3
END DESCRIPTION:
XS GIS Cut Line= 6
      1033959.77        839870.6      1033913.08       839927.95
      1033958.43       840002.65      1034005.12       840109.37
       1034035.8       840233.42      1034070.48       840257.43
#Sta/Elev= 30
  4796.7 2217.62  4823.8 2195.71    4852  2177.7  4856.4 2173.95  4865.9 2167.61
  4870.7 2163.39  4888.8 2151.97  4917.9 2139.34  4924.2 2138.08  4930.1  2134.2
  4938.9 2131.65    4960 2128.89  4968.4 2113.93  4970.5 2113.11 4974.28 2110.18
  4976.9  2108.6  4983.1 2106.85  5009.7 2106.85  5025.9 2109.52  5040.5 2113.57
  5053.8 2114.42  5065.3 2131.19  5074.7 2130.34  5111.4 2133.75    5139 2132.86
  5160.7 2133.47  5166.7 2136.07  5199.6 2141.29  5217.9 2148.45  5244.5 2152.05
#Mann= 3 , 0 , 0
  4796.7     .09       0 4974.28     .05       0  5025.9     .09       0
#XS Ineff= 2 , 0
       0    4949 2140.18    5063       0    2140
Permanent Ineff=
       F       F
Bank Sta=4974.28,5025.9
Exp/Cntr=0.5,0.3

Type RM Length L Ch R = 3 ,251     ,,,
BEGIN DESCRIPTION:
XS 2 TOR
Structure ID: XS 2
Approximate Survey Structure
END DESCRIPTION:
Bridge Culvert--1,0,-1,-1, 0
Deck Dist Width WeirC Skew NumUp NumDn MinLoCord MaxHiCord MaxSubmerge Is_Ogee
18,20,3,0, 60, 60, , , , 0, 1,1,,
  4720.2  4775.2  4781.4  4785.1  4805.3  4808.8    4821  4824.8  4860.1    4864
  4871.4  4882.1  4888.6  4898.9  4907.8  4916.5  4929.3  4935.5  4938.9  4947.7
  4950.4  4952.9  4953.5    4958    4958    5042    5042    5073  5077.5  5086.1
  5089.6  5093.2  5098.3  5109.6  5117.5  5121.2    5123  5126.9  5130.3  5131.9
    5140    5151  5158.2  5162.1  5164.8  5168.1  5172.6  5176.3  5181.1  5192.4
  5202.1  5204.2  5221.6  5226.5  5237.7  5239.6  5247.4  5278.8  5290.6  5353.6
 2224.51 2217.02 2212.71 2209.82 2192.75 2189.24 2179.93 2176.79 2141.03 2140.77
 2140.95  2144.7 2140.85 2141.52 2141.26 2140.34 2140.36 2139.63 2140.14 2140.42
 2140.01 2140.56    2140    2140    2140 2139.91 2139.91 2139.88 2139.24 2138.65
 2138.14 2138.52  2139.5 2139.18 2139.34 2139.93 2139.74 2139.91 2139.38 2139.71
 2139.04 2139.82 2139.56 2139.76 2139.47 2139.89 2139.37 2139.43 2139.11 2139.18
 2139.69 2139.28 2138.53 2138.77 2140.15 2140.82 2144.88 2158.21 2159.42 2176.05
 2087.31 2087.31 2087.31 2087.31 2087.31 2087.31 2087.31 2087.31 2087.31 2087.31
 2087.31 2087.31 2087.31 2087.31 2087.31 2087.31 2087.31 2087.31 2087.31 2087.31
 2087.31 2087.31 2087.31 2087.31    2137    2137 2087.31 2087.31 2087.31 2087.31
 2087.31 2087.31 2087.31 2087.31 2087.31 2087.31 2087.31 2087.31 2087.31 2087.31
 2087.31 2087.31 2087.31 2087.31 2087.31 2087.31 2087.31 2087.31 2087.31 2087.31
 2087.31 2087.31 2087.31 2087.31 2087.31 2087.31 2087.31 2087.31 2087.31 2087.31
  4720.2  4775.2  4781.4  4785.1  4805.3  4808.8    4821  4824.8  4860.1    4864
  4871.4  4882.1  4888.6  4898.9  4907.8  4916.5  4929.3  4935.5  4938.9  4947.7
  4950.4  4952.9  4953.5    4958    4958    5042    5042    5073  5077.5  5086.1
  5089.6  5093.2  5098.3  5109.6  5117.5  5121.2    5123  5126.9  5130.3  5131.9
    5140    5151  5158.2  5162.1  5164.8  5168.1  5172.6  5176.3  5181.1  5192.4
  5202.1  5204.2  5221.6  5226.5  5237.7  5239.6  5247.4  5278.8  5290.6  5353.6
 2224.51 2217.02 2212.71 2209.82 2192.75 2189.24 2179.93 2176.79 2141.03 2140.77
 2140.95  2144.7 2140.85 2141.52 2141.26 2140.34 2140.36 2139.63 2140.14 2140.42
 2140.01 2140.56    2140    2140    2140 2139.91 2139.91 2139.88 2139.24 2138.65
 2138.14 2138.52  2139.5 2139.18 2139.34 2139.93 2139.74 2139.91 2139.38 2139.71
 2139.04 2139.82 2139.56 2139.76 2139.47 2139.89 2139.37 2139.43 2139.11 2139.18
 2139.69 2139.28 2138.53 2138.77 2140.15 2140.82 2144.88 2158.21 2159.42 2176.05
 2087.31 2087.31 2087.31 2087.31 2087.31 2087.31 2087.31 2087.31 2087.31 2087.31
 2087.31 2087.31 2087.31 2087.31 2087.31 2087.31 2087.31 2087.31 2087.31 2087.31
 2087.31 2087.31 2087.31 2087.31    2137    2137 2087.31 2087.31 2087.31 2087.31
 2087.31 2087.31 2087.31 2087.31 2087.31 2087.31 2087.31 2087.31 2087.31 2087.31
 2087.31 2087.31 2087.31 2087.31 2087.31 2087.31 2087.31 2087.31 2087.31 2087.31
 2087.31 2087.31 2087.31 2087.31 2087.31 2087.31 2087.31 2087.31 2087.31 2087.31
Pier Skew, UpSta & Num, DnSta & Num=  ,4979, 2 ,4979, 2 , 0 , 0 , 0 ,0,0
       2       2
    2108    2137
       2       2
 2111.75    2137
Pier Skew, UpSta & Num, DnSta & Num=  ,5021, 2 ,5021, 2 , 0 , 0 , 0 ,0,0
       2       2
    2108    2137
       2       2
    2112    2137
BR Coef= 1 , 1 , 0 ,1.25, 0 ,,,0.8,0,2,0,
WSPro=,,,, 1 ,,,, 0 ,,,, 0 ,,,,-1 ,-1 ,-1 , 0 , 0 , 0 , 0 , 0
BC Design=,, 0 ,, 0 ,,,,,,
BC HTab HWMax=2217.62

Type RM Length L Ch R = 1 ,214     ,82,82,82
BEGIN DESCRIPTION:
XS 1
END DESCRIPTION:
XS GIS Cut Line= 6
      1033917.08       839837.25      1033829.05       839925.29
      1033933.09       840092.02      1033958.43       840184.06
       1033961.1        840276.1      1034065.15       840324.12
#Sta/Elev= 30
  4725.9    2217  4755.3 2192.12  4770.6 2182.19  4813.8  2141.8  4837.9 2139.26
  4850.4 2133.14  4883.5 2132.07  4906.2 2128.36  4939.6 2126.76  4955.8 2122.39
  4960.1 2118.97  4976.7 2112.44  4989.6 2107.06  5011.3 2107.06    5020 2112.06
  5047.9  2113.5  5058.6  2116.4  5077.3 2118.51  5090.5 2118.02  5104.7 2120.81
  5118.5 2120.96  5137.5 2125.34    5150 2122.48  5184.9 2120.17  5235.5 2121.08
  5264.9 2137.29  5295.9 2140.65  5327.8 2161.58  5341.7 2167.15    5350 2168.85
#Mann= 3 ,-1 , 0
  4725.9     .09       0  4976.7     .05       0    5020     .09       0
#XS Ineff= 2 , 0
       0    4931 2140.16  5137.5       0    2140
Permanent Ineff=
       F       F
Bank Sta=4976.7,5020
Exp/Cntr=0.5,0.3

Type RM Length L Ch R = 1 ,132     ,0,0,0
BEGIN DESCRIPTION:
backwaterxs
END DESCRIPTION:
XS GIS Cut Line= 4
      1033906.72       839739.47      1033798.87       839937.38
      1033893.11       840287.13      1034067.21       840339.86
#Sta/Elev= 30
    4621    2229  4643.9 2218.08  4664.9 2206.89  4692.3 2196.44  4727.8 2177.54
  4752.6 2162.28  4767.6 2147.74  4775.8 2142.08  4787.8 2141.83  4805.4 2139.81
  4827.6 2124.75  4842.1 2119.03  4916.9  2116.2  4946.9  2116.2  4975.2 2112.02
  4997.7 2107.31  5067.9 2107.31  5101.8 2111.69  5121.9 2110.29  5132.7 2111.61
  5147.8 2111.26  5160.3 2112.66  5170.1 2111.69  5264.4 2116.95  5274.3 2121.53
  5280.9 2123.22  5309.1 2138.76  5341.4 2141.31    5377 2169.86  5390.5 2172.22
#Mann= 3 ,-1 , 0
    4621     .09       0  4975.2    .045       0  5101.8     .09       0
Bank Sta=4975.2,5101.8
Exp/Cntr=0.3,0.1
Stream Node=Big Rock Creek  ,Reach-1         , 0 , 0 ,Upstream end
Stream Node=Big Rock Creek  ,Reach-1         , 0 , 1 ,Downstream end

Chan Stop Cuts=-1
Use User Specified Reach Order=0
User Specified Reach Order=Big Rock Creek  ,Reach-1