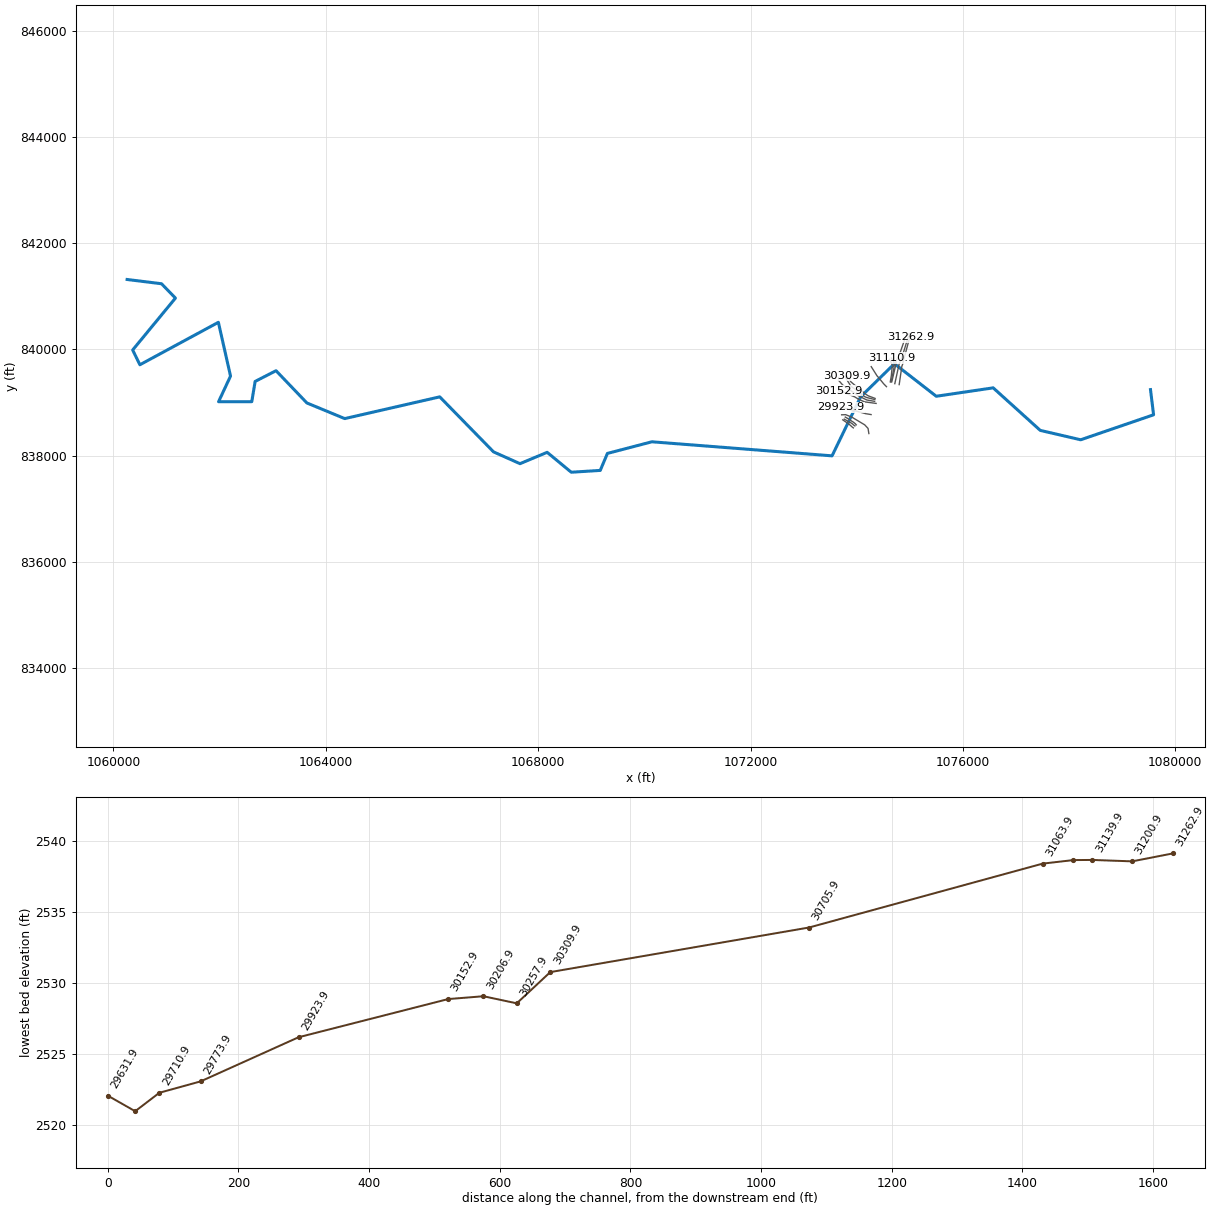
--- dtl_cane_crk.prj (project) ---

Proj Title=cane creek
Current Plan=p01
Default Exp/Contr=0.3,0.1
English Units
Geom File=g01
Flow File=f01
Plan File=p01
Y Axis Title=Elevation
X Axis Title(PF)=Main Channel Distance
X Axis Title(XS)=Station
BEGIN DESCRIPTION:
dtl of cane creek
END DESCRIPTION:
DSS File=dss
DSS Export Rating Curves= 0
DSS Export Rating Curve Sorted= 0
DSS Export Volume Flow Curves= 0
DXF OffsetX= 0
DXF OffsetY= 0
DXF ScaleX= 1
DXF ScaleY= 10

--- dtl_cane_crk.p01 (plan) ---

Plan Title=detail_cane_creek
Program Version=3.13
Short Identifier=floodway
Geom File=g01
Flow File=f01
Subcritical Flow
K Sum by GR= 0
Std Step Tol= 0.01
Critical Tol= 0.01
Num of Std Step Trials= 20
Max Error Tol= 0.3
Flow Tol Ratio= 0.001
Split Flow NTrial= 30
Split Flow Tol= 0.02
Split Flow Ratio= 0.02
Log Output Level= 0
Friction Slope Method= 0
Unsteady Friction Slope Method= 2
Unsteady Bridges Friction Slope Method= 1
Parabolic Critical Depth
Global Vel Dist= 0 , 0 , 0
Global Log Level= 0
CheckData=True
Encroach Param=-1 ,5,5, 2
Encroach River=river
Encroach Reach=main
Encroach Node=31262.9
       1  331.83  499.77
Encroach Node=31200.9
       1  335.81     515
Encroach Node=31139.9
       1  320.86  479.17
Encroach Node=31110.9
       1     310  424.58
Encroach Node=31063.9
       1  303.33  384.59
Encroach Node=30705.9
       1  185.94  324.34
Encroach Node=30309.9
       1  223.28  374.71
Encroach Node=30257.9
       1  231.32  426.08
Encroach Node=30206.9
       1  253.24  448.76
Encroach Node=30152.9
       1  292.66     498
Encroach Node=29923.9
       1  252.67  462.34
Encroach Node=29773.9
       1     391   573.2
Encroach Node=29710.9
       1   76.36  214.01
Encroach Node=29673.9
       1   61.79  188.03
Encroach Node=29631.9
       1   73.72  174.13
Encroach Node=29422.9
       1     220  311.14
Encroach Node=29130.9
       1     200  293.06
Encroach Node=28599.9
       1  177.05  277.77
Encroach Node=28543.9
       1  155.25  295.45
Encroach Node=28518.9
       1  161.97  302.17
Encroach Node=28441.9
       1  199.31  332.71
Encroach Node=28176.9
       1  227.08  333.02
Encroach Node=27766.9
       1  357.53  578.28
Encroach Node=27342.9
       1   80.41  242.93
Encroach Node=27288.9
       1      95  281.88
Encroach Node=27226.9
       1  137.88  289.93
Encroach Node=27170.9
       1  132.67     300
Encroach Node=26940.9
       1  237.96  412.92
Encroach Node=26562.9
       1  238.56  403.88
Encroach Node=26332.9
       1      52  177.44
Encroach Node=26272.9
       1   47.83     163
Encroach Node=26253.9
       1   53.26     164
Encroach Node=26195.9
       1    60.8  150.37
Encroach Node=25787.9
       1  207.23  371.28
Encroach Node=25566.9
       1     336     520
Encroach Node=25514.9
       1     234     447
Encroach Node=25466.9
       1     258     478
Encroach Node=25423.9
       1     285     490
Encroach Node=25207.9
       1     372   745.1
Encroach Node=24893.9
       1  175.21   602.1
Encroach Node=24493.9
       1  258.79  408.25
Encroach Node=24394.9
       1  161.46   269.5
Encroach Node=24377.9
       1  233.02  384.93
Encroach Node=24145.9
       1   93.91  245.28
Encroach Node=23838.9
       1  148.04  271.42
Encroach Node=23129.9
       1  218.42  477.44
Encroach Node=22682.9
       1  227.89  456.91
Encroach Node=21951.9
       1   460.7   701.7
Encroach Node=21859.9
       1     538     857
Encroach Node=21772.9
       1     616     957
Encroach Node=21221.9
       1  195.72  324.43
Encroach Node=20700.9
       1   23.22  320.97
Encroach Node=20644.9
       1   126.1  347.22
Encroach Node=20616.9
       1  207.27  385.83
Encroach Node=20574.9
       1  219.81  429.33
Encroach Node=20286.9
       1  226.88     630
Encroach Node=20211.9
       1  640.97  745.17
Encroach Node=20143.9
       1  722.73  811.99
Encroach Node=20092.9
       1  747.31  897.38
Encroach Node=19433.9
       1  262.19  530.34
Encroach Node=18834.9
       1  556.52  723.55
Encroach Node=18790.9
       1  641.15  751.17
Encroach Node=18722.9
       1  571.78  689.13
Encroach Node=18664.9
       1  610.39  674.12
Encroach Node=18445.9
       1  561.63  671.44
Encroach Node=18116.9
       1  545.14  643.96
Encroach Node=17774.9
       1  464.57   561.6
Encroach Node=17583.9
       1  747.81  848.26
Encroach Node=17102.9
       1 1044.75 1239.09
Encroach Node=17045.9
       1   50.33  265.05
Encroach Node=17009.9
       1   94.66  322.57
Encroach Node=16957.9
       1   98.39  323.44
Encroach Node=16096.9
       1  296.52  445.84
Encroach Node=15624.9
       1  478.39  589.38
Encroach Node=15269.9
       1  284.18   420.8
Encroach Node=14500.9
       1  164.78  309.43
Encroach Node=14447.9
       1  195.84  328.28
Encroach Node=14370.9
       1  208.73  319.71
Encroach Node=14320
       1  226.13  395.23
BEGIN DESCRIPTION:
detailed of cane creek
END DESCRIPTION:
Computation Interval=1HOUR
Output Interval=1HOUR
Run HTab= 0
Run UNet= 0
Run PostProcess= 0
UNET Theta= 1
UNET Theta Warmup= 1
UNET ZTol= 0.02
UNET ZSATol= 0.05
UNET MxIter= 20
UNET MaxInSteps= 0
UNET DtIC= 0
UNET DtMin= 0
UNET MaxCRTS= 20
UNET WFStab= 2
UNET SFStab= 1
UNET WFX= 1
UNET SFX= 1
UNET DSS MLevel= 4
UNET DZMax Abort= 100
UNET Convert EG Bridges=-1
UNET Use Existing IB Tables=-1
UNET Froude Reduction=False
UNET Froude Limit= 1
UNET Froude Power= 10
Instantaneous Interval=1HOUR
DSS File=dss
Write IC File= 0
Echo Input=False
Echo Output=False
Write Detailed= 0
Detailed Automatic Start=False, 10

--- dtl_cane_crk.f01 (steady flow) ---

Flow Title=detailed
Program Version=3.13
Number of Profiles= 5
Profile Names=100 YR,FWAY,10 YR,50 YR,500 YR
River Rch & RM=river,main            ,31262.9
    4890    4890    2350    4460    9210
River Rch & RM=river,main            ,31063.9
    5850    5850    2840    5340   10950
River Rch & RM=river,main            ,27342.9
    6040    6040    2940    5520   11300
River Rch & RM=river,main            ,21859.9
    6700    6700    3280    6140   12510
River Rch & RM=river,main            ,20700.9
    7160    7160    3520    6560   13330
River Rch & RM=river,main            ,19433.9
    7390    7390    3640    6780   13740
Boundary for River Rch & Prof#=river,main            , 1
Up Type= 0
Dn Type= 1
Dn Known WS=2416.432
Boundary for River Rch & Prof#=river,main            , 2
Up Type= 0
Dn Type= 1
Dn Known WS=2416.814
Boundary for River Rch & Prof#=river,main            , 3
Up Type= 0
Dn Type= 1
Dn Known WS=2413.444
Boundary for River Rch & Prof#=river,main            , 4
Up Type= 0
Dn Type= 1
Dn Known WS=2416.413
Boundary for River Rch & Prof#=river,main            , 5
Up Type= 0
Dn Type= 1
Dn Known WS=2421.279
DSS Import GetInterval= 0
DSS Import GetPeak= 0
DSS Import FillOption= 0

--- dtl_cane_crk.g01 (geometry) ---

Geom Title=detailed
Program Version=3.13

River Reach=river           ,main
Reach XY= 30
 1079533.6615897  839241.9011975 1079591.8282564  838767.6720306
 1078218.4845058  838297.2553637 1077457.1928388  838474.2970305
 1076570.7136717  839274.7866142 1075498.3386712  839116.7032808
 1074710.4949208  839728.7657811 1074074.4011705  839106.5886974
 1073535.6824203  837995.0157802  1070142.297002  838259.4845304
  1069304.755335  838040.4845303 1069169.5261682  837720.6303635
  1068623.307418  837686.4845301 1068169.3907511  838061.0782803
 1067657.8595009  837847.6199468 1067160.3282506  838069.1720303
 1066146.0574168  839105.2345308 1064356.7032493  838696.0261972
 1063643.9949157  838990.4845307  1063062.880332  839597.6511977
 1062669.4011652  839395.7032809 1062605.9219985  839014.4532807
 1061980.2657482  839013.5991141  1062205.682415  839496.4532809
 1061976.9115815  840508.5470314 1060498.4532475  839709.4011977
 1060362.6303308  839987.3699478 1061168.1199145  840964.8282816
 1060905.6199144  841234.6199484 1060257.8803307  841314.8282818

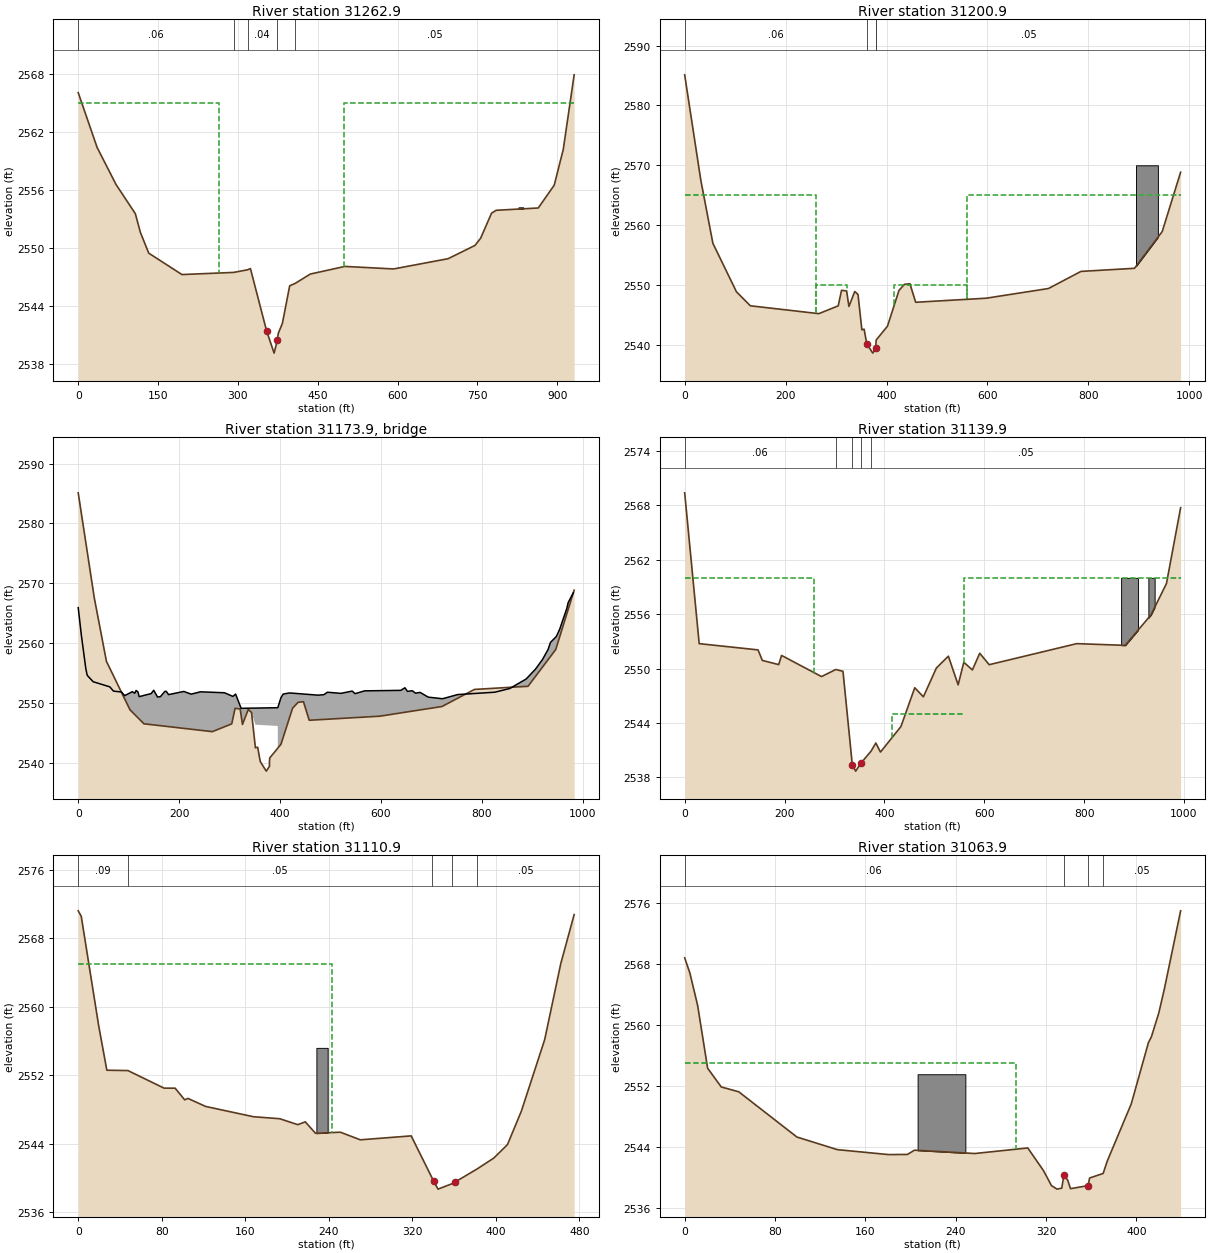
Type RM Length L Ch R = 1 ,31262.9 ,60.77,62.42,63.77
XS GIS Cut Line= 6
 1074800.1459877  839335.8543894 1074850.8959878  839683.4898064
 1074867.4897378  839724.5939731 1074881.2918211  839789.7918898
 1074993.0834879  840205.5835569 1075020.7501546  840232.1356403
#Sta/Elev= 30
       0 2566.08   35.49 2560.42   71.11 2556.58  107.35 2553.57  116.79 2551.64
  132.51 2549.49  194.84 2547.28  291.94  2547.5  318.14 2547.77  323.51  2547.9
  353.85 2541.47  368.01 2539.16  373.31 2540.31  373.88 2540.51  375.85  2541.2
  383.59 2542.24  397.31 2546.12  407.39 2546.36  435.97 2547.33  500.81 2548.12
  592.54 2547.86  694.96 2548.92  745.38 2550.29  755.96 2551.03  776.47 2553.62
   785.1 2553.92  864.28 2554.16  894.27 2556.52  911.23 2560.21  931.68 2567.92
#Mann= 5 ,-1 , 0
       0     .06       0  291.94     .09       0  318.14     .04       0
  373.31     .09       0  407.39     .05       0
#XS Ineff= 2 , 0
       0  264.83    2565  499.77       0    2565
Permanent Ineff=
       F       F
#Block Obstruct= 1 ,-1
  827.07  835.872554.231
Bank Sta=353.85,373.88
Exp/Cntr=0.5,0.3

Type RM Length L Ch R = 1 ,31200.9 ,59.98,61,63.07
BEGIN DESCRIPTION:
U/S 22161 SURVEYED SECTION
END DESCRIPTION:
XS GIS Cut Line= 6
 1074717.5678375  839353.5886975 1074799.2032542  839723.2032811
 1074818.9949209  839763.4011977 1074861.3907542  839878.7657811
 1074969.6511709  840232.9741146 1075027.3907543   840262.026198
#Sta/Elev= 30
       0 2585.12   31.88 2567.55    55.9 2556.96   102.6 2548.85  130.23 2546.51
 265.839  2545.2 304.265  2546.5  310.85  2549.1 320.874    2549 325.493  2546.4
 336.991  2548.9 343.478  2548.4 351.143  2542.5 355.566  2542.6 360.774  2540.2
 372.666  2538.6 378.956  2539.4 378.956  2540.1 379.545  2540.8 401.854  2543.1
 424.753  2549.1 435.661  2550.1 446.373  2550.2 457.774  2547.1  597.45 2547.78
  720.88  2549.4  785.31 2552.26   891.4 2552.78  946.36 2558.93  982.77 2568.84
#Mann= 4 ,-1 , 0
       0     .06       0 360.774     .05       0 378.956     .09       0
 379.545     .05       0
#XS Ineff= 4 ,-1
       0  259.81    2565     260  320.86    2550  415.46     559    2550
     560  982.77    2565
Permanent Ineff=
       F       F       F       F
#Block Obstruct= 1 ,-1
  894.35  937.73    2570
Bank Sta=360.774,378.956
Exp/Cntr=0.5,0.3

Type RM Length L Ch R = 3 ,31173.9 ,,,
BEGIN DESCRIPTION:
FBSTR1390
END DESCRIPTION:
Bridge Culvert--1,0,-1,-1, 0
Deck Dist Width WeirC Skew NumUp NumDn MinLoCord MaxHiCord MaxSubmerge Is_Ogee
22.5,31.5,2.6,0, 60, 60, , , 0.95, 0, 1,1,,
       0    6.16   15.12   17.89   29.64   62.51   69.97   85.62   92.13  107.21
  112.05  114.67  118.51  120.74  144.52  149.63  157.23  162.84  171.89  174.52
  179.06  209.25  223.92  242.37  289.84  306.56  311.85 322.863 395.463  401.72
  406.08   418.8  475.12  486.78  493.82  520.44  543.02  548.47   567.6  639.01
  647.51  652.46   661.9  668.49  677.53   693.6   721.9  752.12  825.41  855.12
  887.52  906.08  919.95  930.82  935.96  947.54  954.18  968.15  970.87  980.85
 2565.93 2561.37 2555.69 2554.61 2553.54 2552.69 2551.97 2551.83 2551.22 2551.88
 2551.62 2552.08 2551.83 2551.05 2551.56 2552.12 2550.99 2551.05 2551.95 2551.93
 2551.39 2551.92 2551.47 2551.86  2551.7 2551.09 2551.48  2549.1  2549.2 2550.87
 2551.48 2551.67  2551.3 2551.38 2551.79  2551.6 2551.98 2551.55 2552.02  2552.1
 2552.53 2551.93 2552.04 2551.63 2551.76 2550.97  2550.7  2551.4 2551.79 2552.41
 2553.99 2555.64 2557.25 2558.89 2560.13 2561.11 2562.34 2565.78 2566.76 2568.38
                                                                                
                                                                                
                                                          2546.5 2546.15
                                                                                
                                                                                
                                                                                
       0    6.16   15.12   17.89   29.64   62.51   69.97   85.62   92.13  107.21
  112.05  114.67  118.51  120.74  144.52  149.63  157.23  162.84  171.89  174.52
  179.06  209.25  223.92  242.37  289.84  306.56  311.85 322.863 395.463  401.72
  406.08   418.8  475.12  486.78  493.82  520.44  543.02  548.47   567.6  639.01
  647.51  652.46   661.9  668.49  677.53   693.6   721.9  752.12  825.41  855.12
  883.37  906.08  919.95  930.82  935.96  947.54  954.18  968.15  970.87  992.81
 2565.93 2561.37 2555.69 2554.61 2553.54 2552.69 2551.97 2551.83 2551.22 2551.88
 2551.62 2552.08 2551.83 2551.05 2551.56 2552.12 2550.99 2551.05 2551.95 2551.93
 2551.39 2551.92 2551.47 2551.86  2551.7 2551.09 2551.48  2549.1  2549.2 2550.87
 2551.48 2551.67  2551.3 2551.38 2551.79  2551.6 2551.98 2551.55 2552.02  2552.1
 2552.53 2551.93 2552.04 2551.63 2551.76 2550.97  2550.7  2551.4 2551.79 2552.41
 2553.72 2555.64 2557.25 2558.89 2560.13 2561.11 2562.34 2565.78 2566.76  2567.6
                                                                                
                                                                                
                                                          2546.5 2546.15
                                                                                
                                                                                
                                                                                
BR Coef=-1 , 0 , 0 ,, 0 ,,,0.8,0,,0,
WSPro=,,,, 1 ,,,, 0 ,,,, 0 ,,,,-1 ,-1 ,-1 , 0 , 0 , 0 , 0 , 0
BC Design=,, 0 ,, 0 ,,,,,,

Type RM Length L Ch R = 1 ,31139.9 ,27.23,29,31.36
BEGIN DESCRIPTION:
D/S 22161 SURVEYED SECTION
END DESCRIPTION:
XS GIS Cut Line= 6
 1074661.1407541  839388.9949476 1074737.4949208   839714.797031
 1074738.7970042  839776.4011977 1074800.0157542  839885.9845311
 1074927.5574209   840254.744948 1074996.4115876   840297.432448
#Sta/Elev= 30
       0 2569.37   29.06 2552.75  146.96 2552.06  155.51  2550.9  188.34 2550.44
  194.06 2551.45   274.1 2549.12 302.653  2549.9 317.055  2549.7 335.729  2539.4
 342.483  2538.7  353.31  2539.6 373.275  2540.9  382.81  2541.8 392.147  2540.8
  433.11 2543.61  460.79 2547.89   478.1 2546.89  504.18 2550.07  528.13 2551.37
   547.7 2548.21  559.03  2550.7  576.22 2549.85  590.95 2551.69  609.87 2550.43
  785.23 2552.75  882.37 2552.56  933.81 2555.91  964.91 2559.37  993.28 2567.73
#Mann= 5 ,-1 , 0
       0     .06       0 302.653     .09       0 335.729     .04       0
  353.31     .09       0 373.275     .05       0
#XS Ineff= 4 ,-1
       0  259.81    2560     260  320.86    2545  415.46     559    2545
     560  993.28    2560
Permanent Ineff=
       F       F       F       F
#Block Obstruct= 2 ,-1
  874.12  907.82    2560  928.68  941.25    2560
Bank Sta=335.729,353.31
Exp/Cntr=0.5,0.3

Type RM Length L Ch R = 1 ,31110.9 ,40.92,47,50.71
XS GIS Cut Line= 6
 1074647.8543209  839384.5627228 1074697.6980709   839624.093973
  1074705.791821  839700.4898064 1074710.4897376  839713.8960564
 1074700.0939043  839763.3960565 1074653.3230709  839836.7502232
#Sta/Elev= 30
       0  2571.2    2.92 2570.56   19.57 2557.81   27.43 2552.58   47.61 2552.54
    82.2 2550.49   92.86 2550.48  101.99 2549.12   105.1 2549.29  122.02 2548.35
  167.75 2547.15  193.22 2546.91  210.32 2546.22  217.52 2546.55  227.35 2545.21
  251.13 2545.34  270.27 2544.45  318.99 2544.91  338.54 2540.11  340.51 2539.62
  344.71 2538.69   358.5 2539.34  360.65 2539.49  381.94 2541.03  398.15 2542.32
  411.22 2543.89  424.58 2547.81  446.89 2556.16  462.31 2565.04  475.11 2570.76
#Mann= 5 ,-1 , 0
       0     .09       0   47.61     .05       0  338.54     .04       0
   358.5     .09       0  381.94     .05       0
#XS Ineff= 2 , 0
       0  243.55    2565               0
Permanent Ineff=
       F       F
#Block Obstruct= 1 ,-1
  228.18  238.982555.193
Bank Sta=340.51,360.65
Exp/Cntr=0.3,0.1

Type RM Length L Ch R = 1 ,31063.9 ,351.1,357.59,364.44
XS GIS Cut Line= 5
 1074632.3699208  839386.7761976 1074652.6095041   839507.359531
 1074669.9949208  839693.2761977 1074659.6615875  839732.1928644
 1074616.4220041  839810.9011978
#Sta/Elev= 30
       0 2568.84     4.6 2566.85    11.5 2562.57   20.33 2554.33    32.4 2551.87
   47.92 2551.23   99.34 2545.29  135.18 2543.63  180.48 2542.98  197.24    2543
  203.49 2543.56  256.85 2543.12  303.77 2543.85  317.68 2540.87  324.74  2538.9
  329.65 2538.44  333.83 2538.57 335.772  2540.3 339.154  2539.6 341.589  2538.5
 357.147  2538.9   358.5  2539.9 370.495  2540.5 374.057  2542.1  395.36 2549.64
   410.6 2557.71  413.13 2558.43  419.73 2561.58  424.77 2564.81  439.07 2575.02
#Mann= 4 ,-1 , 0
       0     .06       0 335.772     .04       0 357.147     .09       0
 370.495     .05       0
#XS Ineff= 2 , 0
       0  293.33    2555               0
Permanent Ineff=
       F       F
#Block Obstruct= 1 ,-1
  206.22   248.52553.541
Bank Sta=335.772,357.147
Exp/Cntr=0.3,0.1

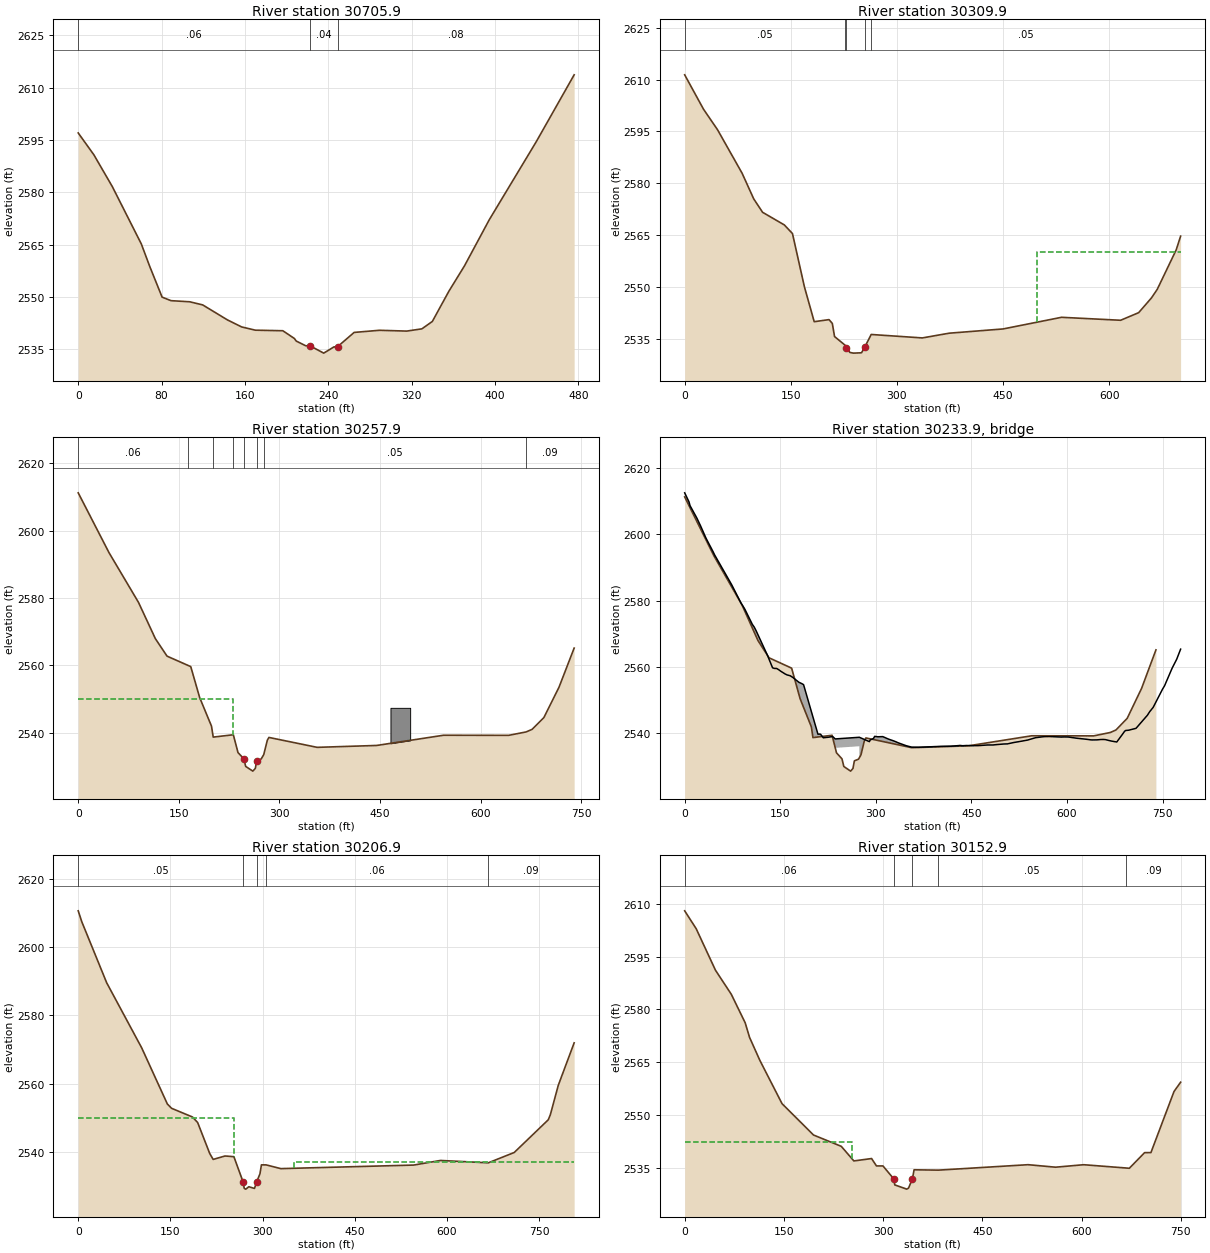
Type RM Length L Ch R = 1 ,30705.9 ,393.73,396,397.12
XS GIS Cut Line= 5
 1074560.7032541  839296.9324475 1074504.1303374  839355.2657809
  1074430.765754  839446.3178643 1074382.1511707  839502.0053643
 1074273.4220039  839674.3699477
#Sta/Elev= 30
       0 2596.99   15.07 2590.71   32.74 2581.62   60.55 2565.21   68.63 2558.77
   80.51 2549.97   89.09 2548.96  107.03 2548.64  119.44 2547.75  143.22 2543.45
  156.83 2541.44  169.98 2540.51  196.37 2540.35  207.41 2538.14  209.26 2537.39
  218.26 2536.05  222.47 2536.03  235.61 2533.94  245.29  2535.7  249.08 2535.83
  264.78 2539.87   289.1 2540.48  315.24 2540.25  329.77 2540.89  339.82 2543.01
  355.64 2551.63  370.77 2558.98  394.45 2572.13  439.59  2594.5  475.91 2613.63
#Mann= 3 , 0 , 0
       0     .06       0  222.47     .04       0  249.08     .08       0
Bank Sta=222.47,249.08
Exp/Cntr=0.3,0.1

Type RM Length L Ch R = 1 ,30309.9 ,51.56,51.32,52.22
XS GIS Cut Line= 6
  1074346.890754  839075.8491141 1074217.4324206  839124.5366141
 1074179.7032539  839148.5991141 1074110.4011705  839203.4949475
 1073892.7136704  839385.7761976 1073812.6511704  839505.8699476
#Sta/Elev= 30
       0 2611.36   26.59 2601.42   46.46 2595.46   81.22 2582.85   97.56 2575.46
   110.1 2571.57  140.82 2567.91  152.34 2565.41  169.22 2549.99 183.074  2539.9
 204.031  2540.5 208.657  2539.4 211.811  2535.6  226.67  2533.1 228.282  2532.3
 233.539    2531 238.515  2530.8 249.939  2530.9 254.916  2532.7 263.607  2536.2
  335.91  2535.2  373.78 2536.57  450.03  2537.8   532.6 2541.17  616.11 2540.31
  641.59 2542.51  659.72 2546.79  667.94 2549.29  694.65 2560.69   700.9 2564.65
#Mann= 5 ,-1 , 0
       0     .05       0  226.67     .09       0 228.282     .04       0
 254.916     .09       0 263.607     .05       0
#XS Ineff= 2 , 0
       0                  497.49       0    2560
Permanent Ineff=
       F       F
Bank Sta=228.282,254.916
Exp/Cntr=0.5,0.3

Type RM Length L Ch R = 1 ,30257.9 ,45.02,51,54.19
BEGIN DESCRIPTION:
U/S XS 21221 SURVEYED SECTION
END DESCRIPTION:
XS GIS Cut Line= 6
 1074340.2553373  839054.8282807 1074189.7761706  839092.4532808
 1074147.2032539  839110.4011974 1074034.2970038  839202.7032808
 1073889.8699204  839306.7345309 1073776.6199204  839487.9220309
#Sta/Elev= 30
       0 2611.22   45.93 2593.46   89.87 2578.71  115.05 2567.93  132.45 2562.74
  163.35 2560.02  167.84 2559.62   181.1 2550.44  198.76 2541.95 201.298  2538.7
 231.323  2539.4 238.275  2534.1 246.853  2532.3 249.737    2530 260.386  2528.6
 264.084  2529.4 266.303  2531.7  272.81  2532.2 276.656  2533.5 282.054  2537.8
 284.421  2538.6  356.33 2535.66  445.14 2536.22  544.71 2539.25  641.84 2539.22
  667.93 2540.24  676.81    2541   694.4  2544.5  716.99 2553.53  739.53 2565.13
#Mann= 8 ,-1 , 0
       0     .06       0  163.35     .09       0 201.298     .05       0
 231.323     .09       0 246.853     .04       0 266.303     .09       0
 276.656     .05       0  667.93     .09       0
#XS Ineff= 2 , 0
       0  231.32    2550  284.42       0    2538
Permanent Ineff=
       F       F
#Block Obstruct= 1 ,-1
  465.63  494.992547.392
Bank Sta=246.853,266.303
Exp/Cntr=0.5,0.3

Type RM Length L Ch R = 3 ,30233.9 ,,,
BEGIN DESCRIPTION:
FBSTR 1905
END DESCRIPTION:
Bridge Culvert--1,0,-1,-1, 0
Deck Dist Width WeirC Skew NumUp NumDn MinLoCord MaxHiCord MaxSubmerge Is_Ogee
14.2,32,2.6,0, 153, 151, , , 0.95, 0, 1,1,,
       0    6.81    8.37   19.13   22.58   24.97    33.6   44.56   47.08    60.8
   61.59   70.58   72.05   73.78   81.58   88.41   91.97    94.6  101.86   106.1
  109.16  112.17  118.38  123.16  129.62  129.75  137.88  140.73  144.34  147.73
  150.57     156  157.73  159.16   160.8  165.55  169.86  177.45  179.16  184.13
  186.57  195.47  198.31  209.14  211.99  213.31  217.53   225.3  225.53  225.97
  232.14   236.2   236.2   274.1   274.1  289.89  290.98  296.23  298.19  303.02
  309.28  310.84  320.12  323.34  327.96  331.26  335.49  345.16  346.49  347.58
  356.16  365.22  365.87  366.67  376.71   381.7  388.03  395.53  399.61  403.03
  410.42  416.75  421.28     426  432.26  436.18  442.25  448.43     450  450.95
  452.58  462.12  473.63  474.04  475.38  483.93   485.7  487.38  488.61  500.61
  506.56  511.66  515.82  523.57  525.07  525.91     538  548.25  550.81  559.67
  563.01  566.34  573.43  580.64  583.09  586.36  591.06  594.64  601.79  613.56
  614.71  615.39  627.35  629.61  637.39   639.9  644.32  646.97  652.69  656.18
  659.87  669.51  678.07  685.55  686.21  687.06  690.25  691.84  696.73  705.56
  708.12  709.45   726.1  729.83  735.15  741.84  750.02     753  761.94  763.63
  764.98  772.13  778.25
 2612.45 2609.71  2608.6 2604.84 2603.43 2602.48 2598.73 2594.71 2593.71 2589.14
 2588.93 2585.86 2585.34 2584.75 2581.78 2579.23 2578.17 2577.32 2574.49 2572.84
    2572 2570.87 2568.27 2566.26  2563.6 2563.56 2559.74 2559.55 2559.53 2559.13
 2558.72 2558.05 2557.86 2557.72 2557.58 2557.34 2556.81 2555.65 2555.38 2554.93
 2554.65 2548.83 2546.88 2539.73 2539.76 2539.69 2538.64  2538.8 2538.81 2538.83
 2539.03  2538.3  2538.3  2538.8  2538.8 2537.48 2537.98 2538.44 2539.08 2538.95
 2538.99    2539 2538.23 2538.02 2537.71 2537.46  2537.1 2536.41 2536.33 2536.26
 2535.83 2535.79 2535.79 2535.79 2535.87 2535.94 2535.98 2536.04 2536.08 2536.07
 2536.07  2536.1 2536.16 2536.23 2536.34 2536.25 2536.32 2536.28 2536.25 2536.24
 2536.26  2536.3 2536.47 2536.48 2536.48 2536.48 2536.52 2536.55 2536.58 2536.77
 2536.81 2537.03  2537.2 2537.44 2537.49 2537.53 2537.95 2538.53 2538.68  2538.9
 2538.97 2539.01 2539.02 2538.96 2538.91  2538.9 2538.86  2538.9 2538.88 2538.55
 2538.52 2538.51 2538.29 2538.22 2538.02    2538 2538.02 2538.02 2538.12 2538.14
 2538.11 2537.66 2537.38 2539.31 2539.48 2539.72 2540.58 2540.84 2540.93 2541.37
 2541.49 2541.76 2545.43 2546.54  2547.8 2550.33 2553.35 2554.29 2558.29 2559.08
 2559.64 2562.32 2565.35
                                                                                
                                                                                
                                                                                
                                                                                
                                                                                
          2535.6  2535.6  2536.1  2536.1
                                                                                
                                                                                
                                                                                
                                                                                
                                                                                
                                                                                
                                                                                
                                                                                
                                                                                
                        
       0    6.81    8.37   19.13   22.58   24.97    33.6   44.56   47.08    60.8
   61.59   70.58   72.05   73.78   81.58   88.41   91.97    94.6  101.86   106.1
  109.16  112.17  118.38  123.16  129.62  129.75  137.88  140.73  144.34  147.73
  150.57     156  157.73  159.16   160.8  165.55  169.86  177.45  179.16  184.13
  186.57  195.47  198.31  209.14  211.99  213.31  217.53   225.3  225.53  225.97
  232.14  259.29  259.29  297.19  297.19  298.19  303.02  309.28  310.84  320.12
  323.34  327.96  331.26  335.49  345.16  346.49  347.58  356.16  365.22  365.87
  366.67  376.71   381.7  388.03  395.53  399.61  403.03  410.42  416.75  421.28
     426  432.26  436.18  442.25  448.43     450  450.95  452.58  462.12  473.63
  474.04  475.38  483.93   485.7  487.38  488.61  500.61  506.56  511.66  515.82
  523.57  525.07  525.91     538  548.25  550.81  559.67  563.01  566.34  573.43
  580.64  583.09  586.36  591.06  594.64  601.79  613.56  614.71  615.39  627.35
  629.61  637.39   639.9  644.32  646.97  652.69  656.18  659.87  669.51  678.07
  685.55  686.21  687.06  690.25  691.84  696.73  705.56  708.12  709.45   726.1
  729.83  735.15  741.84  750.02     753  761.94  763.63  764.98  772.13  778.25
  806.76
 2612.45 2609.71  2608.6 2604.84 2603.43 2602.48 2598.73 2594.71 2593.71 2589.14
 2588.93 2585.86 2585.34 2584.75 2581.78 2579.23 2578.17 2577.32 2574.49 2572.84
    2572 2570.87 2568.27 2566.26  2563.6 2563.56 2559.74 2559.55 2559.53 2559.13
 2558.72 2558.05 2557.86 2557.72 2557.58 2557.34 2556.81 2555.65 2555.38 2554.93
 2554.65 2548.83 2546.88 2539.73 2539.76 2539.69 2538.64  2538.8 2538.81 2538.83
 2539.03  2538.3  2538.3  2538.8  2538.8 2539.08 2538.95 2538.99    2539 2538.23
 2538.02 2537.71 2537.46  2537.1 2536.41 2536.33 2536.26 2535.83 2535.79 2535.79
 2535.79 2535.87 2535.94 2535.98 2536.04 2536.08 2536.07 2536.07  2536.1 2536.16
 2536.23 2536.34 2536.25 2536.32 2536.28 2536.25 2536.24 2536.26  2536.3 2536.47
 2536.48 2536.48 2536.48 2536.52 2536.55 2536.58 2536.77 2536.81 2537.03  2537.2
 2537.44 2537.49 2537.53 2537.95 2538.53 2538.68  2538.9 2538.97 2539.01 2539.02
 2538.96 2538.91  2538.9 2538.86  2538.9 2538.88 2538.55 2538.52 2538.51 2538.29
 2538.22 2538.02    2538 2538.02 2538.02 2538.12 2538.14 2538.11 2537.66 2537.38
 2539.31 2539.48 2539.72 2540.58 2540.84 2540.93 2541.37 2541.49 2541.76 2545.43
 2546.54  2547.8 2550.33 2553.35 2554.29 2558.29 2559.08 2559.64 2562.32 2565.35
 2571.91
                                                                                
                                                                                
                                                                                
                                                                                
                                                                                
          2535.6  2535.6  2536.1  2536.1
                                                                                
                                                                                
                                                                                
                                                                                
                                                                                
                                                                                
                                                                                
                                                                                
                                                                                
        
BR Coef=-1 , 0 , 0 ,, 0 ,,,0.8,-1,,0,
WSPro=,,,, 1 ,,,, 0 ,,,, 0 ,,,,-1 ,-1 ,-1 , 0 , 0 , 0 , 0 , 0
BC Design=,, 0 ,, 0 ,,,,,,

Type RM Length L Ch R = 1 ,30206.9 ,51.87,54,55.33
BEGIN DESCRIPTION:
D/S OF 21221
END DESCRIPTION:
XS GIS Cut Line= 6
  1074338.047004  839020.5261974 1074193.0886706  839045.9741141
 1074156.6095039  839062.2970307 1074030.0990872  839126.7032808
 1073734.8386704  839329.9116142 1073656.6095036  839419.1199476
#Sta/Elev= 30
       0 2610.56    5.88 2607.34   46.32  2589.5   103.3 2570.44  145.01 2554.02
  151.84 2552.76  185.89 2550.21  194.28  2548.6  213.97 2539.52 219.518  2537.8
   238.8  2538.8  253.24  2538.6 268.246  2531.2 270.102  2529.3 272.683  2529.1
 277.524  2529.8 286.721  2529.3 290.271  2531.2 295.676  2533.6 298.015  2536.2
 305.599  2536.2  329.64  2535.1  545.73 2536.14  589.21 2537.49   667.1  2536.8
  709.26 2539.82  764.63 2549.39  768.02 2550.87  780.93 2559.48  806.76 2571.91
#Mann= 5 ,-1 , 0
       0     .05       0 268.246     .04       0 290.271     .08       0
 305.599     .06       0   667.1     .09       0
#XS Ineff= 2 , 0
       0  253.24    2550  351.25       0  2537.1
Permanent Ineff=
       F       F
Bank Sta=268.246,290.271
Exp/Cntr=0.5,0.3

Type RM Length L Ch R = 1 ,30152.9 ,227.89,229,231.09
XS GIS Cut Line= 6
  1074365.703254  838981.7970307 1074146.6199205  839011.6720307
 1074034.4949205  839060.5991141 1073962.7032538  839104.5991141
  1073733.567837  839199.4220308 1073662.8699203  839217.7449475
#Sta/Elev= 30
       0 2608.06   17.44 2602.96   46.54 2591.17   70.44 2584.33   91.46 2576.21
   98.11 2572.04  113.81 2565.46  147.16 2553.21  194.76 2544.29  236.71 2541.07
  255.75 2536.92 282.531  2537.6 289.877  2535.5 299.697  2535.5 315.664  2531.9
 317.613  2530.1 335.679  2528.9 338.378  2529.2 344.225  2531.8 346.773  2534.4
 383.505  2534.3  519.07 2535.85  560.52 2535.14  603.13 2535.84  667.14 2534.91
  672.06 2534.83  695.19 2539.28  704.74 2539.29  739.65 2556.67  749.62 2559.31
#Mann= 5 ,-1 , 0
       0     .06       0 315.664     .04       0 344.225     .09       0
 383.505     .05       0  667.14     .09       0
#XS Ineff= 2 , 0
       0  252.67 2542.17               0
Permanent Ineff=
       F       F
Bank Sta=315.664,344.225
Exp/Cntr=0.3,0.1

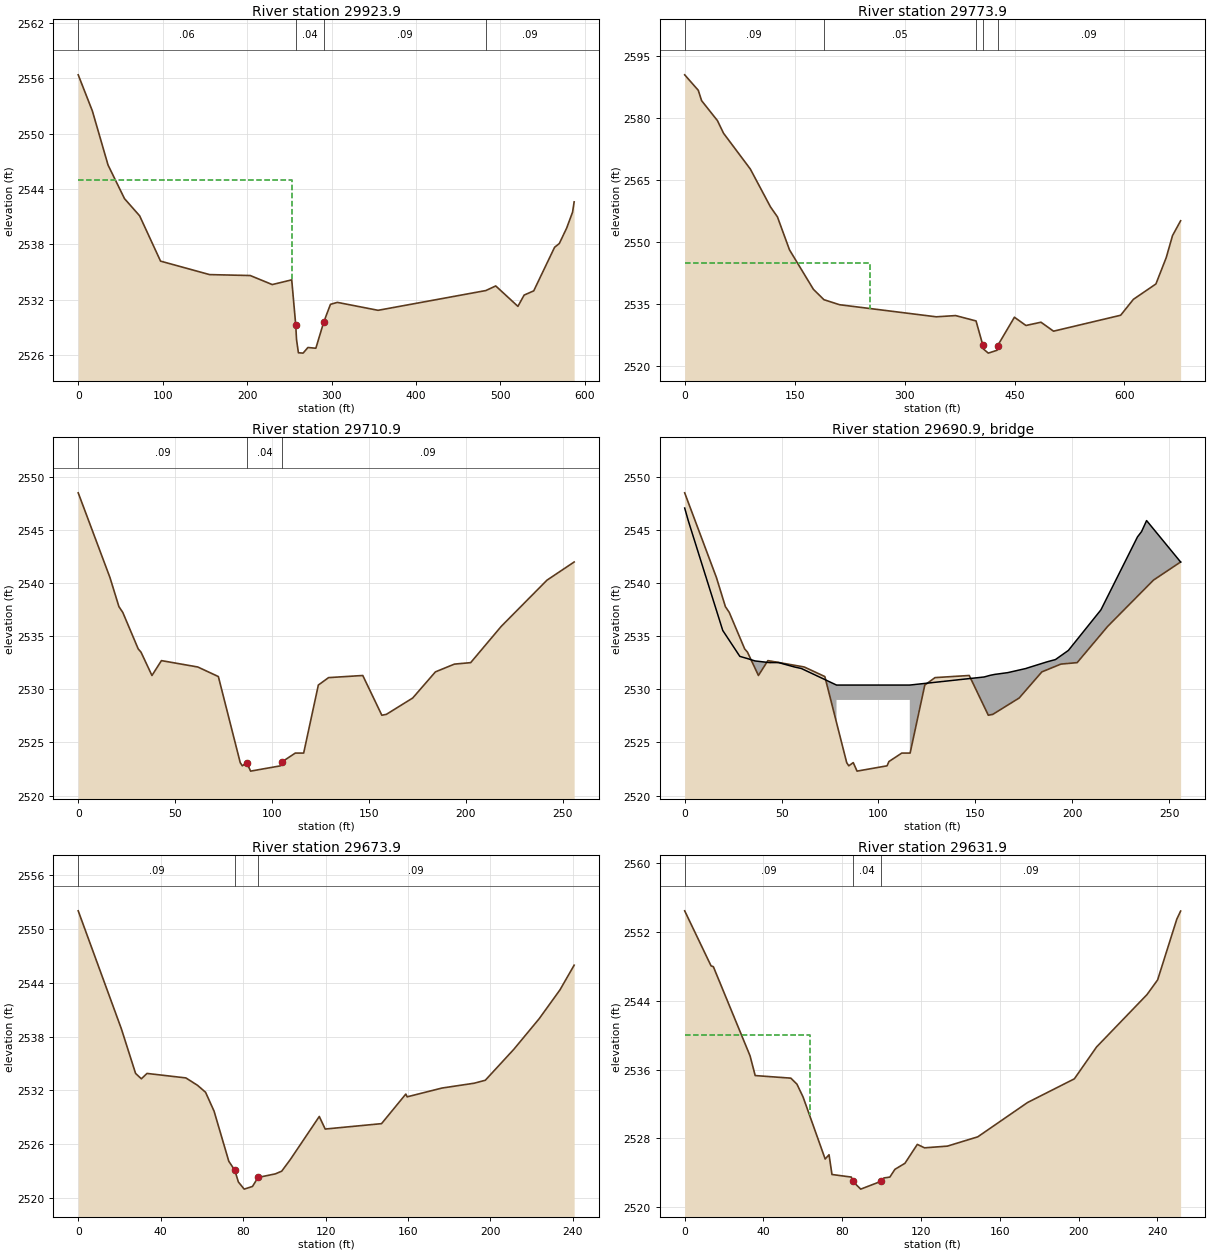
Type RM Length L Ch R = 1 ,29923.9 ,158.48,150,147.71
XS GIS Cut Line= 4
 1074271.1928373  838771.7553639 1074169.9532539  838788.3386973
 1073988.4220038  838838.0886973 1073700.4011703   838908.786614
#Sta/Elev= 30
       0 2556.37   16.79 2552.45   35.35 2546.59   54.84 2542.95   72.76 2541.09
   97.52 2536.18   155.6 2534.72  203.71 2534.62  229.83 2533.64  252.88 2534.15
  257.67 2529.23  258.54  2527.7   260.8 2526.25  266.37 2526.21  272.04 2526.82
  281.46 2526.74  290.82 2529.58  298.77  2531.5  306.95 2531.71  355.18 2530.85
  482.71 2532.99  494.52 2533.49  520.78 2531.28  528.15  2532.5  539.52 2532.96
  564.22 2537.68  569.82 2538.09  578.51 2539.76  585.52 2541.49  587.39  2542.6
#Mann= 4 ,-1 , 0
       0     .06       0  257.67     .04       0  290.82     .09       0
  482.71     .09       0
#XS Ineff= 2 , 0
       0  252.67    2545               0
Permanent Ineff=
       F       F
Bank Sta=257.67,290.82
Exp/Cntr=0.3,0.1

Type RM Length L Ch R = 1 ,29773.9 ,61.6,63,62.36
XS GIS Cut Line= 6
 1074228.8490872  838414.3491138 1074213.9115872  838510.9011972
 1074150.9324205  838578.3699472 1073910.7032538  838721.9949473
  1073791.442837  838769.9428639  1073716.192837  838767.1407806
#Sta/Elev= 30
       0 2590.55   18.56  2586.8   23.08 2584.29   44.71 2579.45   52.99  2576.4
   89.56 2567.72  117.08 2558.54   126.6 2556.11  142.99 2548.14  175.62 2538.57
     190 2536.05  211.36 2534.83  343.27  2531.9 369.651  2532.2 397.528  2530.9
 406.866    2525  407.61  2524.1 414.241  2523.1 426.286  2523.8 426.962  2524.9
 449.901  2531.8 465.599  2529.8  486.11 2530.59  503.27 2528.42  594.82 2532.28
  612.23 2536.14  642.93 2539.86  656.98 2546.23  665.59 2551.58  676.65 2555.18
#Mann= 5 ,-1 , 0
       0     .09       0     190     .05       0 397.528     .09       0
 406.866     .04       0 426.962     .09       0
#XS Ineff= 2 , 0
       0  252.67 2544.93               0
Permanent Ineff=
       F       F
Bank Sta=406.866,426.962
Exp/Cntr=0.5,0.3

Type RM Length L Ch R = 1 ,29710.9 ,36.4,37,34.75
BEGIN DESCRIPTION:
u/s of fbstr 20678
END DESCRIPTION:
XS GIS Cut Line= 6
 1073991.3490871  838578.5053639 1073971.2970038  838602.0991139
 1073930.2970038  838634.5991139 1073905.4949204  838648.0991139
 1073878.9011704  838670.2970306 1073784.3595037  838724.7032806
#Sta/Elev= 30
       0 2548.49   16.38 2540.52   21.01 2537.78   23.02 2537.23  30.966  2533.8
  32.399  2533.5  38.055  2531.3  42.943  2532.7  61.701  2532.1  72.322  2531.2
  83.608  2523.1  84.683  2522.8  86.986  2523.1  88.957  2522.3  104.44  2522.8
 105.386  2523.2  112.04    2524  116.34    2524 123.915  2530.4 129.187  2531.1
 146.845  2531.3  156.68 2527.56     159 2527.64  172.61 2529.18  184.33 2531.64
  194.12 2532.37  202.53 2532.51  218.28 2535.92  241.89 2540.27  255.92 2541.98
#Mann= 3 ,-1 , 0
       0     .09       0  86.986     .04       0 105.386     .09       0
#XS Ineff= 2 , 0
       0   68.35    2530  126.15       0    2530
Permanent Ineff=
       F       F
Bank Sta=86.986,105.386
Exp/Cntr=0.5,0.3

Type RM Length L Ch R = 3 ,29690.9 ,,,
BEGIN DESCRIPTION:
FBSTR 6694
END DESCRIPTION:
Bridge Culvert--1,0,-1,-1, 0
Deck Dist Width WeirC Skew NumUp NumDn MinLoCord MaxHiCord MaxSubmerge Is_Ogee
12,20,2.6,0, 32, 32, , , 0.95, 0, 1,1,,
       0    1.85   19.64   28.46   31.65   32.63    36.3   43.86    48.4   51.88
   56.71   60.19  78.354  78.354 116.154 116.154  154.53  157.29  157.73  159.87
  166.73  175.88  176.16  176.54  187.08  191.34     198   214.8  233.65  235.75
  238.36  255.92
 2547.06 2545.87 2535.54  2533.1 2532.93 2532.88 2532.67 2532.51 2532.52 2532.34
  2532.1 2531.96  2530.4  2530.4  2530.4  2530.4 2531.16  2531.3 2531.32  2531.4
 2531.57 2531.95 2531.96 2531.99 2532.59  2532.8 2533.66 2537.48 2544.34 2544.84
 2545.88 2541.98
                                                                                
                            2529    2529
                                                                                
                
       0    1.85   19.64   28.46   31.65   32.63    36.3   43.86    48.4   51.88
   56.71   60.19   70.53   70.53  108.33  108.33  154.53  157.29  157.73  159.87
  166.73  175.88  176.16  176.54  187.08  191.34     198   214.8  233.65  235.75
  238.36  240.61
 2547.06 2545.87 2535.54  2533.1 2532.93 2532.88 2532.67 2532.51 2532.52 2532.34
  2532.1 2531.96  2529.1  2529.1  2529.1  2529.1 2531.16  2531.3 2531.32  2531.4
 2531.57 2531.95 2531.96 2531.99 2532.59  2532.8 2533.66 2537.48 2544.34 2544.84
 2545.88 2545.97
                                                                                
                          2527.7  2527.7
                                                                                
                
BR Coef=-1 , 0 , 0 ,, 0 ,,,0.8,0,,0,
WSPro=,,,, 1 ,,,, 0 ,,,, 0 ,,,,-1 ,-1 ,-1 , 0 , 0 , 0 , 0 , 0
BC Design=,, 0 ,, 0 ,,,,,,

Type RM Length L Ch R = 1 ,29673.9 ,46.64,42,41.29
BEGIN DESCRIPTION:
d/s of 20678
END DESCRIPTION:
XS GIS Cut Line= 6
 1073965.9324205  838558.4636972 1073938.7970038  838577.9011972
 1073921.8074204  838595.2032805 1073885.2032538  838620.0991139
 1073871.9949204  838624.9011972 1073764.6824204  838686.3178639
#Sta/Elev= 30
       0 2552.03   20.96 2538.86  27.839  2533.9   30.63  2533.3  33.373  2533.9
  52.237  2533.4  57.916 2532.57  61.789  2531.8  65.904  2529.7  73.074  2524.1
  75.986  2523.1  77.694  2521.8  80.533    2521  84.551  2521.3  87.246  2522.3
   95.62  2522.7  98.724    2523  102.91  2524.3 116.962  2529.1 119.825  2527.7
 147.159  2528.3 158.949  2531.6   159.6 2531.29  176.48 2532.27  192.13 2532.81
  197.52 2533.14  211.38  2536.6  223.64    2540  233.71 2543.21  240.61 2545.97
#Mann= 3 ,-1 , 0
       0     .09       0  75.986     .04       0  87.246     .09       0
#XS Ineff= 2 , 0
       0   60.53  2527.8  118.33       0  2527.8
Permanent Ineff=
       F       F
Bank Sta=75.986,87.246
Exp/Cntr=0.5,0.3

Type RM Length L Ch R = 1 ,29631.9 ,202.8,209,213.35
XS GIS Cut Line= 6
 1073936.8595038  838521.2032805 1073910.5990871  838541.4949472
 1073895.7970038  838555.9011972 1073880.0990871  838566.9949472
 1073864.9949204  838584.4011972 1073737.0157537  838672.2136972
#Sta/Elev= 30
       0 2554.45    13.4 2548.05   14.56 2547.96  33.192  2537.6  35.811  2535.3
  53.919    2535  57.016  2534.3  60.139  2532.8  71.346  2525.6   73.31  2526.1
  74.796  2523.8  84.643  2523.5  85.373    2523  89.403  2522.1  99.627    2523
 101.189  2523.4 104.186  2523.5 106.754  2524.4 111.842  2525.1 118.137  2527.3
 121.814  2526.9 133.449  2527.1  148.84 2528.18  174.13 2532.17  197.88 2534.92
  209.18 2538.63  234.76 2544.71  240.16 2546.42   249.9 2553.48  251.84 2554.42
#Mann= 3 ,-1 , 0
       0     .09       0  85.373     .04       0  99.627     .09       0
#XS Ineff= 2 , 0
       0   63.44    2540               0
Permanent Ineff=
       F       F
Bank Sta=85.373,99.627
Exp/Cntr=0.3,0.1