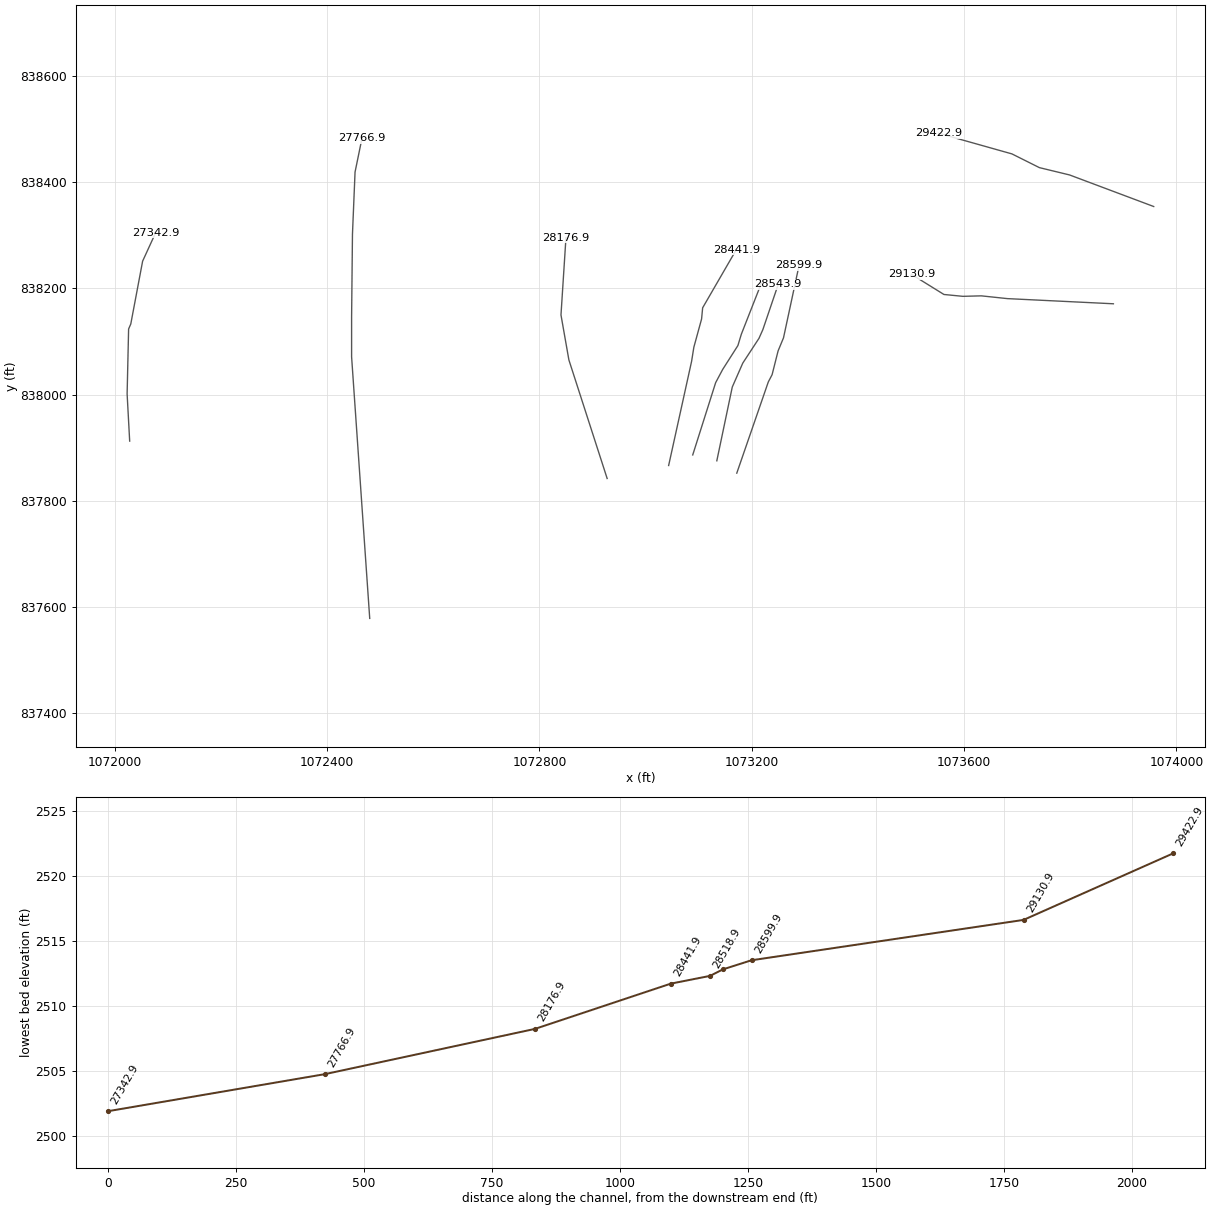
HEC-RAS study dtl_cane_crk.prj: cane creek

--- dtl_cane_crk.g01 (geometry) --- (continued)

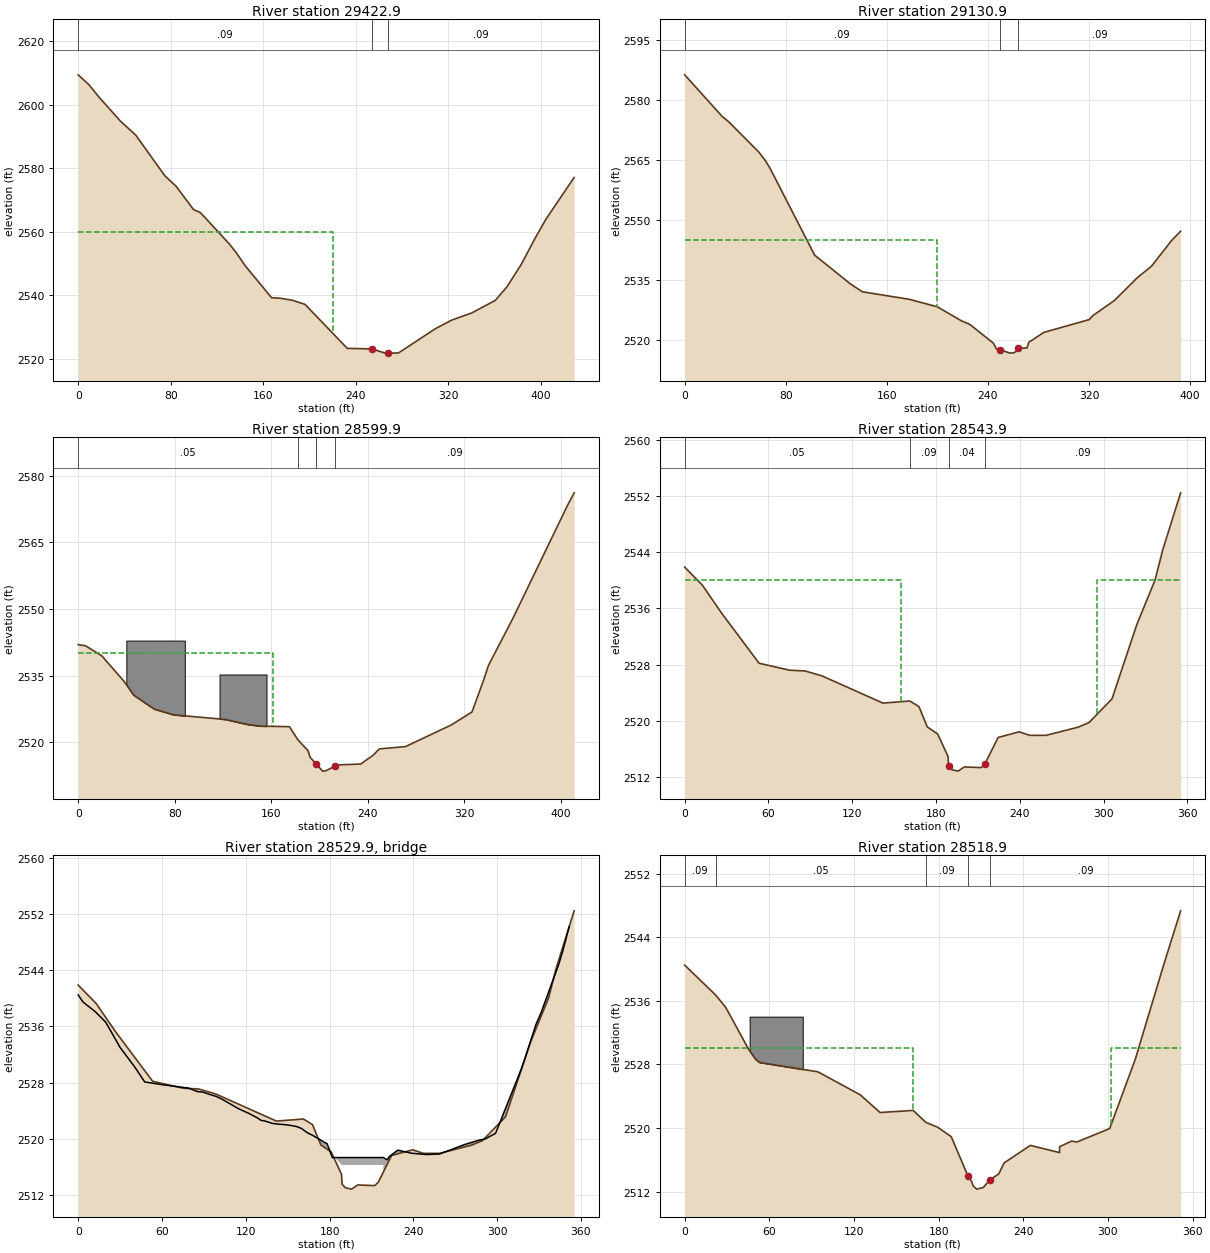
Type RM Length L Ch R = 1 ,29422.9 ,286.5,292,298.18
XS GIS Cut Line= 5
 1073957.1303371  838354.1199471 1073798.6407537  838413.5574471
  1073741.786587  838427.3386971 1073690.1095037  838453.1824471
 1073552.2865869  838491.9428638
#Sta/Elev= 30
       0 2609.44    9.37 2606.29   18.17 2602.33   36.51 2594.84   49.76 2590.43
   74.99 2577.59   84.74 2574.26   99.73 2566.95  105.61 2566.02  130.91 2556.02
  137.07 2553.14  144.37 2549.25  167.17 2539.17  174.41 2539.03  185.46 2538.34
  196.03 2537.09  232.57 2523.22  253.76 2523.04  265.43 2521.71  267.56 2521.72
  276.86 2521.76  308.74 2529.41  323.01 2532.14  340.13 2534.37  360.53 2538.33
   370.6  2542.6  382.92 2549.61  394.96 2557.93  404.54 2564.04  428.72 2577.09
#Mann= 3 ,-1 , 0
       0     .09       0  253.76     .05       0  267.56     .09       0
#XS Ineff= 2 , 0
       0     220    2560               0
Permanent Ineff=
       F       F
Bank Sta=253.76,267.56
Exp/Cntr=0.3,0.1

Type RM Length L Ch R = 1 ,29130.9 ,559.28,531,497.53
XS GIS Cut Line= 6
 1073881.1928371  838170.9741137 1073681.4949203  838180.7032803
 1073632.4011703   838185.901197 1073597.7032536   838184.994947
 1073561.9949203   838188.494947 1073500.5470036  838226.5782804
#Sta/Elev= 30
       0 2586.29   29.88  2575.8   34.66 2574.59    58.6 2566.97   63.88 2564.79
   67.45 2562.95  102.83 2541.14  130.92 2533.99  140.55 2531.96  177.57 2530.09
 199.932  2528.2 218.885  2524.7 225.596  2523.8 244.274  2519.1 246.786  2517.6
 249.376  2517.5 257.302  2516.6 260.559  2516.7 262.678  2517.1  264.13  2517.8
  270.84  2517.9 272.214  2519.3 284.221  2521.8 320.127    2525  322.94 2525.98
  340.08  2529.8  358.14 2535.49  369.32 2538.35  385.23 2544.78  392.41 2547.13
#Mann= 3 ,-1 , 0
       0     .09       0 249.376    .048       0  264.13     .09       0
#XS Ineff= 2 , 0
       0     200    2545               0
Permanent Ineff=
       F       F
Bank Sta=249.376,264.13
Exp/Cntr=0.3,0.1

Type RM Length L Ch R = 1 ,28599.9 ,57.82,56,52.28
XS GIS Cut Line= 6
 1073171.7865868  837852.0678635 1073231.2032535  838023.9011969
 1073238.2970035  838037.4011969 1073249.5990868  838082.2032803
 1073259.8074201  838106.8803636 1073289.1511701  838243.4741137
#Sta/Elev= 30
       0 2541.96    6.17 2541.69   19.54 2539.44   38.16 2533.64    45.9  2530.6
   62.95 2527.46   79.17 2526.16  122.07 2525.12  140.69 2523.98  151.51 2523.62
 175.042  2523.5 181.863  2520.6 190.409  2518.1 192.176  2516.6 197.189  2515.1
 202.531  2513.5 205.448  2513.6 212.433  2514.6 214.693  2514.9 234.129  2515.1
 244.442  2517.1 249.496  2518.5 271.192 2519.02  309.03 2523.88  326.26  2526.8
  335.43 2533.62  339.95  2537.3   360.3 2547.95  405.55 2573.37   410.9 2576.11
#Mann= 4 ,-1 , 0
       0     .05       0 181.863     .09       0 197.189     .04       0
 212.433     .09       0
#XS Ineff= 2 , 0
       0  161.55    2540               0
Permanent Ineff=
       F       F
#Block Obstruct= 2 ,-1
   39.87   88.31 2542.87  117.09  156.012535.241
Bank Sta=197.189,212.433
Exp/Cntr=0.5,0.3

Type RM Length L Ch R = 1 ,28543.9 ,27.68,25,26.8
BEGIN DESCRIPTION:
u/s of 19517 surveyed section
END DESCRIPTION:
XS GIS Cut Line= 6
 1073134.1720034  837875.2970302 1073163.2970034  838014.2032803
 1073183.0990868  838059.2970303 1073213.5990868   838105.901197
 1073220.9011701  838122.2970303 1073249.8595035   838207.494947
#Sta/Elev= 30
       0 2541.89   12.77 2539.29   26.54  2535.3    53.3 2528.18   75.12 2527.19
    86.2 2527.08   98.34 2526.38 141.944  2522.5 161.227  2522.8 167.762    2522
 173.728  2519.1  181.15  2518.1 188.572  2514.9 188.963  2513.5 191.306    2513
 195.745  2512.8 200.256  2513.4 212.259  2513.3 214.922  2513.8  224.44  2517.6
 239.461  2518.4 247.203  2517.9  258.78  2517.9  281.63 2519.06  289.53 2519.72
     306 2523.11  323.79 2533.71   336.8 2540.03  342.29 2544.32  355.13 2552.48
#Mann= 4 ,-1 , 0
       0     .05       0 161.227     .09       0 188.963     .04       0
 214.922     .09       0
#XS Ineff= 4 ,-1
       0  155.25    2540     156  162.01  2517.3  238.51     295  2517.3
   295.2  355.13    2540
Permanent Ineff=
       F       F       F       F
Bank Sta=188.963,214.922
Exp/Cntr=0.5,0.3

Type RM Length L Ch R = 3 ,28529.9 ,,,
BEGIN DESCRIPTION:
fbstr 6693
END DESCRIPTION:
Bridge Culvert--1,0,-1,-1, 0
Deck Dist Width WeirC Skew NumUp NumDn MinLoCord MaxHiCord MaxSubmerge Is_Ogee
11.9,11.5,2.6,0, 64, 62, , , 0.95, 0, 1,1,,
       0    3.38    8.51   10.54   12.55    19.7   30.06   40.61   47.59   60.58
    79.1   85.16   89.52   94.17   98.83  103.21  111.44  115.16  121.95  128.56
  130.84  133.23  135.73  139.04  142.86  149.71  156.12  157.01  159.74  164.39
  167.28  170.88  173.57  176.49  178.21  182.01  182.01  218.51  218.51  221.23
  222.69  228.81  239.11  239.99   240.8  249.41  250.65  258.77  275.79  276.31
  276.92  287.05   291.1  298.84   314.5  316.67  317.37  319.85  327.83  331.59
  344.45  345.03  347.14  351.62
 2540.49 2539.49 2538.68 2538.36 2538.04  2536.6 2532.98 2530.18 2528.08 2527.68
  2527.2 2526.72 2526.62  2526.3 2526.02  2525.6 2524.65 2524.23 2523.62 2522.93
  2522.6 2522.54 2522.38 2522.17 2522.08 2521.96 2521.74 2521.67 2521.46  2520.8
 2520.53 2520.12  2519.8 2519.45 2519.28  2517.3  2517.3  2517.3  2517.3 2516.98
 2517.43 2518.36  2517.9 2517.89 2517.88 2517.73 2517.74 2517.81 2519.09 2519.13
 2519.17 2519.79 2519.93 2520.75 2528.54 2529.62 2529.99  2531.4  2536.3 2538.04
 2545.05 2545.47 2546.88 2550.24
                                                                                
                                                                                
                                                                                
                                                 2516.25 2516.25
                                                                                
                                                                                
                                
       0    3.38    8.51   10.54   12.55    19.7   30.06   40.61   47.59   60.58
    79.1   85.16   89.52   94.17   98.83  103.21  111.44  115.16  121.95  128.56
  130.84  133.23  135.73  139.04  142.86  149.71  156.12  157.01  159.74  164.39
  167.28  170.88  173.57  176.49  178.21  188.74  188.74  225.24  225.24  228.81
  239.11  239.99   240.8  249.41  250.65  258.77  275.79  276.31  276.92  287.05
   291.1  298.84   314.5  316.67  317.37  319.85  327.83  331.59  344.45  345.03
  347.14  351.62
 2540.49 2539.49 2538.68 2538.36 2538.04  2536.6 2532.98 2530.18 2528.08 2527.68
  2527.2 2526.72 2526.62  2526.3 2526.02  2525.6 2524.65 2524.23 2523.62 2522.93
  2522.6 2522.54 2522.38 2522.17 2522.08 2521.96 2521.74 2521.67 2521.46  2520.8
 2520.53 2520.12  2519.8 2519.45 2519.28  2516.8  2516.8  2516.8  2516.8 2518.36
  2517.9 2517.89 2517.88 2517.73 2517.74 2517.81 2519.09 2519.13 2519.17 2519.79
 2519.93 2520.75 2528.54 2529.62 2529.99  2531.4  2536.3 2538.04 2545.05 2545.47
 2546.88 2550.24
                                                                                
                                                                                
                                                                                
                                                 2515.75 2515.75
                                                                                
                                                                                
                
BR Coef=-1 , 0 , 0 ,, 0 ,,,0.8,0,,0,
WSPro=,,,, 1 ,,,, 0 ,,,, 0 ,,,,-1 ,-1 ,-1 , 0 , 0 , 0 , 0 , 0
BC Design=,, 0 ,, 0 ,,,,,,

Type RM Length L Ch R = 1 ,28518.9 ,71.78,77,82.38
BEGIN DESCRIPTION:
d/s of 19157
END DESCRIPTION:
XS GIS Cut Line= 6
 1073088.8074201  837886.3595302 1073131.9949201  838022.4949469
 1073145.2032534  838047.2970303 1073173.9220034  838092.3803636
 1073180.2970034   838113.494947 1073218.1824201   838209.901197
#Sta/Elev= 30
       0 2540.48   22.11 2536.69   29.07 2535.17   45.46 2529.85   50.38 2528.61
   52.94 2528.24    94.4 2527.06  124.38 2524.17  138.47 2521.94 161.969  2522.2
 170.932  2520.7 179.157  2520.1 188.928  2518.9 200.879  2513.9  203.55  2513.2
 204.464  2512.7 206.995  2512.3   211.6  2512.5  216.45  2513.5 222.566  2514.2
 226.398  2515.6 244.992  2517.8 265.695  2516.9   265.7 2517.63  274.16 2518.34
  277.96 2518.23  301.23 2519.92  319.33 2528.62  339.03 2540.25  351.49 2547.31
#Mann= 5 ,-1 , 0
       0     .09       0   22.11     .05       0 170.932     .09       0
 200.879     .04       0  216.45     .09       0
#XS Ineff= 4 ,-1
       0  161.97    2530     168  178.74    2516  235.25     302    2516
  302.17  351.49    2530
Permanent Ineff=
       F       F       F       F
#Block Obstruct= 1 ,-1
   46.03   83.67    2534
Bank Sta=200.879,216.45
Exp/Cntr=0.5,0.3

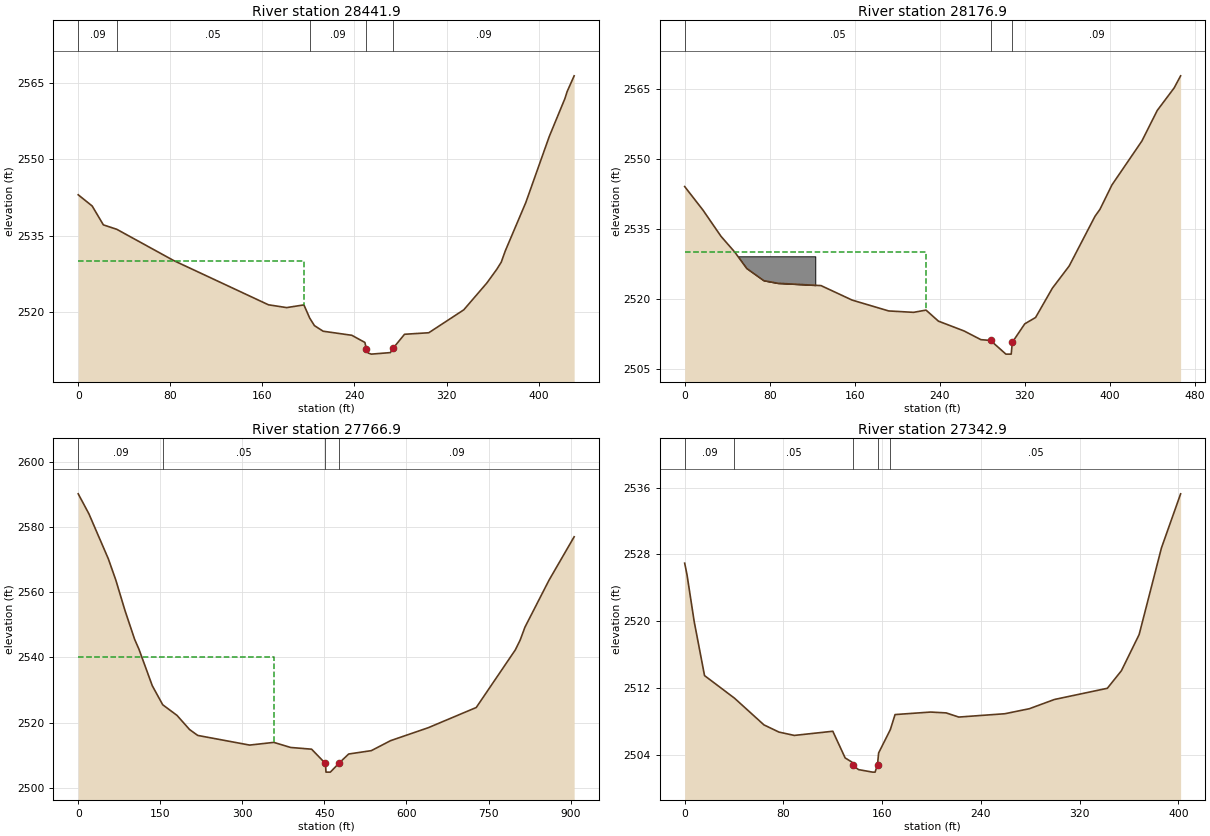
Type RM Length L Ch R = 1 ,28441.9 ,260.06,265,267.41
XS GIS Cut Line= 6
   1073043.43242  837866.4428635 1073086.7032534  838062.7970303
 1073090.9011701  838089.0991136 1073105.4949201   838142.401197
 1073107.4949201   838163.401197 1073170.7657534   838272.682447
#Sta/Elev= 30
       0    2543   12.13  2540.8   21.87 2537.09   33.53 2536.22   82.88 2530.09
   165.3 2521.39  181.09 2520.84 196.092 2521.37  201.09  2518.8 205.226  2517.3
  212.81  2516.2 237.714  2515.4 249.047    2514 250.425  2512.7  252.02  2511.9
 254.691  2511.7 271.237    2512 273.736  2512.9 283.517  2515.6 304.586  2515.9
  334.98  2520.4  354.99 2525.66  363.71 2528.38  367.54 2529.76  371.07 2531.99
  388.88 2541.48   409.2 2554.42  422.85  2561.9  424.79 2563.28  430.88 2566.37
#Mann= 5 ,-1 , 0
       0     .09       0   33.53     .05       0  201.09     .09       0
 250.425     .04       0 273.736     .09       0
#XS Ineff= 2 , 0
       0  196.09    2530               0
Permanent Ineff=
       F       F
Bank Sta=250.425,273.736
Exp/Cntr=0.3,0.1

Type RM Length L Ch R = 1 ,28176.9 ,413.21,410,408.46
XS GIS Cut Line= 4
 1072927.6095033  837841.9949468 1072855.5261699  838065.2866136
 1072840.6407533  838149.9116137 1072850.0470033  838295.6407804
#Sta/Elev= 30
       0 2544.06   17.23 2539.02   34.18 2533.42    47.4 2529.97   58.33 2526.55
   74.42 2523.94   87.63 2523.38  128.27 2522.88  157.56 2519.78  191.93 2517.46
  215.36 2517.16  227.08 2517.64  238.72 2515.28  262.86 2513.18  278.68 2511.32
   287.8 2511.15  302.212508.225  307.212508.225   308.3 2510.77  319.96  2514.7
  330.15 2516.06  345.92 2522.32  361.75 2527.07  386.04  2537.7  390.74  2539.2
  402.02 2544.42   430.2 2553.81  444.57 2560.32  460.45 2565.13   466.6 2567.74
#Mann= 3 ,-1 , 0
       0     .05       0   287.8     .04       0   308.3     .09       0
#XS Ineff= 2 , 0
       0  227.08    2530               0
Permanent Ineff=
       F       F
#Block Obstruct= 1 ,-1
   50.04  122.872529.142
Bank Sta=287.8,308.3
Exp/Cntr=0.3,0.1

Type RM Length L Ch R = 1 ,27766.9 ,424.08,424,423.92
XS GIS Cut Line= 6
 1072480.3803364  837578.5782801 1072446.2449198  838071.1407803
 1072446.2449198  838145.9220303 1072447.8699198  838301.9845304
 1072452.7449198  838419.0261971 1072465.7553364  838482.4324471
#Sta/Elev= 30
       0 2590.28   19.46 2584.17   55.08  2570.3   68.84 2563.72   85.41 2554.47
  103.11 2545.57  110.97 2542.55  135.39 2531.31  154.44 2525.46   180.7 2522.17
  203.52 2517.84  218.48 2516.03  313.29 2513.06  357.53 2513.89  388.26 2512.33
  426.58  2511.8  451.87 2507.41  452.87 2504.75  460.86 2504.75  477.38 2507.62
  494.35 2510.32   535.7 2511.35   571.1 2514.43  639.65 2518.39  727.52 2524.61
  798.95 2542.32  807.77 2545.33  816.56 2549.31  860.57 2563.75  906.47 2577.08
#Mann= 4 ,-1 , 0
       0     .09       0  154.44     .05       0  451.87     .04       0
  477.38     .09       0
#XS Ineff= 2 , 0
       0  357.53    2540               0
Permanent Ineff=
       F       F
Bank Sta=451.87,477.38
Exp/Cntr=0.3,0.1

Type RM Length L Ch R = 1 ,27342.9 ,56.01,54,49.85
XS GIS Cut Line= 6
 1072028.2136696  837912.3907802 1072023.4011696  838001.0991136
 1072026.2032529   838123.494947 1072030.2970029   838132.901197
 1072052.5990862   838251.213697 1072077.3282529  838305.1720304
#Sta/Elev= 30
       0 2526.95    1.92 2525.53    7.71 2519.95    16.1 2513.47   40.32 2510.77
   64.27 2507.56   76.41  2506.7  88.855  2506.3 120.041  2506.8 130.048  2503.6
 135.554  2503.1 136.116  2502.7 140.939  2502.2 152.232  2501.9 154.321  2501.9
 156.251  2502.8 157.175  2504.2 166.659    2507 170.477  2508.8 199.252  2509.1
 211.871    2509 222.118  2508.5 259.453  2508.9  279.29  2509.5  299.67 2510.61
   342.5 2511.95  353.88 2514.05  368.27 2518.39  386.33 2528.77  401.88 2535.26
#Mann= 5 ,-1 , 0
       0     .09       0   40.32     .05       0 136.116     .04       0
 156.251     .09       0 166.659     .05       0
Bank Sta=136.116,156.251
Exp/Cntr=0.5,0.3