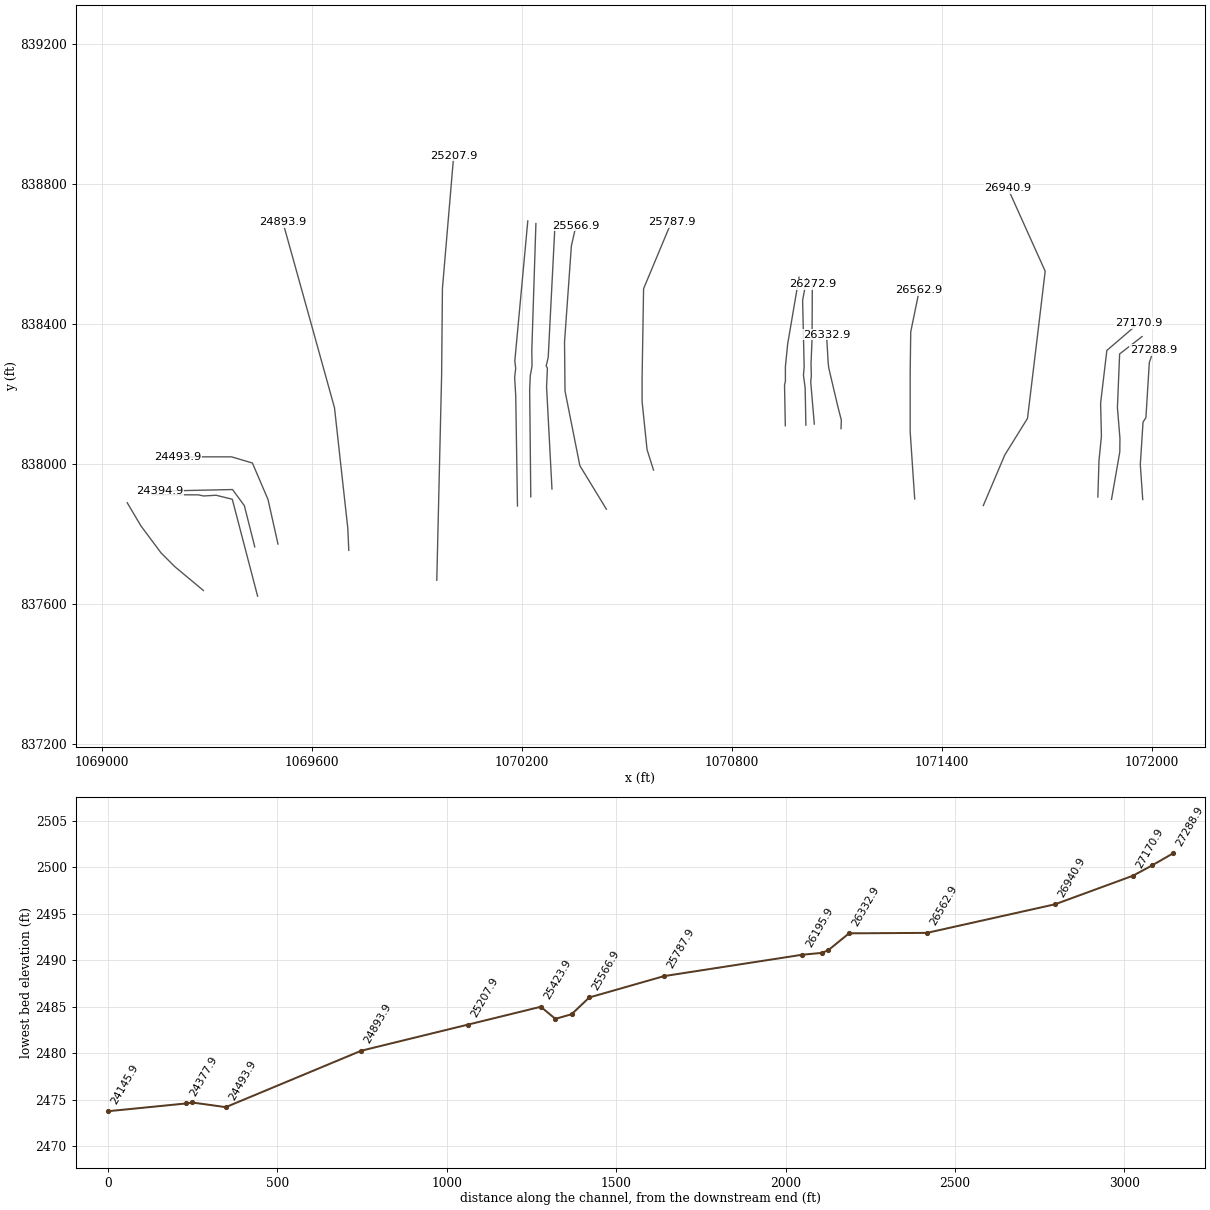
HEC-RAS study dtl_cane_crk.prj: cane creek

--- dtl_cane_crk.g01 (geometry) --- (continued)

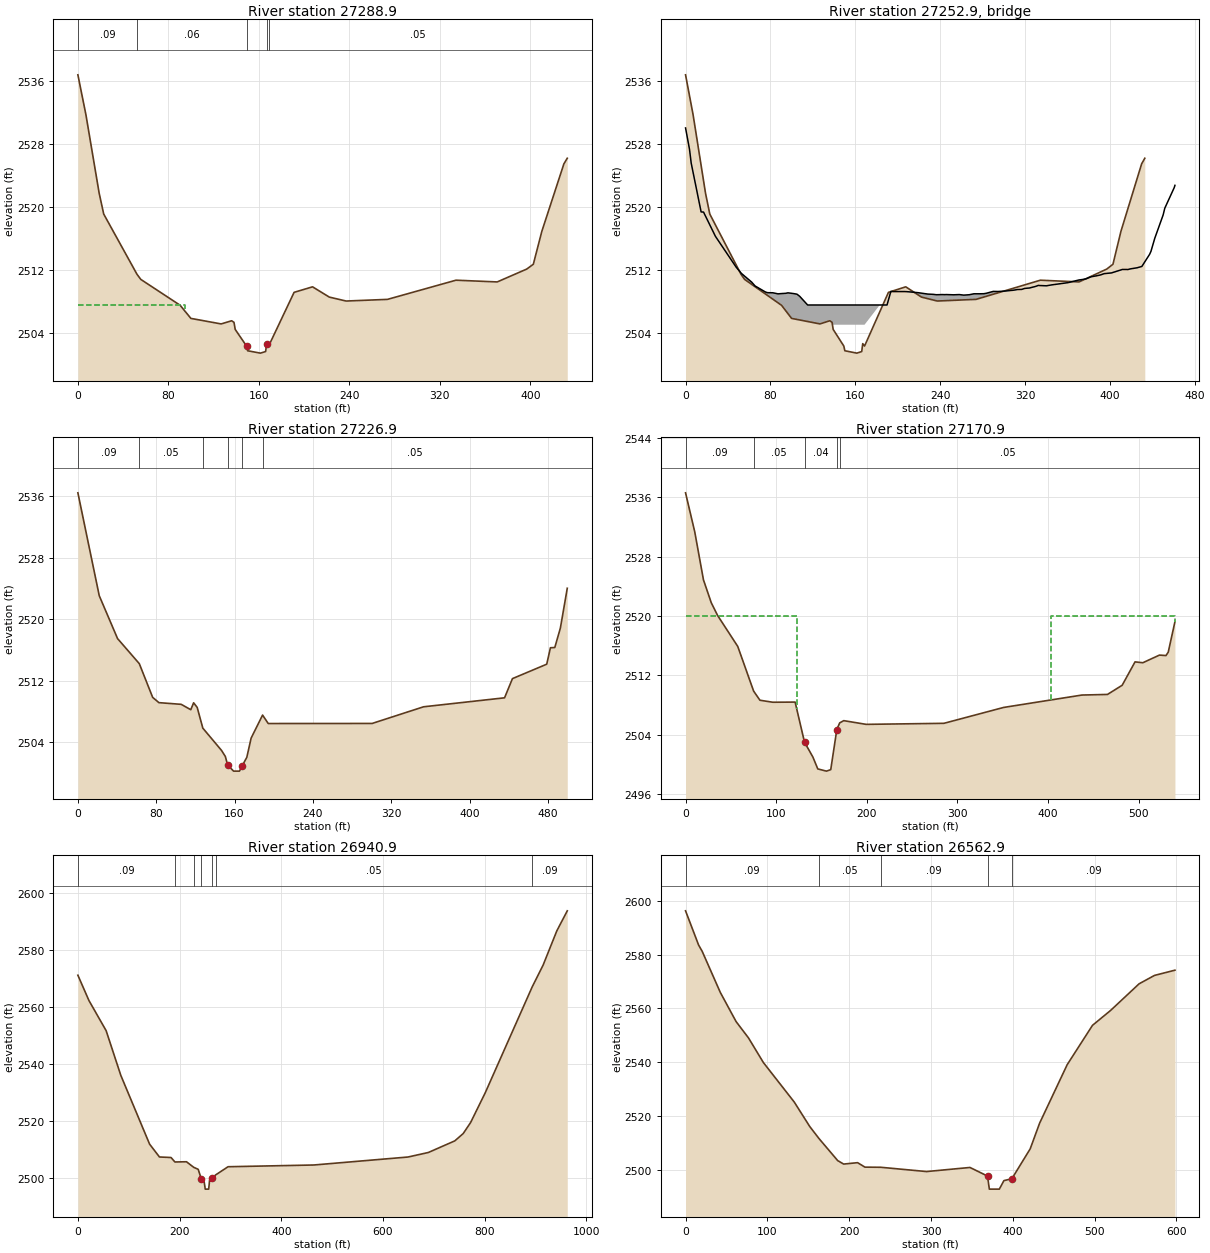
Type RM Length L Ch R = 1 ,27288.9 ,61.21,62,65.83
BEGIN DESCRIPTION:
u/s of 18240
END DESCRIPTION:
XS GIS Cut Line= 6
 1071974.2240862  837898.2553635 1071967.2970029  837997.9011969
 1071975.0990862   838119.494947 1071983.2970029   838131.901197
 1071993.0574195  838289.3595304 1072005.2449195  838325.0991137
#Sta/Elev= 30
       0 2536.76     7.1 2531.71   18.82 2521.76   22.84 2519.12    52.3 2511.48
   55.63 2510.84   90.43 2507.56  99.895  2505.9 126.631  2505.2 135.933  2505.6
  138.01  2505.4 139.091  2504.5 149.085  2502.4  150.08  2501.8 161.328  2501.5
 165.958  2501.7 166.909  2502.7  168.64  2502.4 191.137  2509.2 207.447  2509.9
 222.243  2508.6 237.125  2508.1  273.69 2508.31  334.24 2510.74  370.69 2510.52
  396.79 2512.15  402.62 2512.76  410.14 2516.93  429.64 2525.48  432.63 2526.19
#Mann= 5 ,-1 , 0
       0     .09       0    52.3     .06       0 149.085     .04       0
 166.909     .09       0  168.64     .05       0
#XS Ineff= 2 , 0
       0      95  2507.6   199.8       0  2507.6
Permanent Ineff=
       F       F
Bank Sta=149.085,166.909
Exp/Cntr=0.5,0.3

Type RM Length L Ch R = 3 ,27252.9 ,,,
BEGIN DESCRIPTION:
fbstr 1366
END DESCRIPTION:
Bridge Culvert--1,0,-1,-1, 0
Deck Dist Width WeirC Skew NumUp NumDn MinLoCord MaxHiCord MaxSubmerge Is_Ogee
27,30,2.6,0, 90, 91, , , 0.95, 0, 1,1,,
       0    3.77    5.32   14.67   16.94   28.13   47.68   52.63   62.27   65.55
   66.27   75.32    77.2   82.14   87.07   90.79   94.39   96.47  102.05  104.95
  107.52     115     115   189.8   189.8  193.38  195.58  206.54  209.33  213.39
  218.21  219.04  219.21  219.56  228.33     233  236.33  241.83  242.64   243.5
  245.74  252.61  257.87  262.09  267.34  271.73  277.75   281.1  283.52  289.82
  294.43   299.8  308.75  310.31  312.51  316.58  319.52  323.93  329.94  332.26
  333.95  339.95  345.16  348.99  360.31  362.42   370.6  374.06  377.42  382.15
     387  390.95  394.36  401.21  411.25  411.47  411.85  415.21  416.69  416.87
  418.87  425.23  429.83  437.16  438.41  442.06  449.91  451.45  460.34  461.01
 2530.03 2527.29 2525.57 2519.39 2519.37  2516.3 2512.39  2511.6  2510.5    2510
 2509.95 2509.24 2509.16 2509.15 2509.01 2509.05 2509.08 2509.14 2509.04 2508.97
  2508.7  2507.6  2507.6  2507.6  2507.6 2509.31  2509.3  2509.3 2509.28 2509.23
 2509.17 2509.16 2509.16 2509.15 2508.98 2508.95  2508.9 2508.92 2508.92 2508.91
 2508.92 2508.89 2508.92 2508.85  2508.9 2509.02 2509.02 2509.03 2509.09 2509.32
 2509.31 2509.35 2509.47  2509.5 2509.56 2509.57  2509.7 2509.75 2509.96 2510.08
 2510.06 2510.03 2510.15 2510.22 2510.43  2510.5 2510.77 2510.83 2510.92 2511.18
 2511.29 2511.41 2511.57 2511.66 2512.09  2512.1  2512.1  2512.1 2512.09  2512.1
 2512.17 2512.31 2512.48 2514.02 2514.39 2516.07 2519.01 2519.86 2522.47 2522.76
                                                                                
                                                                                
                  2505.1  2505.1
                                                                                
                                                                                
                                                                                
                                                                                
                                                                                
                                                                                
       0    3.77    5.32   14.67   16.94   28.13   47.68   52.63   62.27   65.55
   66.27   75.32    77.2   82.14   87.07   90.79   94.39   96.47  102.05  104.95
  107.52     115     115   189.8   189.8  193.38  195.58  206.54  209.33  213.39
  218.21  219.04  219.21  219.56  228.33     233  236.33  241.83  242.64   243.5
  245.74  252.61  257.87  262.09  267.34  271.73  277.75   281.1  283.52  289.82
  294.43   299.8  308.75  310.31  312.51  316.58  319.52  323.93  329.94  332.26
  333.95  339.95  345.16  348.99  360.31  362.42   370.6  374.06  377.42  382.15
     387  390.95  394.36  401.21  411.25  411.47  411.85  415.21  416.69  416.87
  418.87  425.23  429.83  437.16  438.41  442.06  449.91  451.45  460.34  461.01
  499.26
 2530.03 2527.29 2525.57 2519.39 2519.37  2516.3 2512.39  2511.6  2510.5    2510
 2509.95 2509.24 2509.16 2509.15 2509.01 2509.05 2509.08 2509.14 2509.04 2508.97
  2508.7  2506.2  2506.2  2506.2  2506.2 2509.31  2509.3  2509.3 2509.28 2509.23
 2509.17 2509.16 2509.16 2509.15 2508.98 2508.95  2508.9 2508.92 2508.92 2508.91
 2508.92 2508.89 2508.92 2508.85  2508.9 2509.02 2509.02 2509.03 2509.09 2509.32
 2509.31 2509.35 2509.47  2509.5 2509.56 2509.57  2509.7 2509.75 2509.96 2510.08
 2510.06 2510.03 2510.15 2510.22 2510.43  2510.5 2510.77 2510.83 2510.92 2511.18
 2511.29 2511.41 2511.57 2511.66 2512.09  2512.1  2512.1  2512.1 2512.09  2512.1
 2512.17 2512.31 2512.48 2514.02 2514.39 2516.07 2519.01 2519.86 2522.47 2522.76
    2523
                                                                                
                                                                                
                  2503.7  2503.7
                                                                                
                                                                                
                                                                                
                                                                                
                                                                                
                                                                                
        
Pier Skew, UpSta & Num, DnSta & Num=  ,135.254, 2 ,135.254, 2 , 0 , 0 , 0 ,,
       4       4
  2501.5  2505.1
       4       4
  2500.1  2503.7
Pier Skew, UpSta & Num, DnSta & Num=  ,185.896, 2 ,185.896, 2 , 0 , 0 , 0 ,,
       4       4
  2501.5  2505.1
       4       4
  2500.1  2503.7
BR Coef=-1 , 0 , 0 ,, 0 ,,,0.8,0,,0,
WSPro=,,,, 1 ,,,, 0 ,,,, 0 ,,,,-1 ,-1 ,-1 , 0 , 0 , 0 , 0 , 0
BC Design=,, 0 ,, 0 ,,,,,,

Type RM Length L Ch R = 1 ,27226.9 ,55.88,56,54.13
BEGIN DESCRIPTION:
d/s of 18240
END DESCRIPTION:
XS GIS Cut Line= 6
 1071885.0470028  837898.7241135 1071908.7032528  838034.2970303
 1071909.0990862  838073.0991136 1071901.9011695  838160.5991137
 1071908.2345028  838313.9428637 1071972.3803362  838363.5470304
#Sta/Elev= 30
       0 2536.45   21.84 2523.04   40.54 2517.46   62.72  2514.2   76.36 2509.81
   82.75 2509.12 105.501  2508.9 115.296  2508.2 118.195  2509.1 121.843  2508.5
  127.59  2505.8 146.682  2502.9  150.63  2502.1 152.879    2501 159.026  2500.2
 165.023  2500.2 167.822  2500.9 172.519    2502 176.917  2504.5 188.612  2507.5
 194.409  2506.4  300.51 2506.41  353.03 2508.58  435.72 2509.75   443.8 2512.25
   478.8 2514.13  482.57 2516.27  487.03  2516.3  492.72 2518.83  499.77 2524.02
#Mann= 6 ,-1 , 0
       0     .09       0   62.72     .05       0  127.59     .09       0
 152.879     .04       0 167.822     .09       0 188.612     .05       0
#XS Ineff= 2 , 0
       0     100 2505.24  194.41       0 2505.24
Permanent Ineff=
       F       F
Bank Sta=152.879,167.822
Exp/Cntr=0.5,0.3

Type RM Length L Ch R = 1 ,27170.9 ,238.11,230,224.76
XS GIS Cut Line= 6
 1071846.0470028  837905.4220302 1071849.2032528  838008.7032803
 1071856.2032528   838078.901197 1071853.9011695  838173.5991137
 1071871.7136695  838323.9220304 1071962.1615862  838401.5261971
#Sta/Elev= 30
       0 2536.59   10.16 2531.33   19.78 2524.86   28.39 2521.78   35.32 2520.08
   57.59  2515.9   75.11 2509.88   82.07 2508.65   96.29 2508.38 120.878  2508.4
 131.243    2503 140.475    2501 145.874  2499.4  155.43  2499.1 160.181  2499.3
 166.875  2504.7  170.06  2505.6 174.541  2505.9 199.267  2505.4  285.01 2505.54
  350.94 2507.68  437.36 2509.35  465.46 2509.43   481.7 2510.67  495.88 2513.82
  504.43  2513.7  522.78 2514.73  530.01 2514.67  532.51 2515.13  539.88 2519.22
#Mann= 5 ,-1 , 0
       0     .09       0   75.11     .05       0 131.243     .04       0
 166.875     .09       0  170.06     .05       0
#XS Ineff= 2 , 0
       0  122.67    2520  402.83       0    2520
Permanent Ineff=
       F       F
Bank Sta=131.243,166.875
Exp/Cntr=0.3,0.1

Type RM Length L Ch R = 1 ,26940.9 ,367.53,378,383.72
XS GIS Cut Line= 6
  1071518.755336  837881.0157802 1071580.0782527  838025.3282803
 1071645.0157527  838129.9428636 1071677.4845027  838398.7136971
 1071695.5261694  838550.2345305  1071589.099086  838786.5366139
#Sta/Elev= 30
       0 2571.08   21.71 2562.21   55.56 2551.62   84.43 2535.94     141 2511.82
  160.43  2507.3  183.15 2507.12  190.85 2505.55  213.54 2505.63  227.87 2503.67
  236.64 2502.97  242.96 2499.44  247.92 2499.15  250.462496.025  257.252496.025
  258.98 2499.15  263.32 2499.85  270.91 2501.01  295.31 2503.88  463.98 2504.49
  649.14 2507.29  689.23 2508.88  741.29 2512.96  757.73 2515.52  772.32 2519.39
  801.32 2529.92  893.64 2567.06     915 2574.66  941.89 2586.65  962.41 2593.67
#Mann= 7 ,-1 , 0
       0     .09       0  190.85     .05       0  227.87     .09       0
  242.96     .04       0  263.32     .09       0  270.91     .05       0
  893.64     .09       0
Bank Sta=242.96,263.32
Exp/Cntr=0.3,0.1

Type RM Length L Ch R = 1 ,26562.9 ,225.09,230,231.52
XS GIS Cut Line= 5
 1071322.7865859  837899.9532802 1071309.8386692  838092.4428636
 1071309.8386692   838259.057447 1071311.4636692  838377.1407804
 1071335.7240859  838495.2241138
#Sta/Elev= 30
       0 2596.24   15.98 2583.53   20.33 2581.22    42.5 2565.95    61.8 2555.13
   77.01 2549.04   95.16 2539.92  132.97 2525.23  151.82 2516.18  163.15 2511.71
  185.96 2503.54  193.26 2502.25  210.29 2502.77  219.28 2501.11  238.62 2501.06
  294.61 2499.47  347.65 2500.99  369.08  2497.8  371.33 2492.95  383.52 2492.95
  389.12  2496.1  398.88 2496.82  421.27  2507.9  432.74  2517.4  466.43 2539.11
  497.41 2553.74  519.43 2559.24  554.37 2569.15   573.2 2572.27  598.18 2574.21
#Mann= 5 ,-1 , 0
       0     .09       0  163.15     .05       0  238.62     .09       0
  369.08     .04       0  398.88     .09       0
Bank Sta=369.08,398.88
Exp/Cntr=0.3,0.1

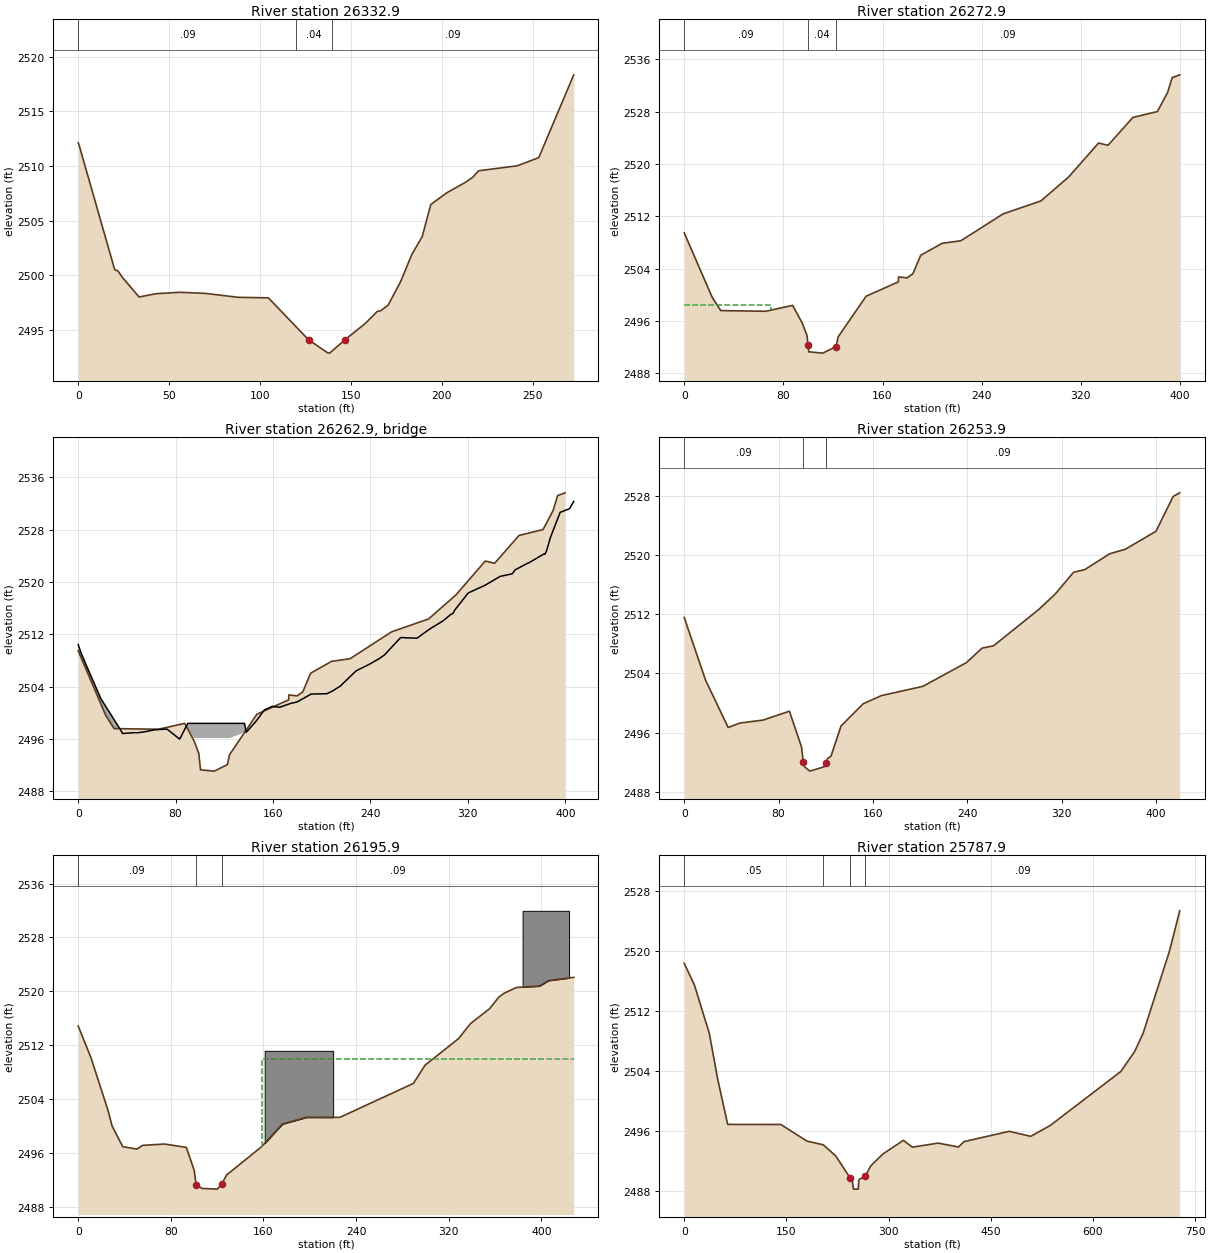
Type RM Length L Ch R = 1 ,26332.9 ,64.31,60.65,58.39
XS GIS Cut Line= 6
 1071112.3647343  838100.7189716 1071113.1564009  838125.0731383
 1071102.5939009  838166.2918883 1071077.1980676  838274.1981384
 1071075.6980676  838287.1981384 1071070.9584842  838368.5314719
#Sta/Elev= 30
       0 2512.13     .53 2511.89   20.06 2500.53   21.88 2500.41   24.37 2499.81
   33.46 2498.03   42.81 2498.33   56.01 2498.46   69.92 2498.36   87.97    2498
   104.6 2497.95  126.67 2494.12  137.16 2492.93  138.27  2492.9  146.84 2494.14
  157.81  2495.6  164.46 2496.71  166.41 2496.78  170.45 2497.29  177.31 2499.44
  183.49 2501.93  189.16 2503.54  193.89 2506.48  202.77 2507.56  213.07 2508.52
  216.91 2508.97  220.17 2509.56  241.48 2510.02  253.26 2510.76  272.48 2518.33
#Mann= 3 ,-1 , 0
       0     .09       0 120.021     .04       0 139.301     .09       0
Bank Sta=126.67,146.84
Exp/Cntr=0.5,0.3

Type RM Length L Ch R = 1 ,26272.9 ,18.99,19,19.26
BEGIN DESCRIPTION:
U/S OF 17250 SURVEYED SECTION
END DESCRIPTION:
XS GIS Cut Line= 6
 1071035.9845024  838113.6407803 1071025.7032524  838234.2970304
 1071027.4949191  838250.7970304 1071026.5990858  838285.7032804
 1071029.4636691  838354.7553637 1071030.3178358  838512.5261972
#Sta/Elev= 30
       0 2509.49   22.52 2499.66   29.48  2497.6  65.808  2497.5  87.477  2498.4
  95.233  2495.7  99.071  2493.8  99.871  2492.3 100.511  2491.3 111.785  2491.1
  122.54  2492.1 124.259  2493.6 146.768  2499.8 172.915    2502  172.92 2502.75
  179.72  2502.6   184.5 2503.23  190.83 2506.06  208.08 2507.88  223.21 2508.28
  257.39 2512.39  287.76 2514.36  310.19 2518.03  334.29 2523.21  341.99 2522.87
  361.98 2527.12  381.78 2528.03  389.99 2530.94  393.73 2533.22   399.8 2533.64
#Mann= 3 ,-1 , 0
       0     .09       0  99.871     .04       0  122.54     .09       0
#XS Ineff= 2 , 0
       0      70  2498.4     156       0  2498.4
Permanent Ineff=
       F       F
Bank Sta=99.871,122.54
Exp/Cntr=0.5,0.3

Type RM Length L Ch R = 3 ,26262.9 ,,,
BEGIN DESCRIPTION:
FBSTR 1904
END DESCRIPTION:
Bridge Culvert--1,0,-1,-1, 0
Deck Dist Width WeirC Skew NumUp NumDn MinLoCord MaxHiCord MaxSubmerge Is_Ogee
10,5,2.6,0, 78, 79, , , 0.95, 0, 1,1,,
       0    2.17    7.52   18.67   34.96   36.43   36.94   37.77   45.31   45.87
      49   54.72   57.98   63.02   66.03   70.81   72.99   83.35      90      90
   136.6   136.6  137.96  146.01  152.92  157.42   159.3  159.38  163.81  165.64
  165.98  175.63  177.03  180.04  180.69  189.77  190.77  191.16  204.21  204.66
  208.91   214.3  214.88  228.19  228.69  238.45  239.26  247.24  251.51   264.5
   265.7  270.04   278.3  284.66  289.66  298.99   301.4  306.24  307.62  309.39
  320.27  333.84  334.06  334.32  346.54  356.48  358.68   368.9  370.26  382.36
  383.24  384.22  384.57  387.83  395.77  403.51  406.25  406.93
 2510.45 2509.25 2506.91 2502.16 2497.34 2496.85 2496.86 2496.86 2496.97 2496.98
 2496.97 2497.12 2497.23 2497.43 2497.46  2497.5 2497.52 2495.99  2498.4  2498.4
  2498.4  2498.4 2497.03 2498.72 2500.46 2500.83    2501    2501 2500.89 2500.88
  2500.9 2501.52 2501.54 2501.71 2501.77 2502.72 2502.82 2502.88 2502.93 2502.98
 2503.35 2503.99 2504.04 2506.42 2506.47 2507.37 2507.45  2508.3 2508.86 2511.46
 2511.52 2511.47 2511.42 2512.29 2512.94 2513.99 2514.34 2515.09 2515.17 2515.75
 2518.33 2519.49 2519.53 2519.53 2520.87 2521.26 2521.85 2522.86 2522.96 2524.28
 2524.25  2524.6 2524.75 2526.83 2530.65 2531.22  2532.1 2532.33
                                                                                
                                                                         2496.15
 2496.15
                                                                                
                                                                                
                                                                                
                                                                                
                                                                
       0    2.17    7.52   18.67   34.96   36.43   36.94   37.77   45.31   45.87
      49   54.72   57.98   63.02   66.03   70.81   72.99   83.35      90      90
   136.6   136.6  137.96  146.01  152.92  157.42   159.3  159.38  163.81  165.64
  165.98  175.63  177.03  180.04  180.69  189.77  190.77  191.16  204.21  204.66
  208.91   214.3  214.88  228.19  228.69  238.45  239.26  247.24  251.51   264.5
   265.7  270.04   278.3  284.66  289.66  298.99   301.4  306.24  307.62  309.39
  320.27  333.84  334.06  334.32  346.54  356.48  358.68   368.9  370.26  382.36
  383.24  384.22  384.57  387.83  395.77  403.51  406.25  406.93  420.02
 2510.45 2509.25 2506.91 2502.16 2497.34 2496.85 2496.86 2496.86 2496.97 2496.98
 2496.97 2497.12 2497.23 2497.43 2497.46  2497.5 2497.52 2495.99  2498.1  2498.1
  2498.1  2498.1 2497.03 2498.72 2500.46 2500.83    2501    2501 2500.89 2500.88
  2500.9 2501.52 2501.54 2501.71 2501.77 2502.72 2502.82 2502.88 2502.93 2502.98
 2503.35 2503.99 2504.04 2506.42 2506.47 2507.37 2507.45  2508.3 2508.86 2511.46
 2511.52 2511.47 2511.42 2512.29 2512.94 2513.99 2514.34 2515.09 2515.17 2515.75
 2518.33 2519.49 2519.53 2519.53 2520.87 2521.26 2521.85 2522.86 2522.96 2524.28
 2524.25  2524.6 2524.75 2526.83 2530.65 2531.22  2532.1 2532.33 2528.41
                                                                                
                                                                         2494.85
 2494.85
                                                                                
                                                                                
                                                                                
                                                                                
                                                                        
BR Coef=-1 , 0 , 0 ,, 0 ,,,0.8,-1,,0,
WSPro=,,,, 1 ,,,, 0 ,,,, 0 ,,,,-1 ,-1 ,-1 , 0 , 0 , 0 , 0 , 0
BC Design=,, 0 ,, 0 ,,,,,,

Type RM Length L Ch R = 1 ,26253.9 ,57.27,58,54.72
BEGIN DESCRIPTION:
D/S OF 17250 SURVEYED SECTION
END DESCRIPTION:
XS GIS Cut Line= 6
 1071011.9115858  838110.6095303 1071009.7970024   838216.901197
 1071004.9949191  838253.2032804 1071006.9949191  838276.7032804
 1071002.5678357  838467.2449471 1071014.2449191  838528.5886972
#Sta/Elev= 30
       0 2511.57   18.12 2503.09   37.26  2496.7  47.294  2497.3  66.909  2497.7
   89.17  2498.9  99.376  2494.1 101.014    2492  101.98  2491.4 106.517  2490.8
 118.865  2491.4 120.251  2491.9 121.469  2492.5 124.367  2492.8 132.936  2496.9
 151.668  2499.9 166.999    2501  202.34 2502.26  239.28 2505.47  252.46 2507.42
  262.22 2507.74  300.52 2512.64  314.66 2514.76  329.99 2517.67   339.5 2518.03
  360.61 2520.17  374.01 2520.79  399.92 2523.22  414.45 2527.92  420.02 2528.41
#Mann= 3 ,-1 , 0
       0     .09       0 101.014     .04       0 120.251     .09       0
#XS Ineff= 2 , 0
       0      70 2496.35     156       0 2496.35
Permanent Ineff=
       F       F
Bank Sta=101.014,120.251
Exp/Cntr=0.5,0.3

Type RM Length L Ch R = 1 ,26195.9 ,408.57,408,409.62
XS GIS Cut Line= 6
 1070953.1615857  838108.8907803 1070950.9011691   838224.994947
 1070953.4011691  838236.2970304 1070953.4011691  838277.7032804
 1070959.8386691  838342.0782804 1070992.3386691  838532.9741138
#Sta/Elev= 30
       0 2514.83   10.97 2510.16   25.55 2502.41   29.27 2499.99   38.46 2496.91
    50.7 2496.55  55.543  2497.1  74.542  2497.3   93.37  2496.8 100.174  2493.4
 101.886  2491.2 107.192  2490.7 120.072  2490.6 123.795  2491.3  128.16  2492.7
  158.37  2496.9  176.33 2500.27  197.22 2501.27  225.96 2501.26  289.44  2506.3
  299.57 2509.02  328.39 2512.95  338.88 2515.21  355.31 2517.41  363.07  2519.1
  367.82  2519.7  378.45 2520.56  398.34 2520.77   406.1 2521.58  427.91 2522.06
#Mann= 3 ,-1 , 0
       0     .09       0 101.886     .04       0 123.795     .09       0
#XS Ineff= 2 , 0
       0                  158.37       0    2510
Permanent Ineff=
       F       F
#Block Obstruct= 2 ,-1
  161.05  220.152511.146  383.76  423.912531.943
Bank Sta=101.886,123.795
Exp/Cntr=0.3,0.1

Type RM Length L Ch R = 1 ,25787.9 ,222.06,221,216.65
XS GIS Cut Line= 6
 1070576.6303355  837982.4220302 1070558.1824189  838040.5886969
 1070543.9949189  838178.1928637 1070543.9949189   838244.869947
 1070548.2553355  838500.2241138 1070627.6928356  838690.3178639
#Sta/Elev= 30
       0 2518.38   14.85 2515.53   36.81 2509.07    49.3 2502.89   63.85 2496.92
  141.89 2496.91  180.08  2494.7  204.26  2494.2  222.54 2492.71  243.34 2489.83
  246.51 2489.64  248.47  2488.3  255.49  2488.3  256.37 2489.56  266.05 2490.05
  273.88  2491.4  291.85 2492.99  321.77  2494.8  334.86 2493.89  372.84 2494.43
  402.64 2493.91   410.8 2494.63  477.26    2496  508.67 2495.33  537.22 2496.77
  640.98 2503.97  661.21 2506.62  673.66 2509.05  712.14 2519.92  727.46 2525.37
#Mann= 4 ,-1 , 0
       0     .05       0  204.26     .09       0  243.34     .04       0
  266.05     .09       0
Bank Sta=243.34,266.05
Exp/Cntr=0.3,0.1

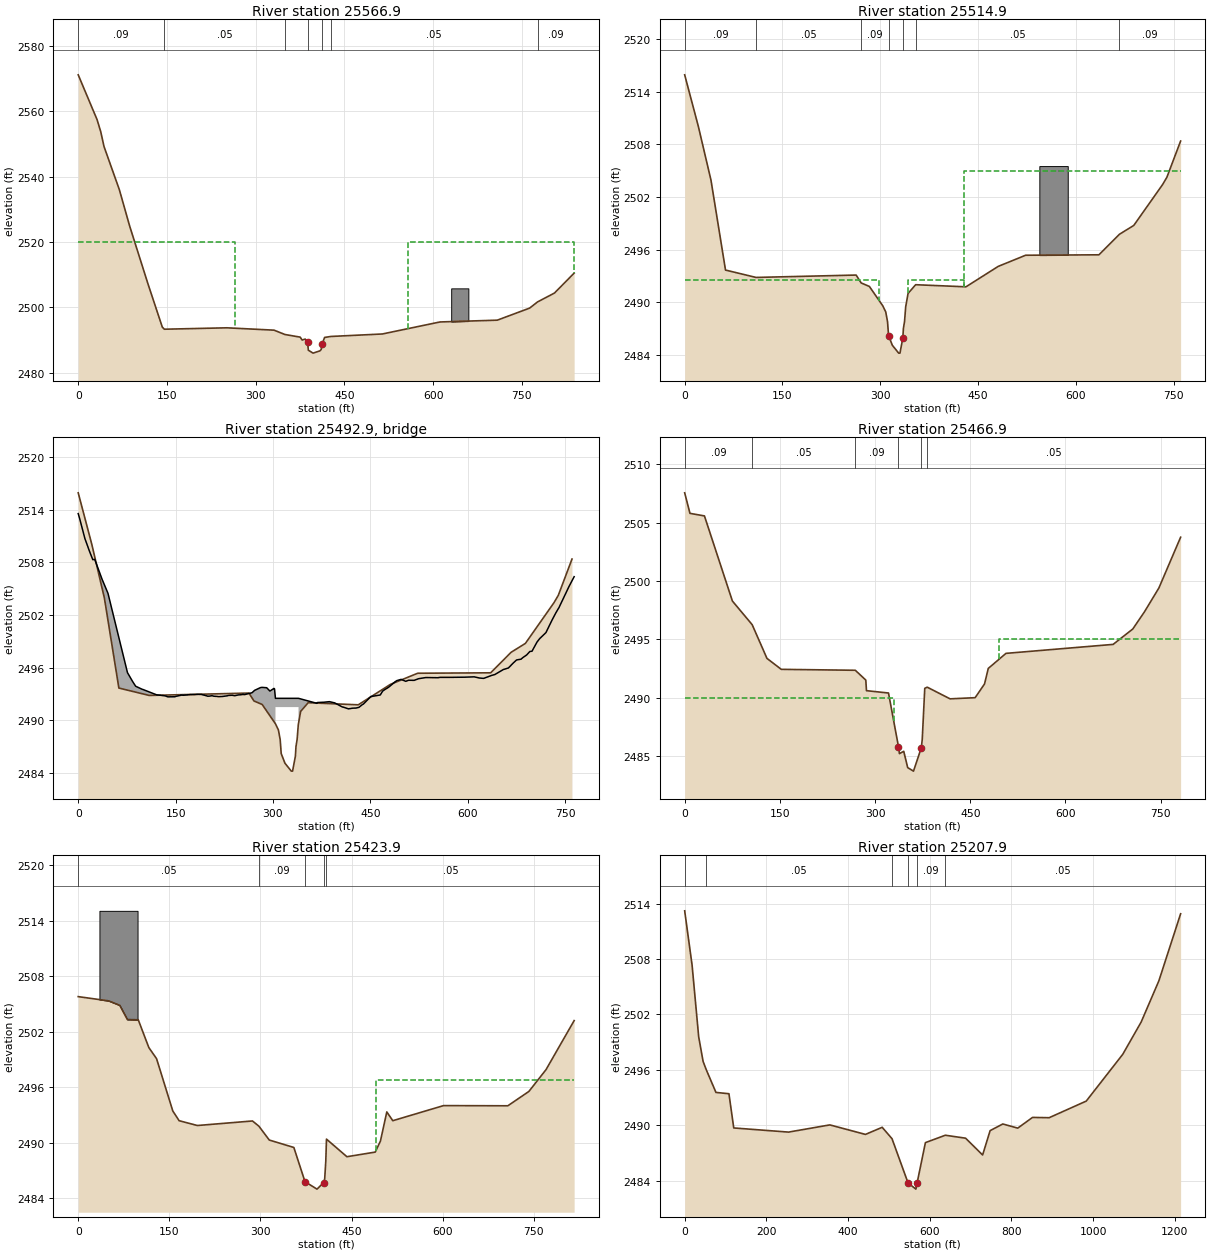
Type RM Length L Ch R = 1 ,25566.9 ,50.72,52,55.56
BEGIN DESCRIPTION:
surveyed section
END DESCRIPTION:
XS GIS Cut Line= 6
 1070441.9949188  837870.7136969 1070366.1511688  837995.0261969
 1070323.7970021  838208.0991137 1070322.4011688  838347.9011971
 1070341.9845021  838622.4428639 1070354.9636688  838679.5574472
#Sta/Elev= 30
       0  2571.2   31.96 2557.45   38.13 2553.75   43.59 2549.27   69.54 2536.04
   86.98  2524.9     118 2507.16  142.14 2493.98  145.62 2493.32  251.28 2493.75
   331.1 2493.03 349.501  2491.7 375.238  2490.9 378.591    2490 383.705  2490.3
 387.813  2489.3 388.986  2486.9 396.951    2486 408.687  2486.7 410.699  2487.1
 412.376  2488.8 416.484  2490.8 426.879  2491.1  514.08 2491.86  611.53 2495.54
  708.37 2496.09  763.04 2499.78  776.51 2501.68  805.04 2504.39  838.34  2510.5
#Mann= 7 , 0 ,-1
       0     .09       0  145.62     .05       0 349.501     .09       0
 387.813     .04       0 412.376     .09       0 426.879     .05       0
  776.51     .09       0
#XS Ineff= 2 , 0
       0  264.39    2520  557.83       0    2520
Permanent Ineff=
       F       F
#Block Obstruct= 1 ,-1
  630.49  659.522505.831
Bank Sta=387.813,412.376
Exp/Cntr=0.5,0.3

Type RM Length L Ch R = 1 ,25514.9 ,47.69,48,45.6
BEGIN DESCRIPTION:
u/s of 16480 surveyed section
END DESCRIPTION:
XS GIS Cut Line= 6
 1070286.5261687  837928.3074469 1070271.0990854  838219.7970304
 1070273.4949187   838273.494947 1070269.9115854  838279.8178637
 1070275.7970021  838304.2032804 1070295.2761688  838684.9324472
#Sta/Elev= 30
       0 2515.93   20.93 2510.06   40.32 2503.93   62.63 2493.67  109.44 2492.83
  262.93  2493.1 270.698  2492.2 283.324  2491.8 303.785  2489.6 308.348  2488.9
 311.086  2487.8 312.684  2486.2 318.464  2485.1   328.2  2484.2 330.177  2484.2
 334.513  2485.9 335.426    2487 337.175  2487.8     339  2489.5 342.575    2491
 354.213    2492  431.38 2491.76   480.9 2494.09  522.88 2495.36  635.35 2495.41
  666.78 2497.75  688.77 2498.76  732.88 2503.41  739.53 2504.25   760.6 2508.38
#Mann= 7 ,-1 , 0
       0     .09       0  109.44     .05       0 270.698     .09       0
 312.684     .04       0 334.513     .09       0 354.213     .05       0
  666.78     .09       0
#XS Ineff= 3 ,-1
       0  298.49  2492.5  342.58  427.96  2492.5     428   760.6    2505
Permanent Ineff=
       F       F       F
#Block Obstruct= 1 ,-1
  543.92   587.52505.525
Bank Sta=312.684,334.513
Exp/Cntr=0.5,0.3

Type RM Length L Ch R = 3 ,25492.9 ,,,
BEGIN DESCRIPTION:
fbstr 6692
END DESCRIPTION:
Bridge Culvert--1,0,-1,-1, 0
Deck Dist Width WeirC Skew NumUp NumDn MinLoCord MaxHiCord MaxSubmerge Is_Ogee
12.4,30,2.6,0, 130, 128, , , 0.95, 0, 1,1,,
       0     2.3   10.28   17.35   22.48   25.46   36.91   45.87   75.88   78.76
   83.86   88.48   98.24   99.98   105.2  120.74  123.38  133.85  138.19  148.89
  150.16   159.4  162.12  165.74  169.79  172.83  178.68  184.23  189.27  197.65
   199.5  201.97  206.02  209.06   213.6  216.35   220.3  221.89  229.87  231.08
  237.32  240.95  246.88  249.64  253.58  256.34  258.28  267.72  271.67  280.34
  280.61  282.95  290.28  295.28  301.49  302.36   303.8   303.8  339.37  339.37
  367.69   368.4  377.85   378.3  379.34  380.05  386.97  395.08   401.6  406.99
  408.14  416.28  423.12  427.77  432.35  437.89  439.17  449.56  450.39  450.53
  450.84   465.2  469.02  472.84  475.68  478.69  487.94  490.78  497.35  504.45
  508.85  517.52  524.33  535.49  550.71  552.12  554.08   557.3  571.39  595.38
  609.89   617.7  621.44  622.98  624.72  637.49  641.65   642.8  654.77  659.35
  662.61  669.71   675.1  676.26     682     685  690.81  695.69  698.97  706.73
  710.82  720.41  729.71  735.51  738.49  739.37   740.1  756.04   763.7   763.9
 2513.56 2512.97 2510.72 2509.27 2508.31 2508.34 2506.05 2504.47 2495.43 2495.06
 2494.41 2493.88 2493.54  2493.5 2493.35  2492.9 2492.88 2492.78 2492.67 2492.68
 2492.72 2492.87 2492.85 2492.88 2492.92 2492.93 2492.93 2492.96 2492.95 2492.79
 2492.74 2492.75  2492.8 2492.74 2492.72 2492.69  2492.7 2492.71 2492.79 2492.83
 2492.85  2492.8 2492.89  2492.9 2492.94 2492.93 2492.96 2493.14 2493.41 2493.71
 2493.72 2493.75 2493.71 2493.33 2493.63 2493.59  2492.5  2492.5  2492.5  2492.5
 2491.93 2492.02 2492.05 2492.05 2492.06 2492.07 2492.12 2491.98 2491.72 2491.51
  2491.5  2491.3 2491.38 2491.39 2491.47  2491.8 2491.84 2492.63 2492.68 2492.69
  2492.7 2492.88 2493.33 2493.53 2493.65  2493.8 2494.38 2494.52 2494.66 2494.44
 2494.56 2494.55 2494.74 2494.87 2494.85 2494.86 2494.85 2494.89 2494.89 2494.91
 2494.95 2494.82 2494.79 2494.78 2494.78 2495.13 2495.21 2495.26 2495.78 2495.88
 2495.96  2496.5 2496.87 2496.89 2496.96 2497.15 2497.45 2497.84 2497.87 2498.92
 2499.31 2499.99  2501.4 2502.22  2502.6 2502.71 2502.78 2505.26 2506.33 2506.37
                                                                                
                                                                                
                                                                                
                                                                                
                                                                                
                                                          2491.5  2491.5
                                                                                
                                                                                
                                                                                
                                                                                
                                                                                
                                                                                
                                                                                
       0     2.3   10.28   17.35   22.48   25.46   36.91   45.87   75.88   78.76
   83.86   88.48   98.24   99.98   105.2  120.74  123.38  133.85  138.19  148.89
  150.16   159.4  162.12  165.74  169.79  172.83  178.68  184.23  189.27  197.65
   199.5  201.97  206.02  209.06   213.6  216.35   220.3  221.89  229.87  231.08
  237.32  240.95  246.88  249.64  253.58  256.34  258.28  267.72  271.67  280.34
  280.61  282.95  290.28  295.28  301.49  302.36  340.32  340.32  374.52  374.52
  377.85   378.3  379.34  380.05  386.97  395.08   401.6  406.99  408.14  416.28
  423.12  427.77  432.35  437.89  439.17  449.56  450.39  450.53  450.84   465.2
  469.02  472.84  475.68  478.69  487.94  490.78  497.35  504.45  508.85  517.52
  524.33  535.49  550.71  552.12  554.08   557.3  571.39  595.38  609.89   617.7
  621.44  622.98  624.72  637.49  641.65   642.8  654.77  659.35  662.61  669.71
   675.1  676.26     682     685  690.81  695.69  698.97  706.73  710.82  720.41
  729.71  735.51  738.49  739.37   740.1  756.04   763.7   763.9
 2513.56 2512.97 2510.72 2509.27 2508.31 2508.34 2506.05 2504.47 2495.43 2495.06
 2494.41 2493.88 2493.54  2493.5 2493.35  2492.9 2492.88 2492.78 2492.67 2492.68
 2492.72 2492.87 2492.85 2492.88 2492.92 2492.93 2492.93 2492.96 2492.95 2492.79
 2492.74 2492.75  2492.8 2492.74 2492.72 2492.69  2492.7 2492.71 2492.79 2492.83
 2492.85  2492.8 2492.89  2492.9 2492.94 2492.93 2492.96 2493.14 2493.41 2493.71
 2493.72 2493.75 2493.71 2493.33 2493.63 2493.59  2492.5  2491.5  2491.5  2492.5
 2492.05 2492.05 2492.06 2492.07 2492.12 2491.98 2491.72 2491.51  2491.5  2491.3
 2491.38 2491.39 2491.47  2491.8 2491.84 2492.63 2492.68 2492.69  2492.7 2492.88
 2493.33 2493.53 2493.65  2493.8 2494.38 2494.52 2494.66 2494.44 2494.56 2494.55
 2494.74 2494.87 2494.85 2494.86 2494.85 2494.89 2494.89 2494.91 2494.95 2494.82
 2494.79 2494.78 2494.78 2495.13 2495.21 2495.26 2495.78 2495.88 2495.96  2496.5
 2496.87 2496.89 2496.96 2497.15 2497.45 2497.84 2497.87 2498.92 2499.31 2499.99
  2501.4 2502.22  2502.6 2502.71 2502.78 2505.26 2506.33 2506.37
                                                                                
                                                                                
                                                                                
                                                                                
                                                                                
                                                          2490.5  2490.5
                                                                                
                                                                                
                                                                                
                                                                                
                                                                                
                                                                                
                                                                
BR Coef=-1 , 0 , 0 ,, 0 ,,,0.8,0,,0,
WSPro=,,,, 1 ,,,, 0 ,,,, 0 ,,,,-1 ,-1 ,-1 , 0 , 0 , 0 , 0 , 0
BC Design=,, 0 ,, 0 ,,,,,,

Type RM Length L Ch R = 1 ,25466.9 ,44.56,43,47.47
BEGIN DESCRIPTION:
d/s of 16480 surveyed section
END DESCRIPTION:
XS GIS Cut Line= 6
 1070226.0053354  837905.8282802 1070222.7970021  838211.7032803
 1070224.5990854   838251.994947 1070229.5990854   838279.401197
 1070228.9011687  838323.2032804 1070240.6511687  838686.3074472
#Sta/Elev= 30
       0 2507.57    8.34 2505.81   31.14 2505.59   75.19 2498.29  106.38 2496.26
  129.66 2493.37   152.2 2492.43  268.85 2492.35  285.39 2491.51 286.479  2490.6
 321.176  2490.4 336.883  2485.8 338.367  2485.2 345.166  2485.4 351.418    2484
 360.561  2483.7 372.829  2485.7 374.314  2486.4 378.299  2490.8 382.207  2490.9
 418.153  2489.9 457.695    2490   472.5 2491.18  478.38 2492.51  506.27  2493.8
   675.1 2494.57  706.08 2495.89  724.43 2497.36  747.24 2499.41  781.45 2503.76
#Mann= 6 ,-1 , 0
       0     .09       0  106.38     .05       0  268.85     .09       0
 336.883    .048       0 372.829     .09       0 382.207     .05       0
#XS Ineff= 3 ,-1
       0     330    2490   378.2     485    2490     495  781.45    2495
Permanent Ineff=
       F       F       F
Bank Sta=336.883,372.829
Exp/Cntr=0.5,0.3

Type RM Length L Ch R = 1 ,25423.9 ,214.84,216,217.97
BEGIN DESCRIPTION:
surveyed section
END DESCRIPTION:
XS GIS Cut Line= 6
 1070187.9740854  837879.9011969 1070182.9949187   838194.401197
 1070179.9011687   838246.901197 1070182.9011687  838272.5991137
 1070180.4011687  838293.9011971 1070217.4636687  838693.7345306
#Sta/Elev= 30
       0 2505.79   50.18 2505.33   68.36 2504.85   80.95 2503.31   98.84 2503.29
  116.26 2500.29  128.97 2499.09  155.72 2493.44   166.1 2492.39  196.17 2491.87
  286.83 2492.36   297.4  2491.8  314.56  2490.3 354.972  2489.5 373.341  2485.8
 393.098    2485 403.956  2485.7 405.752  2486.1 407.548    2488 408.691  2490.4
 442.327  2488.5  488.96    2489  497.52 2490.19  507.99 2493.34  517.87 2492.39
  601.37 2494.02  707.24    2494  741.91 2495.55  770.06  2497.9   816.4  2503.2
#Mann= 5 ,-1 , 0
       0     .05       0   297.4     .09       0 373.341     .04       0
 403.956     .09       0 408.691     .05       0
#XS Ineff= 2 , 0
       0                     490       0 2496.74
Permanent Ineff=
       F       F
#Block Obstruct= 1 ,-1
   34.92   97.682515.055
Bank Sta=373.341,403.956
Exp/Cntr=0.3,0.1

Type RM Length L Ch R = 1 ,25207.9 ,311.56,314,317
XS GIS Cut Line= 4
 1069957.4740853  837667.7761968 1069971.2865853  838254.5053637
 1069973.5782519  838500.7032805 1070005.7970019  838880.3595307
#Sta/Elev= 30
       0 2513.23   18.16 2507.34    34.3 2499.58    45.1 2496.91   52.84 2496.01
   76.59 2493.55  108.35 2493.41  120.15  2489.7  254.21 2489.25  355.39 2490.03
  442.55    2489  483.55 2489.77  507.65 2488.53  546.84 2483.74  566.06 2483.07
  569.18 2483.77  589.34 2488.11  638.12 2488.91  687.71 2488.59  729.39 2486.77
  747.78 2489.41   778.8 2490.13  815.42 2489.68  851.55 2490.84  892.27 2490.81
  983.07 2492.61 1072.47 2497.68 1117.55 2501.18 1160.86 2505.64 1214.12 2512.91
#Mann= 6 ,-1 , 0
       0     .09       0   52.84     .05       0  507.65     .09       0
  546.84     .04       0  569.18     .09       0  638.12     .05       0
Bank Sta=546.84,569.18
Exp/Cntr=0.3,0.1

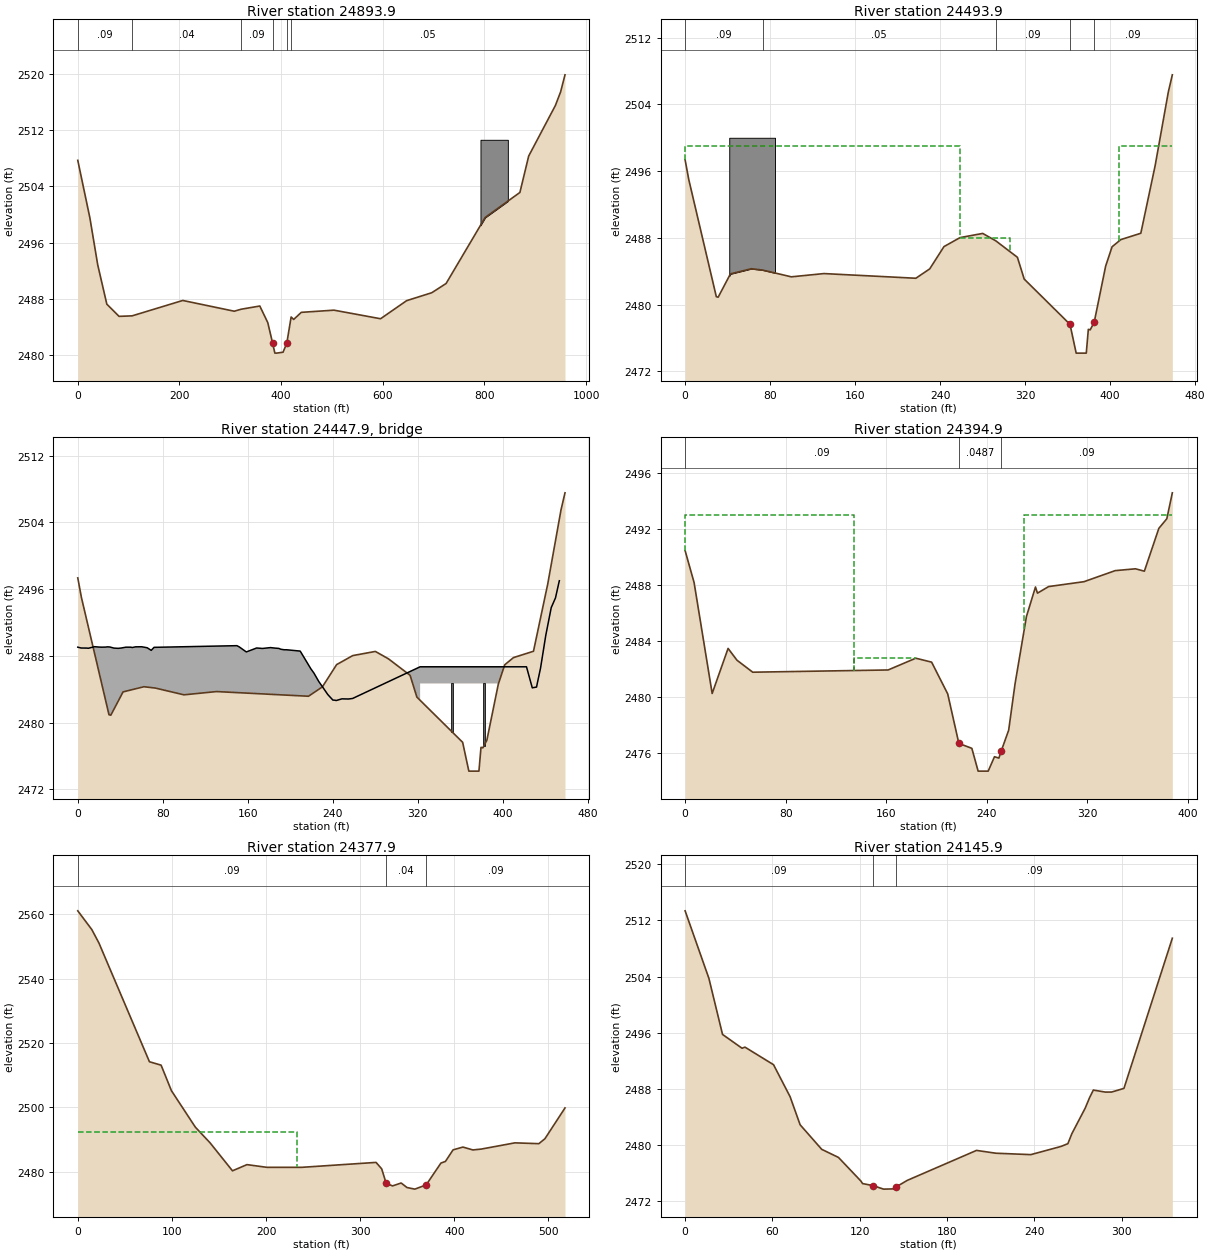
Type RM Length L Ch R = 1 ,24893.9 ,367.27,399.7,431.27
XS GIS Cut Line= 5
 1069706.0938996  837753.0835546  1069703.239733  837816.2502213
 1069665.2605663  838160.1668883 1069596.2293162  838408.6668886
 1069518.0001495  838689.3752222
#Sta/Elev= 30
       0 2507.69   23.87 2499.49   39.21 2492.84   57.17 2487.23   81.25  2485.5
  106.85 2485.57  206.57 2487.76  307.91 2486.23  321.13 2486.51  358.12 2486.97
  373.86  2484.6  383.33 2481.69  387.73 2480.28  390.89 2480.27  403.85  2480.4
  411.23 2481.68  419.77 2485.41  424.78 2485.06  439.77 2486.07  504.06 2486.38
   595.7 2485.16  646.94 2487.73  696.45 2488.86  724.62 2490.17  801.35 2499.55
  869.83 2503.12  887.12  2508.3  939.64 2515.49  949.91 2517.42  958.55 2519.85
#Mann= 6 ,-1 , 0
       0     .09       0  106.85     .04       0  321.13     .09       0
  383.33     .04       0  411.23     .09       0  419.77     .05       0
#Block Obstruct= 1 ,-1
  792.27  846.112510.611
Bank Sta=383.33,411.23
Exp/Cntr=0.5,0.3

Type RM Length L Ch R = 1 ,24493.9 ,98.65,99,96.61
BEGIN DESCRIPTION:
U/S OF 15435
END DESCRIPTION:
XS GIS Cut Line= 5
  1069503.755335  837771.2136968 1069475.3386684  837898.3699469
 1069430.7032517  838002.5470302 1069371.1720017  838020.1303636
 1069218.3074182  838020.1303636
#Sta/Elev= 30
       0 2497.35    3.44    2495   29.37 2480.96   31.11  2480.9   42.63 2483.69
   62.26 2484.31   73.03 2484.15   99.93 2483.34  130.63 2483.73  217.17 2483.17
  230.21 2484.29  243.62 2486.96  258.78 2488.04   280.1 2488.54  292.46 2487.65
  312.76 2485.68  319.16 2483.07  362.25 2477.65  368.07  2474.2  377.57  2474.2
  379.51 2477.05  381.27 2476.99  385.03  2477.9  395.82 2484.63  401.85 2486.94
  410.08  2487.8  428.91 2488.56  442.33 2496.62  454.81 2505.49  458.57 2507.54
#Mann= 5 ,-1 , 0
       0     .09       0   73.03     .05       0  292.46     .09       0
  362.25     .04       0  385.03     .09       0
#XS Ineff= 3 ,-1
       0  258.78    2499     259   305.7    2488  408.25  458.57    2499
Permanent Ineff=
       F       F       F
#Block Obstruct= 1 ,-1
   41.53   84.61    2500
Bank Sta=362.25,385.03
Exp/Cntr=0.5,0.3

Type RM Length L Ch R = 3 ,24447.9 ,,,
BEGIN DESCRIPTION:
FBSTR 1362
END DESCRIPTION:
Bridge Culvert--1,0,-1,-1, 0
Deck Dist Width WeirC Skew NumUp NumDn MinLoCord MaxHiCord MaxSubmerge Is_Ogee
29.2,66,2.6,0, 68, 60, , , 0.95, 0, 1,1,,
       0    3.13    8.24   10.05   10.63   15.82   19.37   20.71    22.3   26.02
   28.04   30.28      34    38.1   41.01   43.58   45.32   49.78   51.32   54.29
   60.16   65.32   69.11   71.26   71.75  149.78  152.01  158.61  167.49  168.07
   168.4  171.58  173.42   173.9  174.19  181.39   185.5  189.27  191.19  194.26
  196.47  207.81  209.02  209.35  209.83  219.31  222.35  226.86  229.68  235.33
  240.12  241.66   243.3  248.65   254.6  255.27  258.59  322.22  322.22  422.32
  422.32  427.77  431.76  435.56   440.5  445.61  449.61  453.24
 2489.05 2488.95 2488.94 2488.92 2488.94 2489.11 2489.07 2489.06 2489.05 2489.06
 2489.09 2489.07 2488.94 2488.91 2488.95 2489.01 2489.05 2489.05 2489.01 2489.09
  2489.1 2488.98 2488.67 2488.96 2489.03 2489.23 2489.08 2488.48 2488.91 2488.95
 2488.95 2488.92  2488.9  2488.9  2488.9    2489 2488.94  2488.9  2488.8 2488.74
 2488.74  2488.6 2488.59 2488.57 2488.48 2486.47 2485.93 2484.93 2484.42 2483.37
 2482.71  2482.7 2482.66 2482.86 2482.84 2482.85  2482.9  2486.7  2486.7  2486.7
  2486.7 2484.18 2484.27 2486.55 2490.48 2493.79 2494.95 2497.01
                                                                                
                                                                                
                                                                                
                                                                                
                                                                                
                                                                  2484.7  2484.7
                                                                
       0    3.13    8.24   10.05   10.63   15.82   19.37   20.71    22.3   26.02
   28.04   30.28      34    38.1   41.01   43.58   45.32   49.78   51.32   54.29
   60.16   65.32   69.11   71.26   71.75  149.78  152.01  158.61  167.49  168.07
   168.4  171.58  173.42   173.9  174.19  181.39   185.5  187.02  187.02  287.12
  287.12  366.08   369.5  373.77  381.89  385.33  390.21  399.77  406.86  410.31
  411.86   416.8  417.12  427.77  431.76  435.56   440.5  445.61  449.61  453.24
 2489.05 2488.95 2488.94 2488.92 2488.94 2489.11 2489.07 2489.06 2489.05 2489.06
 2489.09 2489.07 2488.94 2488.91 2488.95 2489.01 2489.05 2489.05 2489.01 2489.09
  2489.1 2488.98 2488.67 2488.96 2489.03 2489.23 2489.08 2488.48 2488.91 2488.95
 2488.95 2488.92  2488.9  2488.9  2488.9    2489 2488.94  2486.2  2486.2  2486.2
  2486.2  2482.8 2482.86 2482.86 2482.79 2482.85    2483 2483.05 2482.88 2482.88
 2482.83 2482.14 2482.18 2484.18 2484.27 2486.55 2490.48 2493.79 2494.95 2497.01
                                                                                
                                                                                
                                                                                
                                                                  2484.2  2484.2
                                                                                
                                                                                
Pier Skew, UpSta & Num, DnSta & Num=  ,352.22, 2 ,217.02, 2 , 0 , 0 , 0 ,,
       2       2
  2474.2  2484.7
       2       2
  2474.7  2485.2
Pier Skew, UpSta & Num, DnSta & Num=  ,382.22, 2 ,247.02, 2 , 0 , 0 , 0 ,,
       2       2
  2474.2  2484.7
       2       2
  2474.7  2485.2
BR Coef=-1 , 0 , 0 ,, 0 ,,,0.8,0,,1,
WSPro=,,,, 1 ,,,, 0 ,,,, 0 ,,,,-1 ,-1 ,-1 , 0 , 0 , 0 , 0 , 0
BR D #Sta/Elev= 82
       0 2490.46    7.14 2488.18   16.18 2483.28   20.06 2480.92   21.52 2480.25
   23.82 2480.96   34.18 2483.47   41.21 2482.63   48.63 2482.14   53.76 2481.77
   64.64 2481.78   71.85 2481.72   74.88 2481.69   76.18 2481.69   78.45 2481.76
   85.14 2481.86   91.83 2481.73   96.76 2481.73  105.62 2481.78     109 2481.81
   115.5 2481.76   121.1 2481.76   121.4 2481.77  129.55  2481.8  134.52 2481.81
  140.91 2481.79   147.9 2481.92  152.39 2481.99  161.46 2481.93  163.85 2482.02
  174.95  2482.4  175.41 2482.42  178.24 2482.58   178.5 2482.59  183.44 2482.77
  196.04 2482.49  208.85 2480.22  217.72 2476.68  221.33  2476.6  227.79 2476.35
  228.04 2476.33  233.04  2474.7  241.04  2474.7  246.06 2475.73  246.95 2475.71
  249.54 2475.63  250.75 2475.88  251.54 2476.17  257.34 2477.63  262.37 2480.92
   270.8 2485.41  271.46 2485.75  272.02 2485.87  278.65 2487.86  280.23 2487.42
  289.11 2487.89  291.59 2487.89  293.81 2487.91  298.79 2488.06  305.64  2488.2
  310.95 2488.13  312.44 2488.15  317.24 2488.24  320.04 2488.34  325.41 2488.56
  326.79 2488.56  328.77 2488.61  334.02 2488.67  336.22 2488.76  340.84 2488.98
  342.07 2489.03  348.23 2489.05  348.75 2489.06  355.03 2489.09  356.81 2489.15
  358.18 2489.16  365.25 2488.99  376.76 2492.05  382.17 2492.68  383.12 2492.74
  384.61 2493.32  387.49 2494.59
BR D #Mann= 3
       0     .09  217.72    .052  251.54     .09
BC Design=,, 0 ,, 0 ,,,,,,

Type RM Length L Ch R = 1 ,24394.9 ,16.9,17,17.03
BEGIN DESCRIPTION:
D/S OF 15435
END DESCRIPTION:
XS GIS Cut Line= 4
 1069437.4636684  837763.0886968 1069407.7032517  837880.7866135
  1069373.880335  837926.7866135 1069164.9324182  837922.3178635
#Sta/Elev= 30
       0 2490.46    7.14 2488.18   21.52 2480.25   34.18 2483.47   41.21 2482.63
   53.76 2481.77  161.46 2481.93  183.44 2482.77  196.04 2482.49  208.85 2480.22
  217.72 2476.68  228.04 2476.33  233.04  2474.7  241.04  2474.7  246.06 2475.73
  249.54 2475.63  251.54 2476.17  257.34 2477.63  262.37 2480.92  271.46 2485.75
  278.65 2487.86  280.23 2487.42  289.11 2487.89  317.24 2488.24  342.07 2489.03
  358.18 2489.16  365.25 2488.99  376.76 2492.05  383.12 2492.74  387.49 2494.59
#Mann= 3 ,-1 , 0
       0     .09       0  217.72   .0487       0  251.54     .09       0
#XS Ineff= 3 ,-1
       0     134    2493   134.5  183.44  2482.8  269.83  387.49    2493
Permanent Ineff=
       F       F       F
Bank Sta=217.72,251.54
Exp/Cntr=0.5,0.3

Type RM Length L Ch R = 1 ,24377.9 ,246.07,232,221.24
XS GIS Cut Line= 6
 1069445.5782517  837622.4011967 1069373.2032517  837899.0991135
 1069326.7970016  837910.4949469 1069291.4949183  837908.4011969
 1069276.0990849  837911.5991135 1069144.6303349  837912.1720302
#Sta/Elev= 30
       0 2561.03   14.89 2555.22   22.45 2551.06   76.14 2514.16   88.52  2513.1
    99.5 2505.17  124.92 2493.84  140.65 2488.94  164.34 2480.29  179.76 2482.21
  200.84 2481.37   238.1 2481.37 316.867  2482.9 322.871  2480.9 327.632  2476.4
 334.413  2475.6 343.522  2476.5 349.733  2475.1 358.015  2474.6 370.074  2475.9
 385.809  2482.7 390.571  2483.2 398.697  2486.8  409.18 2487.66  419.78 2486.77
  428.69 2487.04  464.37 2488.97  489.81 2488.72  496.26 2490.25  517.59 2499.81
#Mann= 3 ,-1 , 0
       0     .09       0 327.632     .04       0 370.074     .09       0
#XS Ineff= 2 , 0
       0  233.02 2492.44               0
Permanent Ineff=
       F       F
Bank Sta=327.632,370.074
Exp/Cntr=0.3,0.1

Type RM Length L Ch R = 1 ,24145.9 ,323.95,307,297.27
XS GIS Cut Line= 5
 1069290.7345016  837638.5886967 1069209.0678349  837706.5574468
 1069169.5990849  837746.0261968 1069112.0470015  837823.3074468
 1069073.1303348  837889.0886969
#Sta/Elev= 30
       0 2513.37   16.35 2503.76   25.71 2495.78   39.14 2493.81   41.13 2493.97
   60.77 2491.47   72.15 2486.92   79.05 2482.92   93.91 2479.42  105.41 2478.27
  120.82 2474.91  121.97 2474.55  129.02 2474.27  136.42 2473.76  142.64 2473.79
  145.26  2474.1  152.63    2475  200.25 2479.27  213.64 2478.87   237.6 2478.67
  258.42 2479.84  263.07 2480.23  265.83 2481.66  274.98 2485.29  277.96 2486.77
  280.58 2487.86  288.84 2487.57  293.21 2487.58  301.61  2488.1  334.86 2509.47
#Mann= 3 ,-1 , 0
       0     .09       0  129.02     .04       0  145.26     .09       0
Bank Sta=129.02,145.26
Exp/Cntr=0.3,0.1