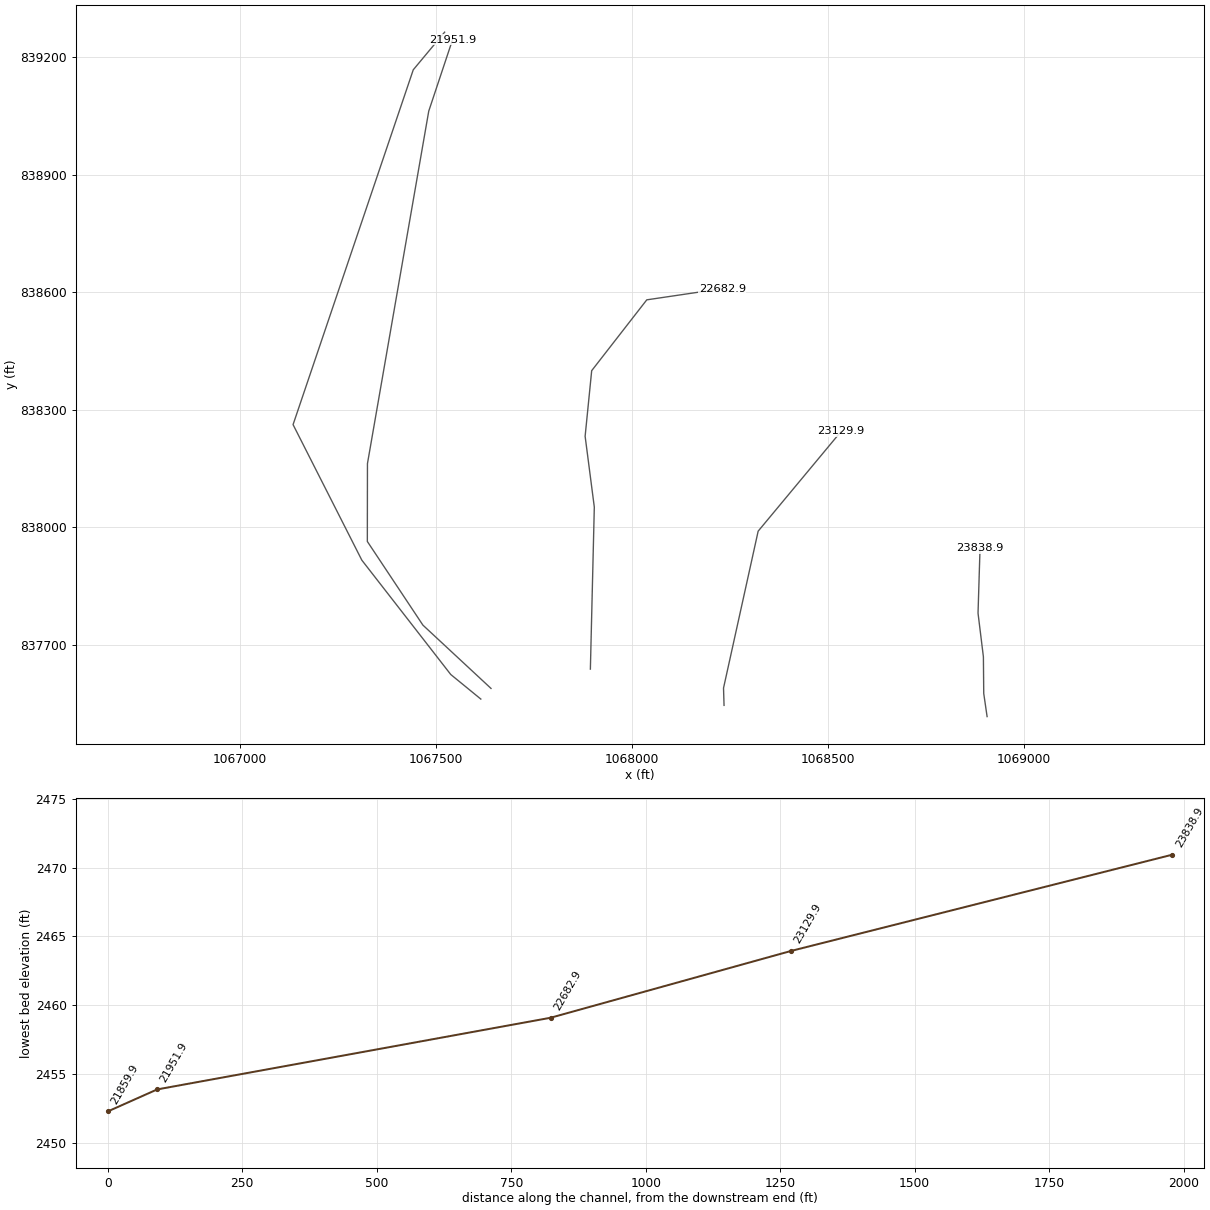
HEC-RAS study dtl_cane_crk.prj: cane creek

--- dtl_cane_crk.g01 (geometry) --- (continued)

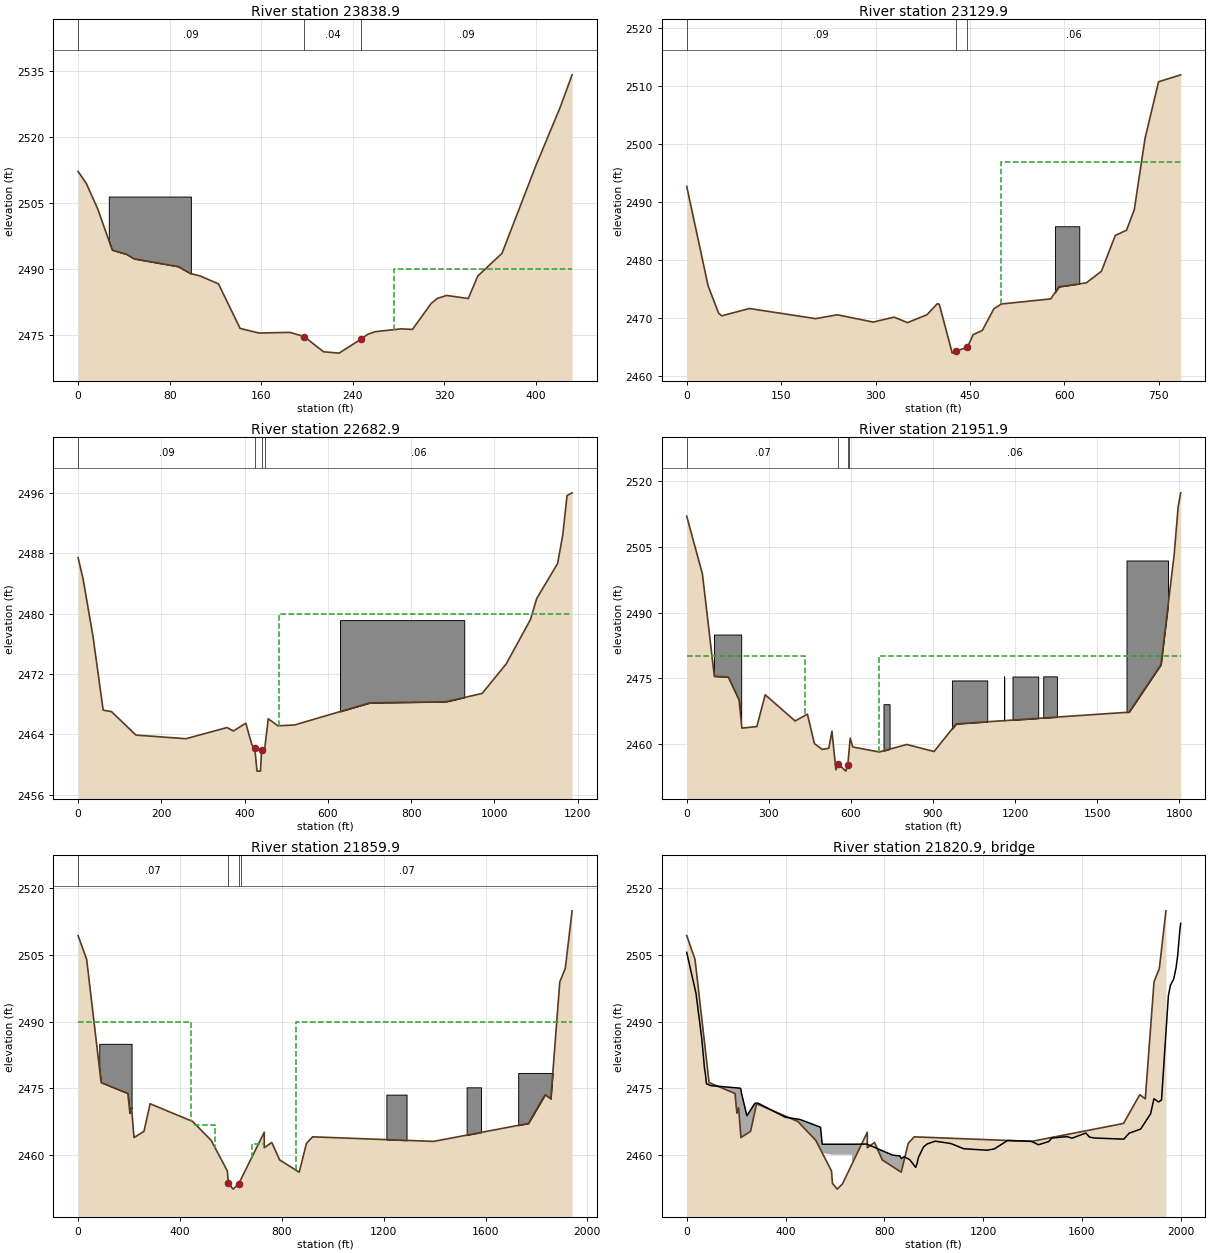
Type RM Length L Ch R = 1 ,23838.9 ,721.43,709,709.35
XS GIS Cut Line= 5
 1068906.5053348    837517.57828 1068897.9324181  837576.6720301
 1068897.0782514  837670.0261968 1068883.3803348  837781.3595301
 1068888.5157514  837947.5157802
#Sta/Elev= 30
       0 2512.16    7.21 2509.42   17.28 2503.57   29.84 2494.31   42.25 2493.37
   48.92 2492.34   87.36 2490.58      98 2489.02  106.39 2488.47  122.62 2486.65
  141.49 2476.55  158.02  2475.5  185.08 2475.65  197.48 2474.68  214.34 2471.25
  227.96 2470.94  247.28 2474.13  252.81 2475.19  259.41  2475.8  282.15 2476.45
  292.03 2476.32  308.41 2482.22  313.93 2483.37  321.84 2484.03  340.76 2483.33
  349.09 2488.44  370.25 2493.59  399.48 2513.25  421.06 2526.72  431.48 2534.09
#Mann= 3 , 0 , 0
       0     .09       0  197.48     .04       0  247.28     .09       0
#XS Ineff= 2 , 0
       0                  275.72       0    2490
Permanent Ineff=
       F       F
#Block Obstruct= 1 ,-1
   26.78   98.492506.468
Bank Sta=197.48,247.28
Exp/Cntr=0.3,0.1

Type RM Length L Ch R = 1 ,23129.9 ,441.02,447,448.72
XS GIS Cut Line= 5
 1068235.6303345  837546.1824467 1068234.2970011  837590.3491134
 1068305.2240845  837911.5157802 1068322.6199178  837990.4741136
 1068534.0574179  838244.7345304
#Sta/Elev= 30
       0 2492.73   33.95 2475.58   50.73 2470.83   55.65 2470.39    99.5 2471.65
  204.92  2469.9  239.12 2470.57   296.2 2469.31  329.47 2470.16  350.68 2469.21
  381.66 2470.58  398.16 2472.49  401.19 2472.37  421.75 2463.95  427.23 2464.29
  445.91 2464.96  454.84 2467.13  469.59 2467.88  487.83  2471.6  499.77 2472.43
  578.22 2473.31  591.13  2475.4  634.67 2476.08  658.61 2478.07  680.72 2484.26
  698.53 2485.16  710.88  2488.7  727.99 2501.03  749.45 2510.78  784.63 2511.98
#Mann= 3 ,-1 , 0
       0     .09       0  427.23     .04       0  445.91     .06       0
#XS Ineff= 2 , 0
       0                  498.52       0    2497
Permanent Ineff=
       F       F
#Block Obstruct= 1 ,-1
  584.86  623.522485.845
Bank Sta=427.23,445.91
Exp/Cntr=0.3,0.1

Type RM Length L Ch R = 1 ,22682.9 ,733.95,731,722.1
XS GIS Cut Line= 6
 1067894.7240843  837638.6928634  1067904.765751  838051.8595303
 1067881.3386676  838232.5157804 1067898.0678343  838399.7970304
  1068038.578251  838580.4532805 1068230.9532511  838608.8907805
#Sta/Elev= 30
       0 2487.41   11.94 2484.59   35.74 2476.98    60.2 2467.19   80.31 2466.99
  138.84 2463.88  259.08  2463.4  357.86 2464.88  373.22 2464.43  402.89 2465.46
  417.45 2462.61  424.46  2462.2   429.8  2459.1  438.27  2459.1  440.72 2461.89
   446.9 2461.53  449.15 2462.48  456.91 2466.04  480.02 2465.11  519.92 2465.22
  700.71 2468.15  883.84  2468.3  970.82 2469.41 1028.49 2473.31 1086.97 2479.21
 1101.91 2481.99 1152.06 2486.63 1164.43 2490.38 1174.82 2495.65 1186.96 2496.01
#Mann= 4 ,-1 , 0
       0     .09       0  424.46     .04       0  440.72     .09       0
  449.15     .06       0
#XS Ineff= 2 , 0
       0                  483.23       0    2480
Permanent Ineff=
       F       F
#Block Obstruct= 1 ,-1
  629.26  927.792479.124
Bank Sta=424.46,440.72
Exp/Cntr=0.3,0.1

Type RM Length L Ch R = 1 ,21951.9 ,76.33,92,110.71
BEGIN DESCRIPTION:
surveyed section
END DESCRIPTION:
XS GIS Cut Line= 6
 1067641.3178342  837589.4116134 1067467.6303341  837750.8491135
 1067325.9011674  837964.2032802 1067326.2032507  838162.7970303
 1067482.5470008  839061.8595307 1067543.0574175  839243.3907808
#Sta/Elev= 30
       0 2511.93   57.41 2498.78  100.97 2475.49   151.8 2475.32  191.37 2470.06
  201.67 2463.69  256.24 2464.05  286.79 2471.28  396.22 2465.32  440.92 2466.87
  466.51 2460.17  495.08 2458.83 519.123  2459.1 530.675    2463 544.934  2454.2
 553.057  2455.6 581.035  2453.9 588.435  2455.2 593.128  2458.5  597.46  2461.4
 606.666  2459.4  703.47 2458.26  804.49 2459.97  903.67 2458.36   984.4 2464.65
 1616.07 2467.32 1732.89 2478.15  1781.1 2503.21  1795.8 2514.14 1805.02 2517.26
#Mann= 4 ,-1 , 0
       0     .07       0 553.057     .04       0 588.435     .09       0
 593.128     .06       0
#XS Ineff= 2 , 0
       0  433.94    2480     702       0    2480
Permanent Ineff=
       F       F
#Block Obstruct= 7 ,-1
  718.98  741.212469.139  969.03 1098.082474.545  1159.3 1160.282475.483
 1190.36 1284.272475.435 1302.62 1352.562475.476 1606.93 1758.65 2501.86
  99.745 199.075    2485
Bank Sta=553.057,588.435
Exp/Cntr=0.5,0.3

Type RM Length L Ch R = 1 ,21859.9 ,80.62,87,88.43
BEGIN DESCRIPTION:
U/S OF 12808 SURVEYED SECTION
END DESCRIPTION:
XS GIS Cut Line= 6
 1067615.3386675  837562.2553634 1067538.6720008  837624.9011967
 1067311.8907507  837916.4741135 1067136.4949173   838262.182447
 1067443.0365841  839167.1511975 1067523.0261675  839263.1199475
#Sta/Elev= 30
       0 2509.35    33.6 2504.02   90.49 2476.28  195.39 2473.82  203.26 2469.38
   209.9 2470.61   219.5 2463.91  258.66 2465.31  282.73 2471.51  449.44 2467.54
  522.27 2463.29 586.078  2456.4 589.958  2453.6  608.97  2452.3 630.892  2453.5
 638.459  2454.4 730.997  2465.1  731.03 2461.63   760.5  2462.8  791.54 2458.87
   868.3 2456.11  896.84 2462.61   921.1 2464.07 1396.07 2463.04 1768.17 2467.08
  1834.1 2473.56 1856.39 2472.62 1891.71 2498.94 1913.24 2501.98 1940.02 2514.93
#Mann= 4 ,-1 , 0
       0     .07       0 589.958     .04       0 630.892     .09       0
 638.459     .07       0
#XS Ineff= 4 ,-1
       0  442.16    2490     857 1940.02    2490  456.94     538 2466.64
     681     730  2462.4
Permanent Ineff=
       F       F       F       F
#Block Obstruct= 4 ,-1
 1210.52 1289.852473.567 1525.67 1582.272475.212 1728.27 1890.992478.451
  83.053     210    2485
Bank Sta=589.958,630.892
Exp/Cntr=0.5,0.3

Type RM Length L Ch R = 3 ,21820.9 ,,,
BEGIN DESCRIPTION:
FBSTR 1363
END DESCRIPTION:
Bridge Culvert--1,0,-1,-1, 0
Deck Dist Width WeirC Skew NumUp NumDn MinLoCord MaxHiCord MaxSubmerge Is_Ogee
39.6,45,2.6,0, 60, 60, , , 0.95, 0, 1,1,,
       0   37.69   60.97   71.92   74.93   79.79   97.77  216.19  218.92  221.87
  243.41   276.3  289.18  398.78  457.76  541.65  548.52  548.52  669.42  669.42
  728.79  833.81   862.9  868.68     880  902.82  926.78  933.37  937.26  958.04
   973.3 1005.54 1068.87 1121.48  1215.9 1245.21 1298.85 1394.21 1423.61 1465.21
 1477.75  1539.1 1559.91 1615.63 1630.84 1652.16 1769.51 1790.83 1837.58 1877.92
 1891.34 1909.56 1922.01 1949.74 1957.94  1971.3 1980.94 1987.36 1996.42 1999.77
 2505.58 2496.31 2486.15 2479.49 2478.51 2476.02 2475.59 2475.02 2474.88 2473.86
 2468.82 2471.63 2471.64 2468.49 2467.99 2466.23  2462.4  2462.4  2462.4  2462.4
 2462.44 2459.95 2459.77 2459.19  2459.6 2458.93 2457.19 2458.23 2459.33 2461.75
 2462.47 2463.09 2462.57 2461.39 2461.06 2461.35 2463.24 2463.08 2462.29    2463
 2463.79 2464.12 2463.77 2464.92 2463.99  2463.8 2463.55 2464.88 2465.82 2469.26
 2472.64 2471.92 2472.35 2495.75 2498.16 2499.55 2502.12 2504.77 2510.67 2512.12
                                                                                
                                                         2460.05 2460.05
                                                                                
                                                                                
                                                                                
                                                                                
       0   37.69   60.97   71.92   74.93   79.79   97.77  216.19  218.92  243.41
   276.3  289.18  398.78  457.76  541.65  649.41  649.41  770.31  770.31  774.67
  826.43   862.9  868.68     880  902.82  926.78  933.37  937.26  958.04 1005.54
 1068.87 1121.48  1215.9 1245.21 1298.85 1394.21 1423.61 1465.21 1477.75  1539.1
 1559.91 1615.63 1630.84 1652.16 1769.51 1790.83 1832.78 1857.79 1877.92 1891.34
 1909.56 1922.01 1949.74 1957.94  1971.3 1980.94 1987.36 1996.42 1999.77 2085.74
 2505.58 2496.31 2486.15 2479.49 2478.51 2476.02 2475.59 2475.02 2474.88 2468.82
 2471.63 2471.64 2468.49 2467.99 2466.23  2462.4  2462.4  2462.4  2462.4 2461.53
 2460.11 2459.77 2459.19  2459.6 2458.93 2457.19 2458.23 2459.33 2461.75 2463.09
 2462.57 2461.39 2461.06 2461.35 2463.24 2463.08 2462.29    2463 2463.79 2464.12
 2463.77 2464.92 2463.99  2463.8 2463.55 2464.88 2465.59 2467.33 2469.26 2472.64
 2471.92 2472.35 2495.75 2498.16 2499.55 2502.12 2504.77 2510.67 2512.12 2509.42
                                                                                
                                                 2460.05 2460.05
                                                                                
                                                                                
                                                                                
                                                                                
BR Coef=-1 , 0 , 0 ,, 0 ,,,0.8,0,,0,
WSPro=,,,, 1 ,,,, 0 ,,,, 0 ,,,,-1 ,-1 ,-1 , 0 , 0 , 0 , 0 , 0
BC Design=,, 0 ,, 0 ,,,,,,