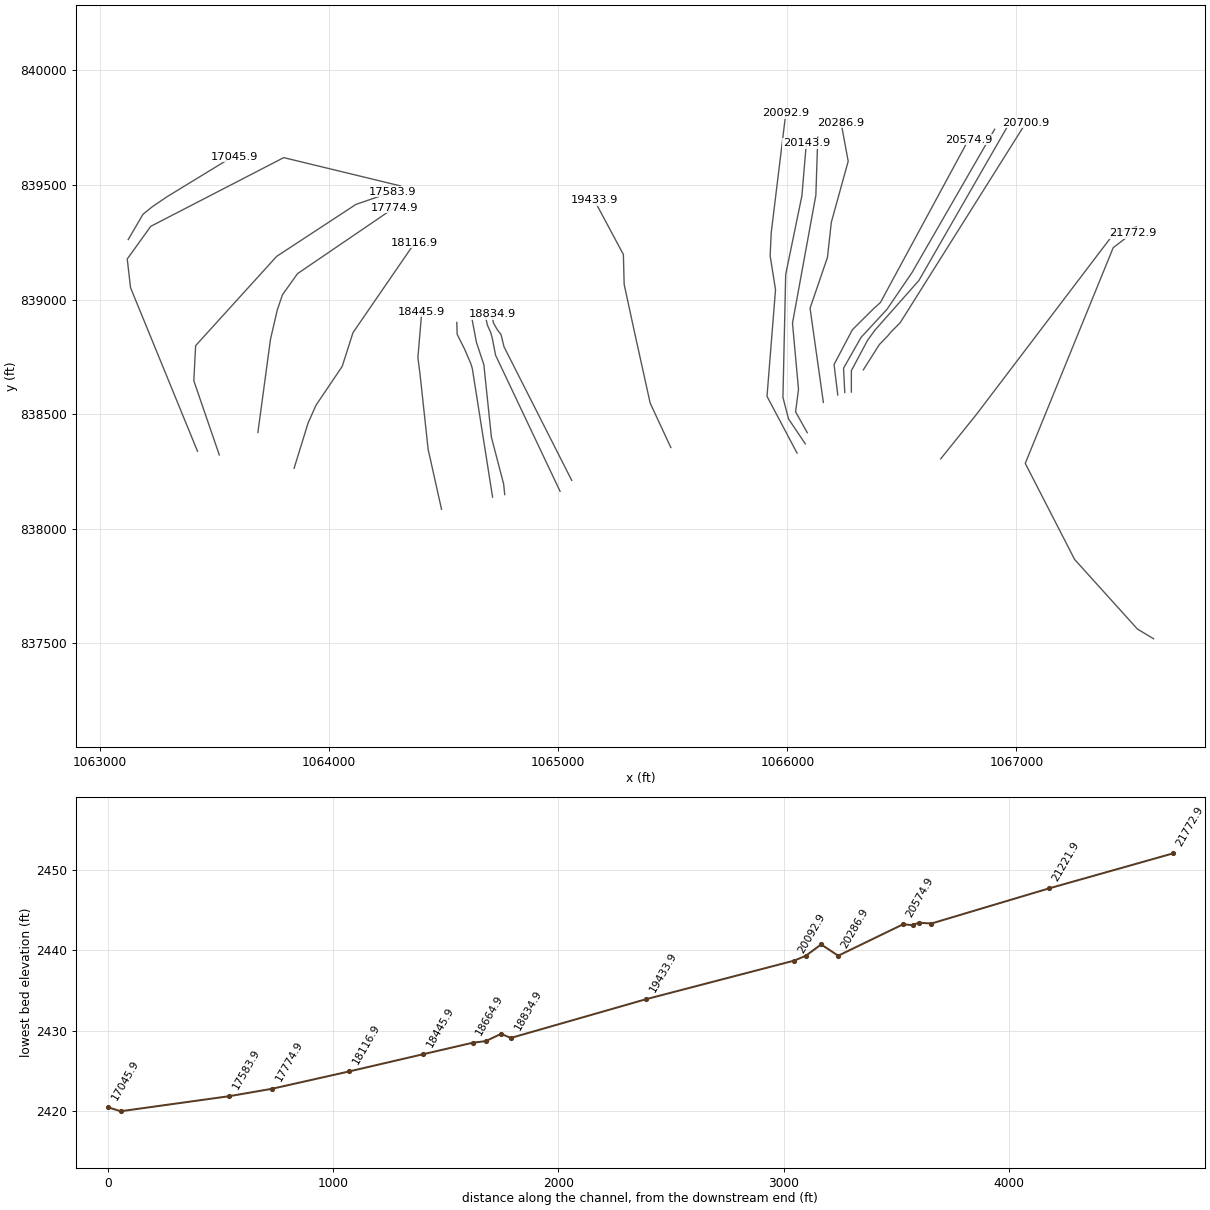
HEC-RAS study dtl_cane_crk.prj: cane creek

--- dtl_cane_crk.g01 (geometry) --- (continued)

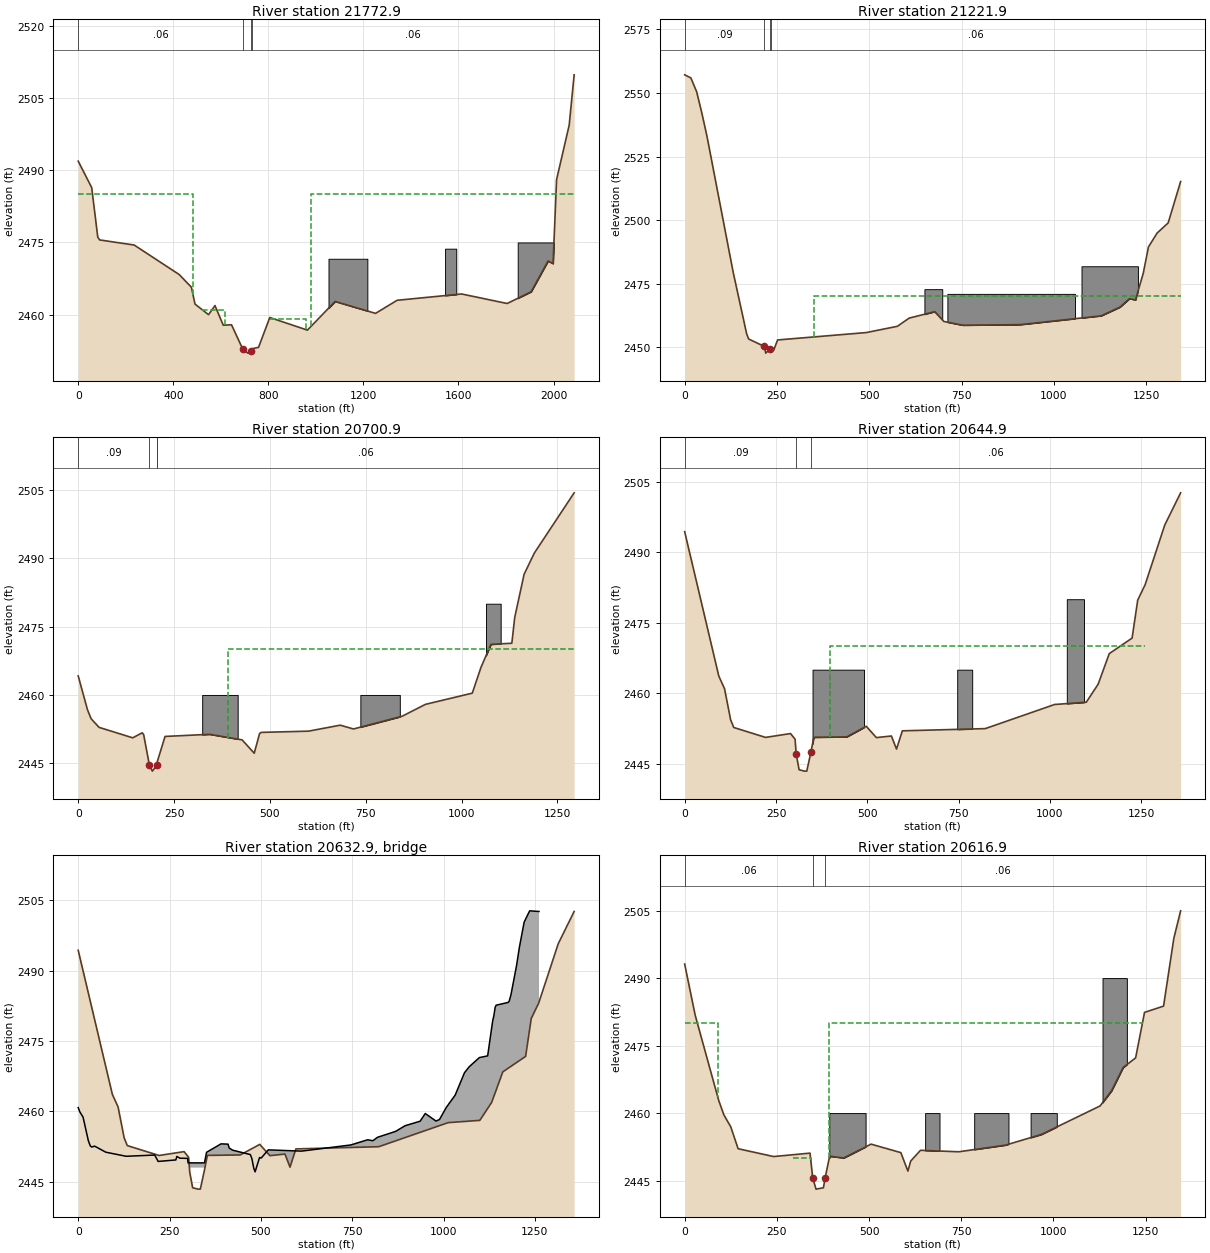
Type RM Length L Ch R = 1 ,21772.9 ,583.96,551,518.33
BEGIN DESCRIPTION:
D/S OF 12808 SURVYEYED SECTION
END DESCRIPTION:
XS GIS Cut Line= 6
 1067598.8074175  837519.7553634 1067528.5053341    837561.79703
  1067254.036584  837865.7032802 1067038.5261672   838284.932447
 1067422.4532507  839226.0053642 1067506.3074175  839290.4845308
#Sta/Elev= 30
       0 2491.89   56.81 2486.39    82.3  2476.1   90.41 2475.52  235.53 2474.46
  424.94 2468.33  476.11  2465.7  491.42 2462.19  548.38 2459.99  575.41 2461.88
  610.34  2457.8  645.01 2457.89 692.753  2452.8 714.036    2452 727.808  2452.5
 729.894  2452.9 758.689  2453.2 806.055  2459.4  964.45 2456.78 1080.72 2462.74
 1250.96 2460.26 1341.68 2462.98 1613.13 2464.29  1804.8 2462.31 1905.58 2464.75
 1976.94 2471.15 1997.92 2470.59 2012.71 2488.06 2065.76 2499.38 2086.61 2509.83
#Mann= 4 ,-1 , 0
       0     .06       0 692.753     .04       0 727.808     .09       0
 729.894     .06       0
#XS Ineff= 4 ,-1
       0  483.07    2485  980.42 2086.61    2485  519.26     616    2461
  806.05  957.07    2459
Permanent Ineff=
       F       F       F       F
#Block Obstruct= 3 ,-1
 1053.02 1216.532471.612 1543.48 1590.452473.705 1849.06 2022.21    2475
Bank Sta=692.753,727.808
Exp/Cntr=0.5,0.3

Type RM Length L Ch R = 1 ,21221.9 ,522.37,521,519.11
XS GIS Cut Line= 4
 1066669.2449171  838304.6720304 1066824.1928338  838497.0991138
 1067426.4636674  839289.2970308 1067523.9220008  839316.7866142
#Sta/Elev= 30
       0 2557.13    16.8 2555.92   32.57 2550.43    46.2 2542.28   60.24  2533.1
  131.44 2479.43  167.91 2455.24  173.37  2453.2  215.63  2450.3  219.63 2447.65
  232.02 2449.42  233.19 2449.36  241.35 2448.87  251.67 2452.83  492.15 2455.74
  576.12  2458.2  608.09 2461.42  677.38 2463.96  701.99 2460.12  753.13 2458.63
  908.41 2458.85 1128.19 2462.32 1179.25 2465.76 1204.96  2469.1 1221.13 2468.57
  1242.2 2479.02 1256.33 2489.39 1279.62 2494.86 1309.75 2498.88 1343.46 2515.15
#Mann= 4 ,-1 , 0
       0     .09       0  215.63     .04       0  232.02     .09       0
  233.19     .06       0
#XS Ineff= 2 , 0
       0                     350       0    2470
Permanent Ineff=
       F       F
#Block Obstruct= 3 ,-1
  649.45  697.742472.811  711.63 1057.31 2470.96 1074.98 1227.782481.825
Bank Sta=215.63,232.02
Exp/Cntr=0.3,0.1

Type RM Length L Ch R = 1 ,20700.9 ,56.64,56,55.2
XS GIS Cut Line= 6
 1066331.4949169  838693.0470306 1066401.7032503   838803.599114
 1066439.5990836  838842.7970306 1066452.7032503  838858.7970306
 1066492.0990836  838898.2032807 1067041.4428339  839771.1928644
#Sta/Elev= 30
       0 2464.17   24.37 2456.71   33.85 2454.76   54.53 2452.89 142.187  2450.6
 167.027  2451.7 170.779  2451.3 185.528  2444.7 193.291  2443.3 205.711  2444.6
 206.358  2445.4 226.541  2450.9  342.93 2451.37  427.62 2450.15  459.17 2447.23
  473.18 2451.54  477.42 2451.79  600.71 2452.06  683.53 2453.37  718.19 2452.54
  845.29 2455.34  905.95 2457.94 1028.04 2460.39 1050.64 2466.02 1076.65 2471.09
 1131.19 2471.33 1138.82 2477.01 1163.19 2486.44 1189.85 2491.09 1293.78  2504.3
#Mann= 4 ,-1 , 0
       0     .09       0 185.528     .04       0 205.711     .09       0
 206.358     .06       0
#XS Ineff= 2 , 0
       0                  391.92       0    2470
Permanent Ineff=
       F       F
#Block Obstruct= 3 ,-1
 323.441 415.992    2460 736.038  838.98    2460 1063.861102.114    2480
Bank Sta=185.528,205.711
Exp/Cntr=0.5,0.3

Type RM Length L Ch R = 1 ,20644.9 ,24.92,27.77,27.33
BEGIN DESCRIPTION:
U/S OF 11620
END DESCRIPTION:
XS GIS Cut Line= 6
 1066279.3438964  838596.0210554 1066279.3438964  838689.5002222
 1066350.2709798  838822.3752223 1066382.6980632   838866.791889
 1066574.1563967  839082.9689725 1066957.5001471  839749.1773065
#Sta/Elev= 30
       0 2494.37   93.48 2463.62  109.16 2460.94  125.75 2454.35  134.34 2452.69
  221.44 2450.58 289.809  2451.4 302.197  2450.2 305.358    2447 313.221  2443.7
     328  2443.4 334.257  2443.4 345.428  2447.4 353.597  2450.6  443.54 2450.69
  496.98 2452.95  524.68 2450.54  565.89 2450.88  579.83 2448.09  595.86 2451.98
  822.76 2452.45 1012.72 2457.59 1099.37 2458.07 1131.81 2461.91 1162.28 2468.42
 1224.71 2471.72  1240.1 2479.81 1260.31 2483.07    1314 2495.77 1357.54 2502.65
#Mann= 3 ,-1 , 0
       0     .09       0 305.358     .04       0 345.428     .06       0
#XS Ineff= 3 ,-1
       0   210.2    2449   274.7     294    2449     397 1261.29    2470
Permanent Ineff=
       F       F       F
#Block Obstruct= 4 ,-1
     746     787    2465     350     491    2465    5.01   77.952468.347
    1046    1093    2480
Bank Sta=305.358,345.428
Exp/Cntr=0.5,0.3

Type RM Length L Ch R = 3 ,20632.9 ,,,
BEGIN DESCRIPTION:
FBSTR 6691
END DESCRIPTION:
Bridge Culvert--1,0,-1,-1, 0
Deck Dist Width WeirC Skew NumUp NumDn MinLoCord MaxHiCord MaxSubmerge Is_Ogee
11.1,12,2.6,0, 60, 60, , , 0.95, 0, 1,1,,
       0    4.37   13.28   27.77   33.08   36.98   44.74   75.56  131.09  209.46
  218.78  267.25  269.99   278.3  299.56   300.6   300.6   345.6   345.6  351.35
  390.92  410.13  413.32  422.48   471.2  475.32  480.59   484.2  496.38  500.93
  520.34     611  746.46   792.3  806.47  819.26  869.08  894.98  935.79  949.95
  979.21  988.84 1007.79 1031.82 1057.35 1070.41  1098.1 1120.75 1134.61 1137.97
 1141.26 1143.96 1176.55 1179.52 1184.55 1199.86 1207.76 1220.67 1235.73 1261.29
  2460.8 2459.89 2458.76 2453.72 2452.62 2452.38 2452.58 2451.28 2450.41 2450.67
 2449.31 2449.63 2450.37    2450 2449.96    2449    2449    2449    2449 2451.26
 2453.06    2453 2452.17 2451.72 2450.77 2449.93 2447.84 2447.09 2450.14 2450.04
 2451.78 2451.51 2452.83 2453.93 2453.73 2454.46 2455.73 2456.94 2457.89 2459.54
 2457.93 2458.25 2460.86 2463.46 2468.24 2469.53 2471.47 2471.84 2479.35 2480.48
  2482.2 2482.65 2483.24 2483.46 2484.88 2491.11 2495.07 2500.38 2502.79 2502.65
                                                                                
                                                    2448    2448
                                                                                
                                                                                
                                                                                
                                                                                
       0    4.37   13.28   27.77   33.08   36.98   44.74   75.56  131.09  161.31
  209.46  212.26  218.78  306.86  334.72  344.38  344.83  344.83  389.33  389.33
  413.32  430.34   471.2  475.32  480.59   484.2  496.38  500.93  520.34     611
  746.46   792.3  806.47  819.26  843.14  869.08  894.98  935.79  949.95  979.21
  988.84 1007.79 1031.82 1057.35 1070.41  1082.9  1098.1 1120.75 1134.61 1137.97
 1141.26 1143.96 1149.27 1179.52 1184.55 1199.86 1207.76 1220.67 1225.84 1235.73
  2460.8 2459.89 2458.76 2453.72 2452.62 2452.38 2452.58 2451.28 2450.41 2450.68
 2450.67 2450.49 2449.31 2449.99 2450.96 2450.93    2449    2449    2449    2449
 2452.17 2451.47 2450.77 2449.93 2447.84 2447.09 2450.14 2450.04 2451.78 2451.51
 2452.83 2453.93 2453.73 2454.46 2454.87 2455.73 2456.94 2457.89 2459.54 2457.93
 2458.25 2460.86 2463.46 2468.24 2469.53 2470.17 2471.47 2471.84 2479.35 2480.48
  2482.2 2482.65 2482.56 2483.46 2484.88 2491.11 2495.07 2500.38 2501.39 2502.79
                                                                                
                                                            2448    2448
                                                                                
                                                                                
                                                                                
                                                                                
BR Coef=-1 , 0 , 0 ,, 0 ,,,0.8,0,,0,
WSPro=,,,, 1 ,,,, 0 ,,,, 0 ,,,,-1 ,-1 ,-1 , 0 , 0 , 0 , 0 , 0
BC Design=,, 0 ,, 0 ,,,,,,

Type RM Length L Ch R = 1 ,20616.9 ,44.3,42.19,42.97
BEGIN DESCRIPTION:
D/S OF 11620
END DESCRIPTION:
XS GIS Cut Line= 6
 1066250.5730631  838594.2293887 1066245.1876464  838700.2918888
 1066321.5938965  838834.5939723 1066434.7918133  838957.0939724
 1066544.5105634  839118.1877226 1066905.0209804  839743.0106398
#Sta/Elev= 30
       0 2493.12   28.57 2481.73   92.31 2462.81   106.2 2459.62  125.06 2456.93
   144.9 2452.08  241.18 2450.34 339.875  2451.1 347.182  2445.6 356.106  2443.1
 376.252  2443.4 380.829  2445.6 393.114  2450.4  431.36 2450.03  505.33  2453.1
  586.17 2451.21  605.29 2447.11  612.97 2449.35  639.47 2451.73  743.26  2451.4
  870.17 2452.88  967.14 2455.25 1126.42 2461.59 1157.71 2464.98 1188.76 2470.12
 1222.79 2472.27 1246.89 2482.38 1298.52 2483.77 1326.31  2498.8 1344.77 2504.95
#Mann= 3 ,-1 , 0
       0     .06       0 347.182     .04       0 380.829     .06       0
#XS Ineff= 4 ,-1
       0      90    2480     293     342    2450     392 1241.61    2480
      91   226.5    2450
Permanent Ineff=
       F       F       F       F
#Block Obstruct= 7 ,-1
                              20      90    2460     392 490.558    2460
     652     691    2460     785     878    2460     938    1009    2460
    1133    1199    2490
Bank Sta=347.182,380.829
Exp/Cntr=0.5,0.3

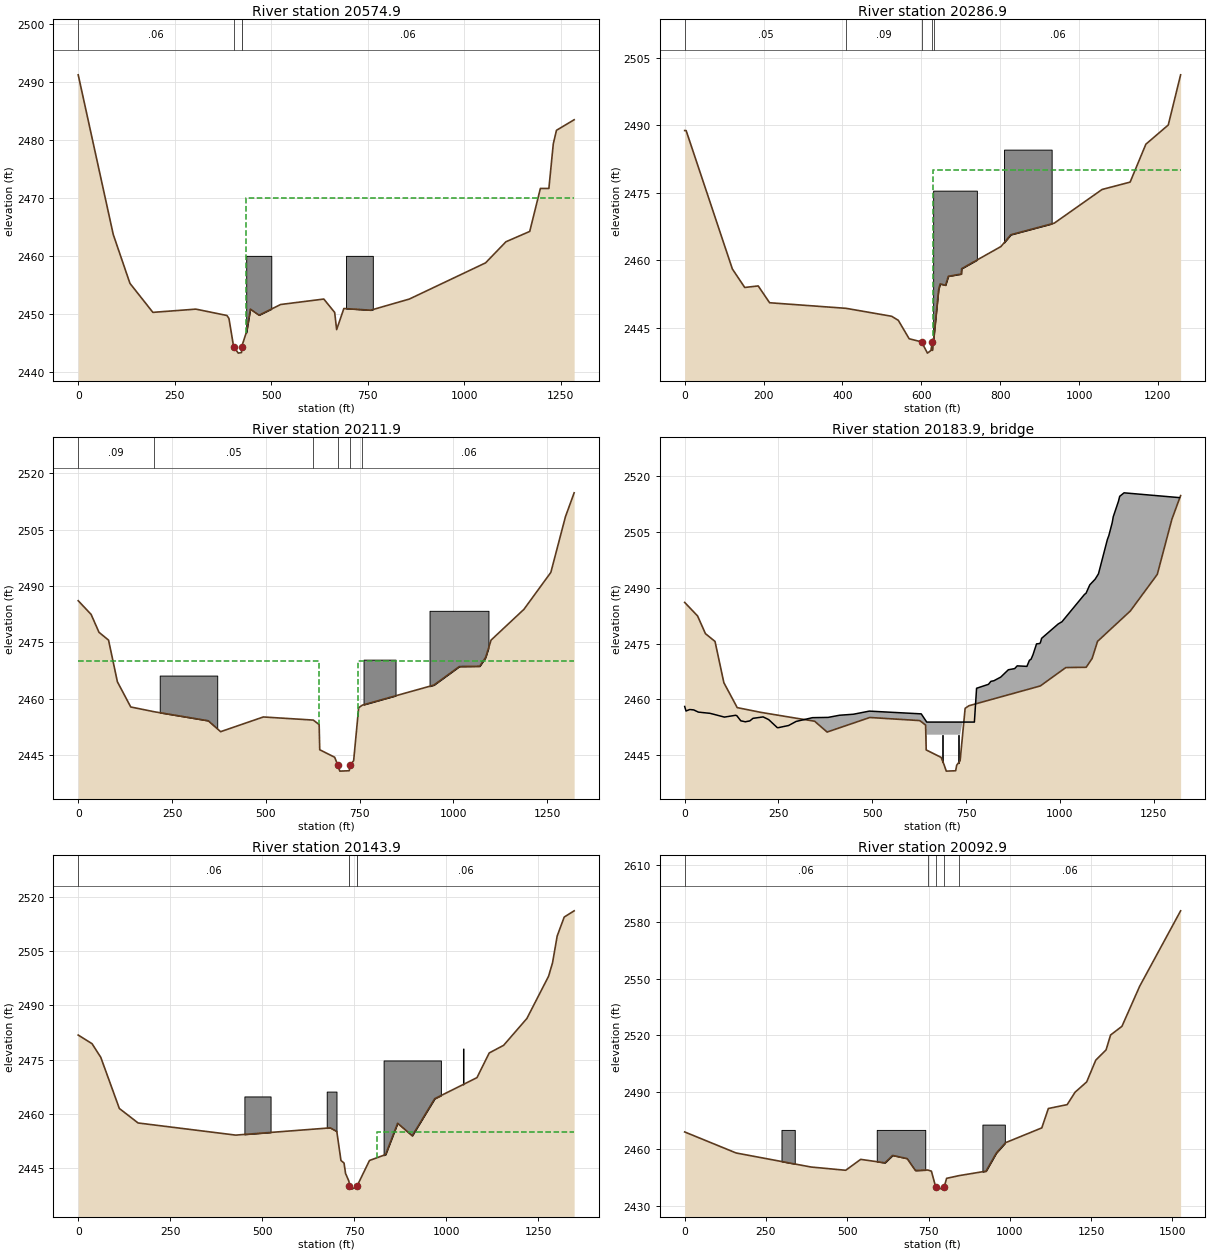
Type RM Length L Ch R = 1 ,20574.9 ,271.63,287.89,294.31
XS GIS Cut Line= 6
 1066220.0209797  838583.4377221 1066203.8334797  838716.4689722
 1066283.6980631  838867.9898057 1066373.9897299  838957.6981391
 1066406.2918132  838987.0939724 1066790.8438969  839697.5210564
#Sta/Elev= 30
       0 2491.27    90.8 2463.68  134.01 2455.25  193.39 2450.24 304.702  2450.8
 385.114  2449.7 390.325  2449.2 402.504  2444.3 414.588  2443.2 422.962  2443.3
 424.331  2444.3 424.785  2444.6 436.468    2447 445.815  2450.8  468.14 2449.76
   524.3  2451.6  636.04 2452.54  664.16 2450.23  669.26 2447.26  687.97 2450.91
  757.59 2450.62  857.54 2452.54 1054.92 2458.79 1107.81 2462.44  1169.3 2464.22
  1196.9 2471.64 1218.94 2471.65 1230.32 2479.35  1238.6 2481.69 1284.35 2483.51
#Mann= 4 ,-1 , 0
       0     .06       0 402.504     .04       0 424.331     .09       0
 424.785     .06       0
#XS Ineff= 2 , 0
       0                     435       0    2470
Permanent Ineff=
       F       F
#Block Obstruct= 3 ,-1
      16  96.685    2450     435     500    2460 693.389  762.93    2460
Bank Sta=402.504,424.331
Exp/Cntr=0.3,0.1

Type RM Length L Ch R = 1 ,20286.9 ,79.66,75.52,85.02
XS GIS Cut Line= 6
 1066157.0938963  838551.0835554 1066098.9897296  838961.9898057
 1066174.9897297  839183.8960559 1066191.8126464  839336.6773061
 1066265.5418131   839603.531473 1066234.2084797  839771.9481398
#Sta/Elev= 30
       0 2488.83    3.74 2488.81  120.93 2458.02  152.28 2453.91  186.44 2454.25
  215.35 2450.51  408.96 2449.27 524.747  2447.5 541.672  2446.6 569.194  2442.5
 600.478  2441.8  615.59  2439.3 624.509  2439.9 627.509  2441.8 628.175  2439.9
 632.631  2443.6 643.837  2453.4 647.729  2454.7  661.34  2454.4 668.596  2456.4
 701.341  2456.9  702.28 2458.09  802.01 2463.02  827.01 2465.64  937.17 2468.22
 1058.28 2475.71 1129.46 2477.35 1169.34 2485.78 1226.21 2490.06 1257.49 2501.22
#Mann= 5 ,-1 , 0
       0     .05       0  408.96     .09       0 600.478     .04       0
 627.509     .09       0 632.631     .06       0
#XS Ineff= 2 , 0
       0                     630       0    2480
Permanent Ineff=
       F       F
#Block Obstruct= 2 ,-1
     630  740.862475.451  809.79  930.462484.578
Bank Sta=600.478,627.509
Exp/Cntr=0.5,0.3

Type RM Length L Ch R = 1 ,20211.9 ,61.59,68,71.16
BEGIN DESCRIPTION:
U/S OF
END DESCRIPTION:
XS GIS Cut Line= 6
 1066086.7345001  838418.9845304 1066035.8386668  838510.1824472
 1066048.5574168  838607.7345305 1066022.3178334  838897.0470307
 1066124.3386668  839455.3386976 1066132.7865835  839708.0574477
#Sta/Elev= 30
       0  2486.1   34.37 2482.46   55.38 2477.69   80.86  2475.6  104.44  2464.5
  139.99 2457.79  202.57 2456.52  346.42 2454.12  379.53 2451.21  493.35 2455.13
 626.435  2454.3 642.029  2453.1 643.615  2446.4 683.395  2444.4 691.325  2442.4
  697.14  2440.7 722.118  2440.8 724.893  2442.3 734.012  2443.5  747.36  2457.6
 757.537  2458.3  947.73 2463.62 1015.72 2468.57 1069.99 2468.64 1085.66 2470.99
 1100.28 2475.62 1187.68  2483.8 1259.44 2493.64 1298.41 2508.49 1321.59 2514.85
#Mann= 6 ,-1 , 0
       0     .09       0  202.57     .05       0 626.435     .09       0
 691.325     .04       0 724.893     .09       0 757.537     .06       0
#XS Ineff= 2 , 0
       0  640.97    2470  745.11       0    2470
Permanent Ineff=
       F       F
#Block Obstruct= 3 ,-1
   936.2 1093.262483.414   217.2  370.452466.161  760.35  845.612470.404
Bank Sta=691.325,724.893
Exp/Cntr=0.5,0.3

Type RM Length L Ch R = 3 ,20183.9 ,,,
BEGIN DESCRIPTION:
FBSTR 1382
END DESCRIPTION:
Bridge Culvert--1,0,-1,-1, 0
Deck Dist Width WeirC Skew NumUp NumDn MinLoCord MaxHiCord MaxSubmerge Is_Ogee
26.3,37,2.6,0, 60, 60, , , 0.95, 0, 1,1,,
       0    3.51   13.46   24.07   36.53   67.76  105.92  135.59  138.96  149.58
  161.51  173.57  181.87  209.07  223.94  246.64  249.22  277.06  296.99  340.73
  382.26  412.66  449.58  492.13  630.39  645.01  645.01  772.01  772.01  777.85
  809.51  816.06  824.04  842.28  862.49  879.34  886.08  911.94  918.66  923.09
  928.32  937.62   946.2  948.08  951.16  995.53 1005.31 1065.23 1069.57 1079.55
 1093.72 1102.67 1126.36 1130.31  1139.3 1142.07 1155.93 1159.22  1170.9  1318.5
  2458.1 2456.88 2457.28 2457.17 2456.58 2456.25 2455.24 2455.73 2455.61 2454.24
 2453.98 2454.21  2454.9 2455.29 2454.56 2452.41 2452.39 2452.98 2454.07 2455.09
 2455.16 2455.74 2456.01 2456.85 2456.11  2453.9  2453.9  2453.9  2453.9    2463
 2464.06 2464.86 2465.03 2466.01 2467.98 2468.29 2469.03 2468.89 2470.52 2470.83
 2472.07 2474.94 2475.05 2475.33 2476.44 2480.32 2480.89 2488.23 2488.58 2490.83
 2492.34  2493.8 2503.01  2504.1 2507.57 2509.16 2513.31 2514.65 2515.59  2514.3
                                                                                
                                                                                
                                                  2450.5  2450.5
                                                                                
                                                                                
                                                                                
       0    3.51   13.46   24.07   36.53   67.76  105.92  135.59  138.96  149.58
  161.51  173.57  181.87  209.07  223.94  246.64  249.22  277.06  296.99  340.73
  382.26  412.66  449.58  492.13  501.89  504.41  507.68  630.39  681.21  681.21
  808.21  808.21  809.51  816.06  842.28  862.49  879.34  886.08  911.94  918.66
  923.09  928.32  937.62   946.2  948.08  951.16  995.53 1005.31 1069.57 1079.55
 1093.72 1102.67 1126.36 1130.31  1139.3 1142.07 1155.93 1159.22  1170.9  1318.5
  2458.1 2456.88 2457.28 2457.17 2456.58 2456.25 2455.24 2455.73 2455.61 2454.24
 2453.98 2454.21  2454.9 2455.29 2454.56 2452.41 2452.39 2452.98 2454.07 2455.09
 2455.16 2455.74 2456.01 2456.85 2456.85 2456.57 2455.23 2456.11  2453.9  2453.9
  2453.9  2453.9 2464.06 2464.86 2466.01 2467.98 2468.29 2469.03 2468.89 2470.52
 2470.83 2472.07 2474.94 2475.05 2475.33 2476.44 2480.32 2480.89 2488.58 2490.83
 2492.34  2493.8 2503.01  2504.1 2507.57 2509.16 2513.31 2514.65 2515.59  2514.3
                                                                                
                                                                                
                                                                          2450.5
  2450.5
                                                                                
                                                                                
Pier Skew, UpSta & Num, DnSta & Num=  ,688.01, 2 ,722.21, 2 , 0 , 0 , 0 ,,
     2.3     2.3
  2441.1  2450.5
     2.3     2.3
  2439.3  2450.5
Pier Skew, UpSta & Num, DnSta & Num=  ,730.01, 2 ,764.21, 2 , 0 , 0 , 0 ,,
     2.3     2.3
  2441.1  2450.5
     2.3     2.3
  2439.3  2450.5
BR Coef=-1 , 0 , 0 ,, 0 ,,,0.8,-1,,0,
WSPro=,,,, 1 ,,,, 0 ,,,, 0 ,,,,-1 ,-1 ,-1 , 0 , 0 , 0 , 0 , 0
BC Design=,, 0 ,, 0 ,,,,,,

Type RM Length L Ch R = 1 ,20143.9 ,49.08,51,54.9
XS GIS Cut Line= 6
 1066078.2553335  838370.2032804 1066004.9115834  838479.1407805
 1065980.5990834  838573.1303638 1065992.5990834  839108.9949474
 1066063.4636668  839453.1824476 1066082.7761668  839682.0678644
#Sta/Elev= 30
       0  2481.8   37.68 2479.41   61.34 2475.66  111.84 2461.55  162.79 2457.55
  428.19  2454.2 685.516  2456.2 703.045  2455.2 714.372  2447.2 722.732  2446.5
 726.912  2443.6 735.946  2441.5 737.564  2440.2  744.71  2439.3  757.52  2440.1
 758.868  2440.3 791.904  2447.2  835.73 2448.83  868.41 2457.47  908.16 2454.02
  969.28 2464.24 1084.18 2470.06 1117.45 2476.86 1156.64 2478.97  1219.9 2486.38
 1278.83 2498.02 1289.63 2501.74 1302.24 2509.12 1321.34 2514.35 1348.38 2516.07
#Mann= 5 ,-1 , 0
       0     .06       0 735.946     .09       0 737.564    .045       0
  757.52     .09       0 758.868     .06       0
#XS Ineff= 2 , 0
       0     700    2455  811.99       0    2455
Permanent Ineff=
       F       F
#Block Obstruct= 4 ,-1
 1045.97 1047.692478.084  451.82  522.982464.866  675.66  702.242466.206
  830.31  986.062474.792
Bank Sta=737.564,757.52
Exp/Cntr=0.5,0.3

Type RM Length L Ch R = 1 ,20092.9 ,652.56,659,657.66
XS GIS Cut Line= 6
 1066042.2032501  838329.9116137     1065911.047  838577.5574472
 1065948.2032501  839042.9949474     1065924.797  839190.4949475
 1065929.3074167  839290.1928642 1065993.2553334  839813.9949478
#Sta/Elev= 30
       0 2468.92  158.27  2457.8  388.35 2450.39  495.17 2448.66  541.23 2454.43
  615.86 2452.59  639.39 2456.52  683.98 2454.85  709.51 2448.54  747.31  2448.8
 758.748  2448.2 772.322  2439.6 793.216  2438.7 798.096  2439.8 805.417  2444.4
 842.783  2445.8  926.74  2448.2  958.33 2457.77  986.57 2463.23 1098.23 2471.07
 1118.39 2481.31 1176.28 2483.36 1200.55 2489.92 1236.18 2495.35 1264.14 2506.85
 1295.94 2512.31  1309.7 2520.15 1344.72 2524.75 1399.14  2545.9 1525.12 2585.78
#Mann= 5 ,-1 , 0
       0     .06       0  747.31     .09       0 772.322     .04       0
 798.096     .09       0 842.783     .06       0
#Block Obstruct= 3 ,-1
 297.676  338.48    2470  915.61  984.542472.801 590.699 739.796    2470
Bank Sta=772.322,798.096
Exp/Cntr=0.3,0.1

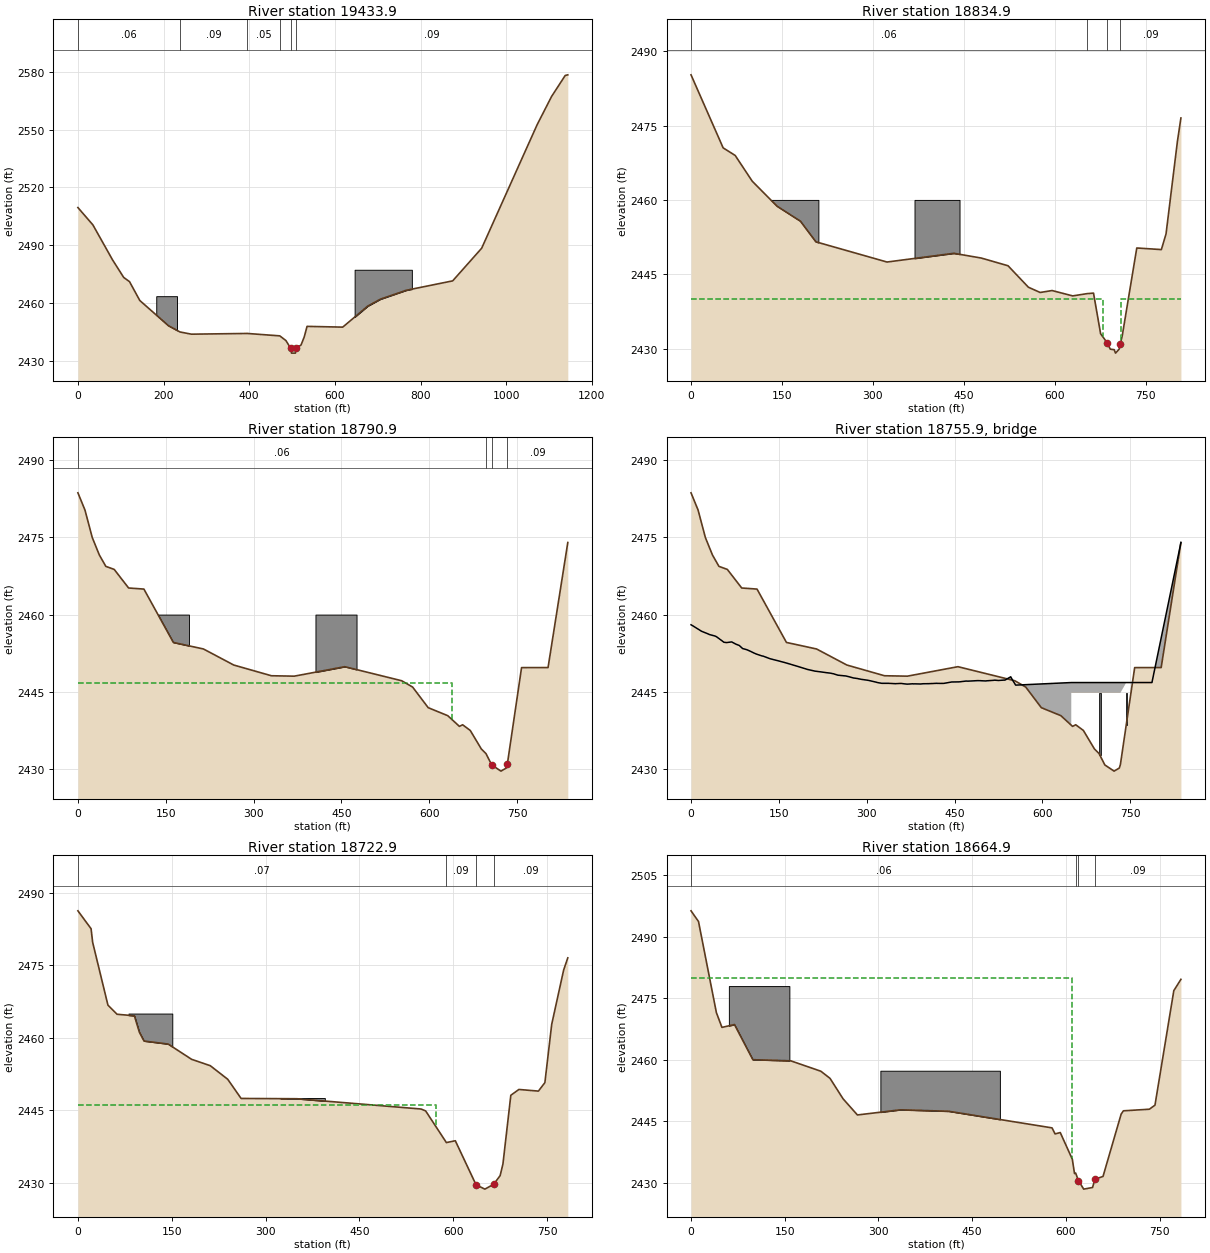
Type RM Length L Ch R = 1 ,19433.9 ,598,599,603.51
XS GIS Cut Line= 6
 1065491.2449165  838354.0574471 1065401.0053331  838547.9116138
 1065330.8178331  838865.4220307 1065287.3699164  839065.9532807
 1065284.0261664  839196.2970308 1065157.0261664  839433.5991142
#Sta/Elev= 30
       0 2509.54   34.99 2500.54   80.98 2482.32  106.97 2473.22  120.53 2471.03
  144.52 2461.24  211.24 2448.17   238.1 2444.91  264.89 2443.75  395.43 2444.12
  471.25 2442.87  485.58 2440.44  496.38 2436.56  496.74 2436.43  498.67  2433.9
  507.78  2433.9   510.1 2436.49  520.86 2438.11  528.42 2442.33  534.99  2447.8
  618.23 2447.41  676.74 2458.35  706.07 2461.93  766.27 2466.54  874.95 2471.45
  942.66 2488.42 1072.08 2552.58 1105.84 2567.27 1137.68 2578.19 1143.72 2578.52
#Mann= 6 ,-1 , 0
       0     .06       0   238.1     .09       0  395.43     .05       0
  471.25     .09       0  496.74     .04       0   510.1     .09       0
#Block Obstruct= 2 ,-1
   182.9  231.412463.493     646  779.642477.232
Bank Sta=496.38,510.1
Exp/Cntr=0.3,0.1

Type RM Length L Ch R = 1 ,18834.9 ,45.22,44,40.03
BEGIN DESCRIPTION:
surveyed section
END DESCRIPTION:
XS GIS Cut Line= 6
  1065058.411583   838210.932447 1064762.7969995  838793.8074473
 1064749.7969995  838847.4949473 1064734.5990828  838866.7032807
 1064716.9949162   838897.099114 1064709.9636661   838935.755364
#Sta/Elev= 30
       0 2485.22   52.99 2470.49   72.87 2468.96  100.97 2463.77  141.75 2458.74
  180.29 2455.72  205.87 2451.55  323.27 2447.47  433.48 2449.23  478.88 2448.27
  522.92 2446.72  556.52 2442.39  575.92 2441.33  595.57 2441.72  629.64 2440.64
  653.53  2441.1 663.954  2441.2 675.672    2433  686.42  2431.2 691.592  2429.9
 697.976  2429.8 700.239  2429.1 706.219  2429.9 708.078  2430.9  711.31  2432.6
 735.312  2450.3  775.87 2449.98  783.57 2453.14   802.3 2471.76  808.12 2476.52
#Mann= 4 ,-1 , 0
       0     .06       0  653.53     .09       0  686.42     .05       0
 708.078     .09       0
#XS Ineff= 2 , 0
       0  679.37    2440  709.75       0    2440
Permanent Ineff=
       F       F
#Block Obstruct= 2 ,-1
 108.121 210.086    2460 368.651442.8999    2460
Bank Sta=686.42,708.078
Exp/Cntr=0.5,0.3

Type RM Length L Ch R = 1 ,18790.9 ,66.83,68,71.1
BEGIN DESCRIPTION:
u/s of 9743 surveyed section
END DESCRIPTION:
XS GIS Cut Line= 6
  1065007.567833  838163.0782803 1064726.0990828  838756.7970306
 1064711.9011661  838829.7970306 1064705.2032495  838854.9949473
 1064690.9011661  838886.9011973 1064680.8386661  838929.7657807
#Sta/Elev= 30
       0 2483.64   12.02 2480.31   24.54 2474.95   36.61 2471.57   47.68 2469.36
   61.99 2468.77    86.6 2465.16  112.73 2464.95  162.95 2454.59   214.4 2453.32
  266.18  2450.2  330.46 2448.12  369.51 2448.04  455.89 2449.88  552.98 2447.15
  571.59 2445.93  598.26 2441.92   631.6 2440.37  651.59 2438.29 657.044  2438.6
 670.096  2437.5 689.005  2433.9 696.953    2433 706.743  2430.8 722.556  2429.6
 731.508  2430.2 733.349  2430.9 757.696  2449.7  802.95 2449.71  836.68 2473.99
#Mann= 4 ,-1 , 0
       0     .06       0 696.953     .09       0 706.743    .045       0
 733.349     .09       0
#XS Ineff= 2 , 0
       0  639.39  2446.8     797       0  2446.8
Permanent Ineff=
       F       F
#Block Obstruct= 2 ,-1
 124.635 189.606    2460 405.715 475.866    2460
Bank Sta=706.743,733.349
Exp/Cntr=0.5,0.3

Type RM Length L Ch R = 3 ,18755.9 ,,,
BEGIN DESCRIPTION:
FBSTR 1376
END DESCRIPTION:
Bridge Culvert--1,0,-1,-1, 0
Deck Dist Width WeirC Skew NumUp NumDn MinLoCord MaxHiCord MaxSubmerge Is_Ogee
25.4,40,2.6,0, 106, 115, , , 0.95, 0, 1,1,,
       0    4.64    5.44   17.79   17.96   17.97   29.71   30.87   41.36    43.7
   52.97   56.16   60.87   69.47   76.52   82.37   88.15   95.21    99.9  108.14
  111.64  121.05  123.46  133.92  135.14  146.89  147.02  147.03  159.13  159.91
  171.26  172.89  183.31  185.76  195.44  198.79  207.69  211.85  219.81  224.76
   231.9  237.77  244.05  245.21  250.88  262.26  264.24  269.09  277.34  283.18
   290.5  301.02  303.19  303.88   314.5  318.84  325.76  333.72  337.01  347.14
  348.26  348.74   358.6  363.63  369.12  378.62  379.62  381.94  392.12  396.57
   405.4  415.68  418.76  425.72  431.91  435.75  445.11  457.11  458.36  460.37
  469.79     473  481.12  488.16  492.44   501.3  503.34  503.73  504.83   514.5
  518.95  524.83  525.23  534.83  535.92  538.18  546.02  547.68   548.6  550.16
  554.42  649.39  649.39  787.19  787.19  836.68
 2458.02 2457.71 2457.65 2456.77 2456.76 2456.76 2456.22 2456.14 2455.82 2455.68
  2454.9 2454.62 2454.56 2454.69 2454.26    2454  2453.4 2453.18 2452.95  2452.5
 2452.33 2451.97 2451.92 2451.47 2451.42 2451.08 2451.08 2451.08 2450.71 2450.69
 2450.31 2450.25  2449.9 2449.81 2449.47 2449.35 2449.12 2449.01  2448.9 2448.82
 2448.71 2448.63 2448.48 2448.43 2448.23  2448.1 2448.08 2447.95 2447.69  2447.6
 2447.43 2447.26 2447.21  2447.2 2446.92 2446.79 2446.65 2446.65 2446.65 2446.59
 2446.58 2446.58 2446.63 2446.56 2446.49 2446.56 2446.54 2446.55 2446.52 2446.57
 2446.58 2446.63 2446.65 2446.63 2446.64 2446.72 2446.91 2446.93 2446.94 2446.96
 2447.09 2447.07 2447.12 2447.17 2447.17 2447.12 2447.11 2447.11 2447.14 2447.21
 2447.26  2447.2  2447.2 2447.28 2447.26 2447.41 2447.92 2447.57 2447.39 2447.09
  2446.3  2446.8  2446.8  2446.8  2446.8 2473.99
                                                                                
                                                                                
                                                                                
                                                                                
                                                                                
                                                                                
                                                                                
                                                                                
                                                                                
                                                                                
                  2444.8  2444.8
       0    4.64    5.44   17.79   17.96   17.97   29.71   30.87   41.36    43.7
   52.97   56.16   60.87   69.47   76.52   82.37   88.15   95.21    99.9  108.14
  111.64  121.05  123.46  133.92  135.14  146.89  147.02  147.03  159.13  159.91
  171.26  172.89  183.31  185.76  195.44  198.79  207.69  211.85  219.81  224.76
   231.9  237.77  244.05  245.21  250.88  262.26  264.24  269.09  277.34  283.18
   290.5  301.02  303.19  303.88   314.5  318.84  325.76  333.72  337.01  347.14
  348.26  348.74   358.6  363.63  369.12  378.62  379.62  381.94  392.12  396.57
   405.4  415.68  418.76  425.72  431.91  435.75  445.11  457.11  458.36  460.37
  469.79     473  481.12  488.16  492.44   501.3  503.34  503.73  504.83   514.5
  518.95  524.83  525.23  534.83  535.92  538.18  546.02  547.68   548.6  550.16
  554.42  581.78  581.78  719.58  719.58  720.12  732.28  733.15  734.05  735.38
  746.26  746.92  764.58  775.59  778.58
 2458.02 2457.71 2457.65 2456.77 2456.76 2456.76 2456.22 2456.14 2455.82 2455.68
  2454.9 2454.62 2454.56 2454.69 2454.26    2454  2453.4 2453.18 2452.95  2452.5
 2452.33 2451.97 2451.92 2451.47 2451.42 2451.08 2451.08 2451.08 2450.71 2450.69
 2450.31 2450.25  2449.9 2449.81 2449.47 2449.35 2449.12 2449.01  2448.9 2448.82
 2448.71 2448.63 2448.48 2448.43 2448.23  2448.1 2448.08 2447.95 2447.69  2447.6
 2447.43 2447.26 2447.21  2447.2 2446.92 2446.79 2446.65 2446.65 2446.65 2446.59
 2446.58 2446.58 2446.63 2446.56 2446.49 2446.56 2446.54 2446.55 2446.52 2446.57
 2446.58 2446.63 2446.65 2446.63 2446.64 2446.72 2446.91 2446.93 2446.94 2446.96
 2447.09 2447.07 2447.12 2447.17 2447.17 2447.12 2447.11 2447.11 2447.14 2447.21
 2447.26  2447.2  2447.2 2447.28 2447.26 2447.41 2447.92 2447.57 2447.39 2447.09
  2446.3  2446.8  2446.8  2446.8 2431.33  2449.6 2449.91  2449.9 2450.08 2450.34
 2451.89 2452.44 2462.39 2469.43 2471.47
                                                                                
                                                                                
                                                                                
                                                                                
                                                                                
                                                                                
                                                                                
                                                                                
                                                                                
                                                                                
                  2445.9  2445.9
                                        
Pier Skew, UpSta & Num, DnSta & Num=  ,698.39, 2 ,630.75, 2 , 0 , 0 , 0 ,,
       2       2
  2429.6  2444.8
       2       2
  2428.7  2445.9
Pier Skew, UpSta & Num, DnSta & Num=  ,743.39, 2 ,675.75, 2 , 0 , 0 , 0 ,,
       2       2
  2429.6  2444.8
       2       2
  2428.7  2445.9
BR Coef=-1 , 0 , 0 ,, 0 ,,,0.8,-1,,0,
WSPro=,,,, 1 ,,,, 0 ,,,, 0 ,,,,-1 ,-1 ,-1 , 0 , 0 , 0 , 0 , 0
BC Design=,, 0 ,, 0 ,,,,,,

Type RM Length L Ch R = 1 ,18722.9 ,55.18,58,60.43
BEGIN DESCRIPTION:
d/s of 9743 surveyed section
END DESCRIPTION:
XS GIS Cut Line= 6
 1064765.9844995  838148.7970303 1064761.1407495  838195.1616137
 1064707.8490828  838399.3178638 1064674.7969995  838715.5991139
 1064642.2032495  838813.9011973 1064623.0990828  838915.5574473
#Sta/Elev= 30
       0 2486.22   21.06 2482.52   23.58 2479.71   48.01 2466.73   62.57 2464.84
   90.29 2464.53   98.14 2461.16  105.68 2459.31  144.26 2458.69  181.78 2455.53
  211.67 2454.21  239.52 2451.41  260.94 2447.44  350.22 2447.38  548.59 2445.26
  556.03 2444.86  589.15 2438.32 603.444  2438.7 636.577  2429.6 650.676  2428.7
 664.775  2429.7 675.115  2431.5  679.58  2433.9  692.19  2448.1 705.115  2449.3
  736.31 2448.96  746.65 2450.71  757.54 2462.75  776.62 2473.98  783.29  2476.5
#Mann= 4 ,-1 , 0
       0     .07       0  589.15     .09       0 636.577     .04       0
 664.775     .09       0
#XS Ineff= 2 , 0
       0  571.78    2446  729.58       0    2446
Permanent Ineff=
       F       F
#Block Obstruct= 2 ,-1
   323.8  394.792447.529   80.86   150.92464.988
Bank Sta=636.577,664.775
Exp/Cntr=0.5,0.3

Type RM Length L Ch R = 1 ,18664.9 ,225.37,219,212.23
BEGIN DESCRIPTION:
surveyed section
END DESCRIPTION:
XS GIS Cut Line= 6
 1064712.9428328  838137.6095303 1064624.4011661  838699.2970306
 1064617.7032494  838720.7032806 1064590.9949161  838782.9949473
 1064558.2969994  838848.2032806 1064556.5990827  838899.8907807
#Sta/Elev= 30
       0 2496.38   11.97 2493.78   40.58 2471.57    49.5 2467.95   69.54 2468.64
   98.94 2460.07  159.54  2459.8  207.82 2457.26  222.52 2455.52  243.41 2450.53
  266.37 2446.59  335.36 2447.85  412.63 2447.49  577.94 2443.44  582.79 2441.97
  591.09  2442.3 610.382  2435.8 613.911  2432.3 615.794  2432.4 620.107  2430.6
 628.655  2428.5 642.772  2428.9 646.615  2430.9 659.555  2431.6 688.572  2446.8
  692.18  2447.6  733.74 2447.99  742.72 2448.98  772.88 2476.91  784.25 2479.67
#Mann= 4 ,-1 , 0
       0     .06       0 615.794     .09       0 620.107     .05       0
 646.615     .09       0
#XS Ineff= 2 , 0
       0  610.39    2480               0
Permanent Ineff=
       F       F
#Block Obstruct= 2 ,-1
   60.58  157.432478.027  303.12  494.442457.382
Bank Sta=620.107,646.615
Exp/Cntr=0.3,0.1

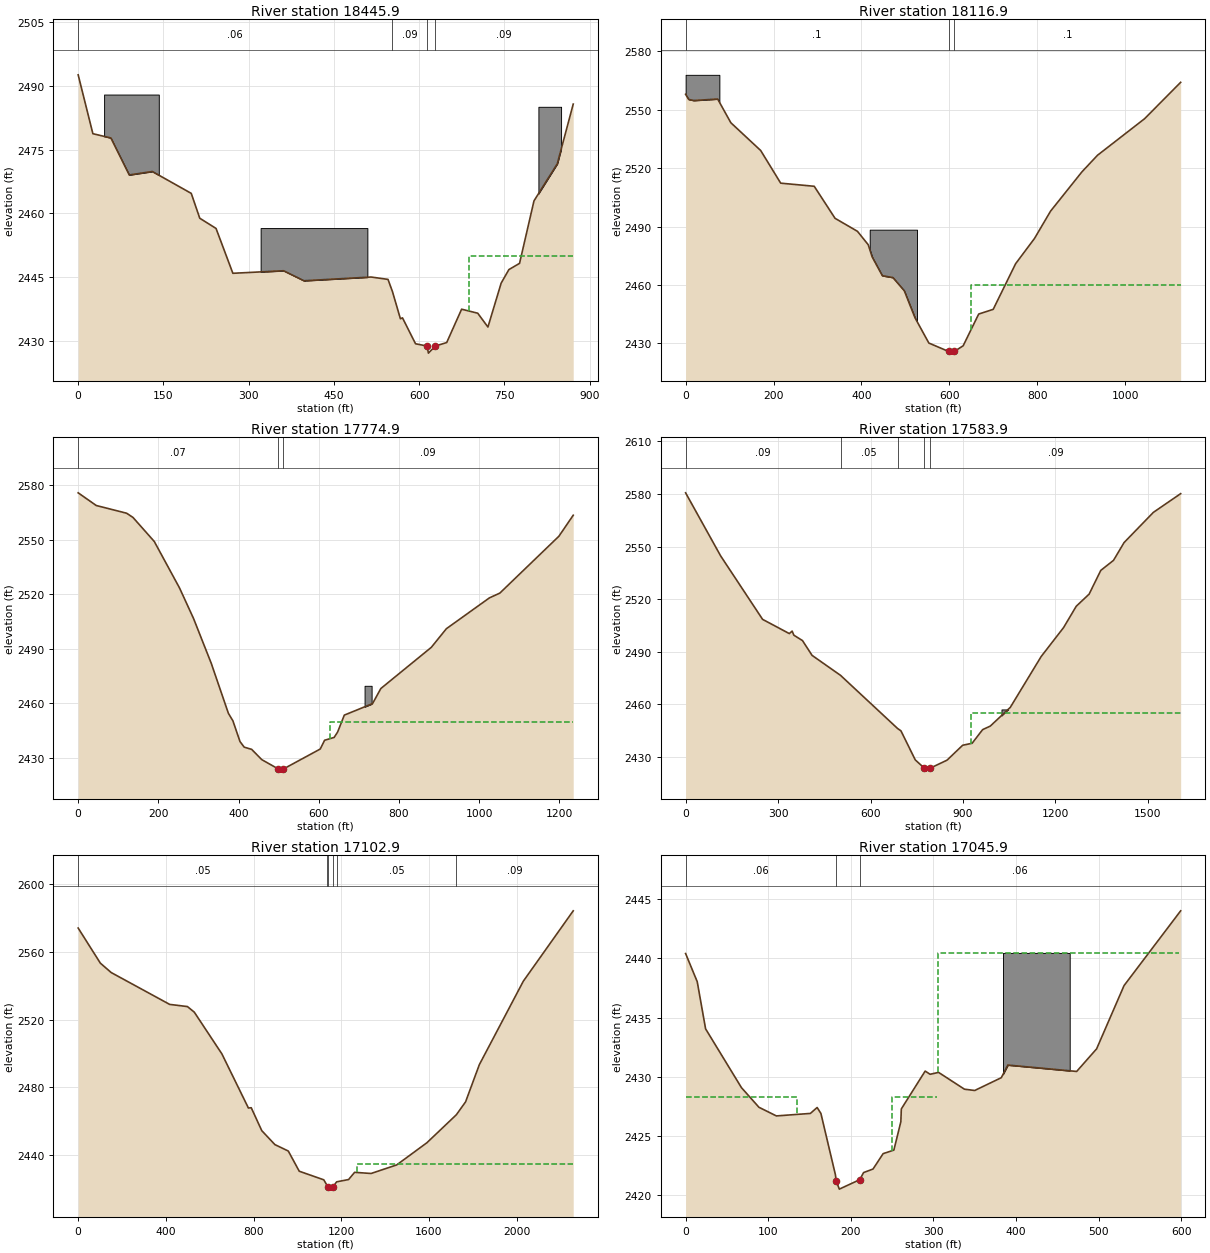
Type RM Length L Ch R = 1 ,18445.9 ,339.37,329,321.78
XS GIS Cut Line= 6
  1064490.088666  838084.5053636 1064439.4115827  838311.5782804
 1064431.9115827  838343.4845304  1064396.244916  838673.7866139
  1064386.869916  838746.9741139 1064403.7553327  838945.9011974
#Sta/Elev= 30
       0 2492.65   25.88 2478.78   57.58 2477.77   89.87 2469.06  130.51 2469.87
  198.98 2464.72  213.97 2458.86  242.58 2456.46  272.21 2445.89  361.45 2446.49
  397.27 2444.13  515.48 2445.01  545.16 2444.45  552.96 2441.61  566.99 2435.18
  570.67 2435.39   593.6 2429.29  613.85 2428.75  616.27 2427.08   628.4 2428.75
  648.48 2429.57  674.68 2437.43  703.09 2436.48  721.01 2433.23   744.3 2443.58
  757.86 2446.76  776.64 2448.23  802.03 2462.95  843.09  2471.7  871.09 2485.76
#Mann= 4 ,-1 , 0
       0     .06       0  552.96     .09       0  613.85     .05       0
   628.4     .09       0
#XS Ineff= 2 , 0
       0                   688.1       0    2450
Permanent Ineff=
       F       F
#Block Obstruct= 3 ,-1
  321.04  508.892456.545   45.62  141.862488.007  809.82  849.72 2485.12
Bank Sta=613.85,628.4
Exp/Cntr=0.3,0.1

Type RM Length L Ch R = 1 ,18116.9 ,341.36,342,343.64
XS GIS Cut Line= 6
 1063846.3699157  838263.5991137 1063907.5886658  838461.5261971
 1063942.2761658  838539.0678638 1064056.5365825  838708.4220306
 1064103.4740825  838855.3386973  1064372.807416  839247.0991142
#Sta/Elev= 30
       0    2558    6.93 2555.37    18.6 2554.79   72.97 2555.56  102.92 2543.37
  170.78  2529.1  216.32 2512.31  292.58 2510.71  339.95 2494.24  390.93 2487.55
  415.38 2480.66  424.39 2474.39   447.5 2464.73  471.63 2463.78  497.45 2456.98
  521.76 2443.13  553.31 2430.12  598.48 2425.78  600.91 2424.94  611.12  2425.8
  631.34 2428.71   666.7 2445.03  699.66 2447.44  750.64  2470.9  793.52 2483.85
  830.28 2497.97  901.52 2518.13  936.89 2526.65 1044.04 2545.44 1126.07 2564.15
#Mann= 3 ,-1 , 0
       0      .1       0  598.48     .04       0  611.12      .1       0
#XS Ineff= 2 , 0
       0                     649       0    2460
Permanent Ineff=
       F       F
#Block Obstruct= 2 ,-1
  418.81  526.372488.397       0   76.782567.999
Bank Sta=598.48,611.12
Exp/Cntr=0.3,0.1

Type RM Length L Ch R = 1 ,17774.9 ,198.34,191,186.02
XS GIS Cut Line= 6
 1063688.2865823  838419.4741138 1063743.1615824  838825.7970306
 1063773.1928324   838955.286614 1063795.7136657  839020.9741141
 1063861.3907491  839112.9220308 1064282.6303326  839399.6720309
#Sta/Elev= 30
       0 2575.82   45.14 2568.85  121.02  2564.6  136.75 2562.28  189.94 2549.05
  252.93 2523.48  287.87  2506.7  332.13    2482  374.76 2454.58  386.08 2450.42
  403.78 2439.03  414.18 2435.98  432.77 2434.76  458.12  2429.1  497.34 2424.22
  502.65 2422.79  510.67 2423.81  603.98 2434.96  614.72 2439.76  638.53 2441.32
  647.24 2444.27  663.96 2453.59  734.37 2459.91   755.1 2468.22  881.05 2490.87
  918.53 2501.09 1025.95 2518.06 1051.95 2520.68 1199.33 2551.96 1235.01  2563.5
#Mann= 3 ,-1 , 0
       0     .07       0  497.34     .04       0  510.67     .09       0
#XS Ineff= 2 , 0
       0                  629.36       0    2450
Permanent Ineff=
       F       F
#Block Obstruct= 1 ,-1
  714.49  732.062469.716
Bank Sta=497.34,510.67
Exp/Cntr=0.3,0.1

Type RM Length L Ch R = 1 ,17583.9 ,483.89,481,475.97
XS GIS Cut Line= 6
 1063519.8594989  838321.6407804 1063408.5574155  838645.6199472
 1063416.5053322  838798.6720306  1063770.296999  839188.2449475
 1064116.1407492  839414.8282809 1064277.1407493  839470.4845309
#Sta/Elev= 30
       0 2580.65  113.62 2544.69   249.8 2508.46  336.43 2500.35  345.77 2501.75
  351.23 2499.43  379.26 2496.35  410.42 2487.91  502.69 2476.52  687.94 2446.18
   698.8 2444.85  745.26 2428.28  773.99 2423.66  778.822421.865  793.75 2423.57
  848.26 2428.11   899.1 2436.64  929.72 2437.75  963.79 2445.54  988.61 2447.55
 1053.54 2458.23 1153.86 2487.27 1226.64 2503.79 1267.62 2515.93  1309.4 2522.85
 1347.27 2536.39 1388.53 2542.12 1422.86 2552.27 1517.91  2569.5 1606.46 2580.18
#Mann= 5 ,-1 , 0
       0     .09       0  502.69     .05       0  687.94     .09       0
  773.99     .04       0  793.75     .09       0
#XS Ineff= 2 , 0
       0                  925.42       0    2455
Permanent Ineff=
       F       F
#Block Obstruct= 1 ,-1
 1024.95 1046.312457.063
Bank Sta=773.99,793.75
Exp/Cntr=0.3,0.1

Type RM Length L Ch R = 1 ,17102.9 ,57.79,57,57.27
BEGIN DESCRIPTION:
surveyed section
END DESCRIPTION:
XS GIS Cut Line= 6
 1063424.6615822  838337.9949471 1063132.4428321  839051.3491141
 1063117.9011654  839176.7866141 1063220.4949155  839319.2032809
 1063801.1511657  839619.0991143 1064311.3907493  839495.5261976
#Sta/Elev= 30
       0 2573.95  101.15 2553.26  150.49 2547.72  417.41 2528.93  498.46 2527.65
   529.8 2524.35  655.74 2499.74  776.61 2467.84   789.6 2467.99  837.63 2454.48
   897.5 2446.26  958.68 2442.46 1008.58 2430.561120.472  2425.51134.023  2422.5
 1138.54  2421.41138.992    24211142.154    24201163.159  2421.51179.194  2424.3
 1233.69 2425.65 1261.28 2429.91 1336.26 2429.22 1453.13 2434.27 1590.92 2447.34
 1725.27 2463.84 1767.57 2471.49 1830.13 2493.36 2030.86  2542.6 2258.57  2584.1
#Mann= 6 ,-1 , 0
       0     .05       01134.023     .09       01138.992     .04       0
1163.159     .09       01179.194     .05       0 1725.27     .09       0
#XS Ineff= 2 , 0
       0                    1272       0    2435
Permanent Ineff=
       F       F
Bank Sta=1138.54,1163.159
Exp/Cntr=0.5,0.3

Type RM Length L Ch R = 1 ,17045.9 ,38.97,36,35.03
BEGIN DESCRIPTION:
u/s of 8012 survyed section
END DESCRIPTION:
XS GIS Cut Line= 6
 1063122.2240821  839261.6199475 1063186.7032488  839371.9011976
 1063229.7969988  839406.7032809 1063293.7032488  839449.7032809
 1063565.3282489  839615.4636977  1063584.140749   839623.828281
#Sta/Elev= 30
       0 2440.42   14.07 2438.04   24.22 2434.05   67.63 2429.08   88.81 2427.42
   109.9 2426.69 151.056  2426.9 159.268  2427.4 163.824  2426.9 181.447  2421.7
 182.286  2421.2 186.123  2420.5 210.879  2421.3 215.495  2421.9 226.944  2422.2
 239.172  2423.5  252.18  2423.8 260.632  2426.2  261.19 2427.28  290.06 2430.48
  296.03 2430.21   306.3 2430.37  337.61 2428.95  350.06 2428.84  382.22 2429.92
  390.21 2430.99  473.51 2430.45  497.66 2432.36  530.89 2437.71  599.43 2444.03
#Mann= 3 ,-1 , 0
       0     .06       0 182.286     .04       0 210.879     .06       0
#XS Ineff= 3 ,-1
       0   134.8  2428.3   249.8     305  2428.3     306  597.79 2440.47
Permanent Ineff=
       F       F       F
#Block Obstruct= 1 ,-1
  384.32  465.082440.472
Bank Sta=182.286,210.879
Exp/Cntr=0.5,0.3