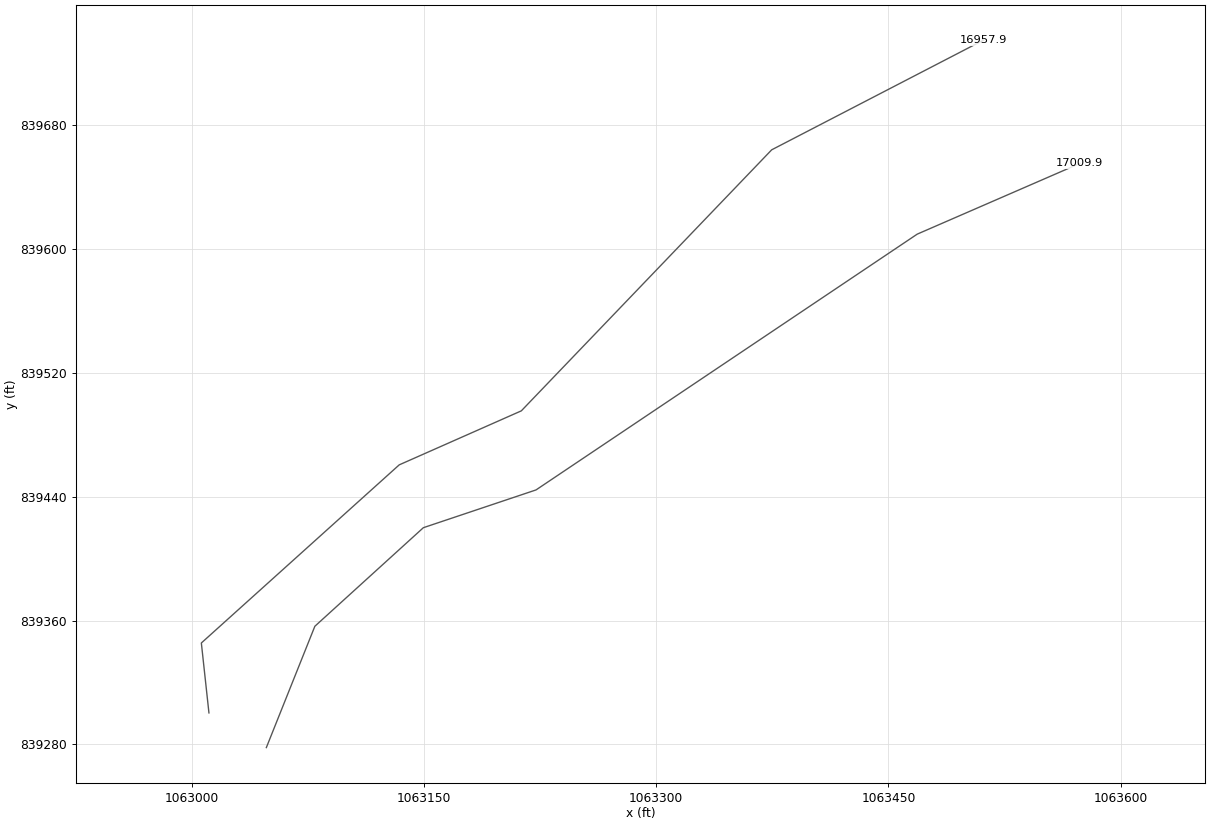
HEC-RAS study dtl_cane_crk.prj: cane creek

--- dtl_cane_crk.g01 (geometry) --- (continued)

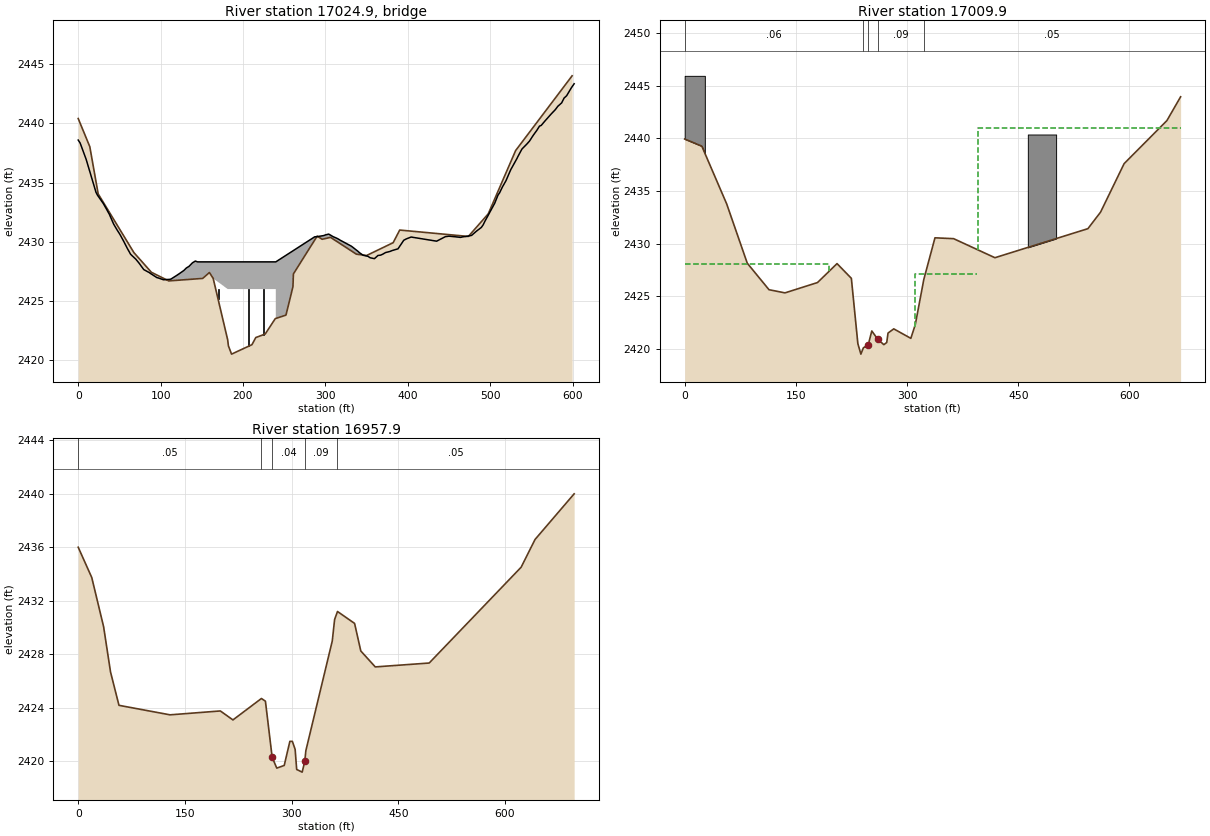
Type RM Length L Ch R = 3 ,17024.9 ,,,
BEGIN DESCRIPTION:
FBSTR 1386
END DESCRIPTION:
Bridge Culvert--1,0,-1,-1, 0
Deck Dist Width WeirC Skew NumUp NumDn MinLoCord MaxHiCord MaxSubmerge Is_Ogee
12.1,19,2.6,0, 120, 107, , , 0.95, 0, 1,1,,
       0    2.33    9.63   21.63   23.39    30.5   34.17   37.88   43.03   47.36
   50.39   54.75   59.68   63.61   70.16   70.87   71.18   73.99   79.42      80
   86.34   87.28   95.73   96.21   96.82  103.36  110.72  112.64  119.39  119.88
  121.93  122.24  128.14  131.35  134.45  138.61  142.18   144.8   144.8   239.8
   239.8  287.05  289.95   293.1  294.94  297.78   300.5  303.97   309.7  311.81
  314.39   317.2  317.99  319.37  325.83   331.2  331.84  332.42  339.61  341.29
  345.81  351.64  354.26  359.47  363.81  367.05  369.61  373.09  378.36  380.76
  384.56  386.98  388.09  395.14  398.16  404.03     435  445.58  449.71   450.3
  456.22   456.4  456.68  463.99  466.92  469.93  476.92  477.61  483.22  489.25
  491.47  493.35  505.46  509.59  511.35  514.83  519.16  524.88  525.11  525.81
  532.66  533.59  538.55  544.36  546.41   547.6  552.35  556.53  559.89  561.99
  565.84  574.37   579.2  582.04  586.72  589.72  592.84  598.27  600.85  601.92
  2438.6 2438.35 2436.97 2434.17 2433.94 2433.23 2432.78 2432.31 2431.49 2430.98
 2430.65  2430.1 2429.43 2428.94 2428.51 2428.44 2428.42 2428.18 2427.66 2427.63
 2427.39 2427.34 2426.96 2426.96 2426.95 2426.79 2426.82 2426.85 2427.15 2427.17
 2427.27 2427.28 2427.57 2427.79 2427.92 2428.22 2428.37  2428.3  2428.3  2428.3
  2428.3 2430.42 2430.43 2430.47 2430.49 2430.52 2430.59 2430.65 2430.42 2430.36
 2430.28 2430.17 2430.13 2430.08 2429.84 2429.64 2429.61 2429.58 2429.19 2429.08
 2428.86 2428.77 2428.65 2428.57 2428.84 2428.87 2428.95 2429.09 2429.18 2429.25
 2429.33 2429.38  2429.4 2430.13 2430.24  2430.4 2430.05 2430.43 2430.47 2430.47
 2430.43 2430.43 2430.43 2430.37 2430.42 2430.44 2430.53 2430.55 2430.89 2431.21
 2431.43  2431.7 2433.25 2433.96 2434.13 2434.63 2435.16 2436.08 2436.12  2436.2
 2437.06  2437.2 2437.84 2438.25 2438.41  2438.5 2439.01 2439.41 2439.78 2439.84
 2440.16 2440.83 2441.18 2441.45 2441.74 2442.15 2442.35 2442.99 2443.25 2443.36
                                                                                
                                                                                
                                                                                
                                                                    2426    2426
                                                                                
                                                                                
                                                                                
                                                                                
                                                                                
                                                                                
                                                                                
                                                                                
       0    2.33    9.63   21.63   23.39    30.5   34.17   37.88   43.03   47.36
   50.39   54.75   59.68   63.61   70.16   70.87   71.18   73.99   79.42      80
   86.34   87.28   95.73   96.21   96.82  103.36  110.72  112.64  119.39  119.88
  121.93  122.24  128.14  131.35  134.45  138.61  142.18  147.48  148.37  148.46
   204.9   204.9   299.9   299.9  339.61  341.29  345.81  351.64  354.26  359.47
  363.81  367.05  369.61  373.09  378.36  380.76  384.56  386.98  388.09  395.14
  398.16  404.03     435  445.58  449.71   450.3  456.22   456.4  456.68  463.99
  466.92  469.93  476.92  477.61  483.22  489.25  491.47  493.35  505.46  509.59
  511.35  514.83  519.16  524.88  525.11  525.81  532.66  533.59  538.55  544.36
  546.41   547.6  552.35  556.53  559.89  561.99  565.84  574.37   579.2  582.04
  586.72  589.72  592.84  598.27  600.85  601.92  668.96
  2438.6 2438.35 2436.97 2434.17 2433.94 2433.23 2432.78 2432.31 2431.49 2430.98
 2430.65  2430.1 2429.43 2428.94 2428.51 2428.44 2428.42 2428.18 2427.66 2427.63
 2427.39 2427.34 2426.96 2426.96 2426.95 2426.79 2426.82 2426.85 2427.15 2427.17
 2427.27 2427.28 2427.57 2427.79 2427.92 2428.22 2428.37 2428.66 2428.69 2428.69
  2428.2  2428.2  2428.2  2428.2 2429.19 2429.08 2428.86 2428.77 2428.65 2428.57
 2428.84 2428.87 2428.95 2429.09 2429.18 2429.25 2429.33 2429.38  2429.4 2430.13
 2430.24  2430.4 2430.05 2430.43 2430.47 2430.47 2430.43 2430.43 2430.43 2430.37
 2430.42 2430.44 2430.53 2430.55 2430.89 2431.21 2431.43  2431.7 2433.25 2433.96
 2434.13 2434.63 2435.16 2436.08 2436.12  2436.2 2437.06  2437.2 2437.84 2438.25
 2438.41  2438.5 2439.01 2439.41 2439.78 2439.84 2440.16 2440.83 2441.18 2441.45
 2441.74 2442.15 2442.35 2442.99 2443.25 2443.36 2443.95
                                                                                
                                                                                
                                                                                
                                                                                
          2425.9  2425.9
                                                                                
                                                                                
                                                                                
                                                                                
                                                                                
                                                        
Pier Skew, UpSta & Num, DnSta & Num=  ,169.8, 2 ,229.9, 2 , 0 , 0 , 0 ,,
       1       1
  2420.5    2426
       1       1
  2420.4  2425.9
Pier Skew, UpSta & Num, DnSta & Num=  ,206.8, 2 ,266.9, 2 , 0 , 0 , 0 ,,
       1       1
  2420.5    2426
       1       1
  2420.4  2425.9
Pier Skew, UpSta & Num, DnSta & Num=  ,224.8, 2 ,284.9, 2 , 0 , 0 , 0 ,,
       1       1
  2420.5    2426
       1       1
  2420.4  2425.9
BR Coef=-1 , 0 , 0 ,, 0 ,,,0.8,0,,0,
WSPro=,,,, 1 ,,,, 0 ,,,, 0 ,,,,-1 ,-1 ,-1 , 0 , 0 , 0 , 0 , 0
BC Design=,, 0 ,, 0 ,,,,,,

Type RM Length L Ch R = 1 ,17009.9 ,52.69,52,50.79
BEGIN DESCRIPTION:
d/s of 8012 surveyed section
END DESCRIPTION:
XS GIS Cut Line= 6
  1063048.036582  839277.9116142 1063079.3803321  839356.2970309
 1063149.4949154  839419.9949476 1063222.2969988  839444.4011976
 1063468.6094989  839609.6824477  1063573.703249   839655.359531
#Sta/Elev= 30
       0 2439.94   23.12 2439.26   56.67 2433.77   84.42 2428.14  113.75 2425.62
  135.29 2425.32 179.148  2426.3 205.505  2428.1 224.838  2426.7 233.601  2420.5
 237.682  2419.5 241.027  2420.1  247.65  2420.4 252.399  2421.7 260.561  2420.9
 268.655  2420.4 272.535  2420.6 274.274  2421.5 282.034  2421.9 305.047    2421
 311.067  2422.3 322.573  2426.6 337.625 2430.55  362.74 2430.47  418.49 2428.66
   543.9 2431.42  560.98 2432.99  592.77  2437.6  650.49 2441.69  668.96 2443.95
#Mann= 5 ,-1 , 0
       0     .06       0 241.027     .09       0  247.65     .04       0
 260.561     .09       0 322.573     .05       0
#XS Ineff= 3 ,-1
       0   194.9 2428.08     310     394 2427.08     396  668.96    2441
Permanent Ineff=
       F       F       F
#Block Obstruct= 2 ,-1
  462.86  501.032440.367       0   27.192445.941
Bank Sta=247.65,260.561
Exp/Cntr=0.5,0.3

Type RM Length L Ch R = 1 ,16957.9 ,809.61,861,895.56
XS GIS Cut Line= 6
  1063010.942832  839300.3178642  1063006.036582  839345.4949475
 1063133.9011654  839460.5991143 1063212.7969988  839495.4949476
 1063374.5678322  839664.1616144 1063511.6199156  839735.1511977
#Sta/Elev= 30
       0    2436   19.04 2433.74   35.71 2430.06   45.44 2426.68    57.3 2424.19
  129.06 2423.48   199.8 2423.77 217.501  2423.1 257.515  2424.7 263.162  2424.5
 272.643  2420.3 279.126  2419.5 289.583  2419.7  297.53  2421.5 301.015  2421.5
 304.919  2420.9  307.08  2419.4 314.818  2419.2 318.443    2420 319.977  2420.8
 357.133    2429  360.41  2430.6 364.453  2431.2  388.48 2430.31  397.23 2428.25
  417.56 2427.06  493.36 2427.35  622.63 2434.51  642.15 2436.58  697.12 2439.99
#Mann= 5 ,-1 , 0
       0     .05       0 257.515     .09       0 272.643     .04       0
 318.443     .09       0 364.453     .05       0
Bank Sta=272.643,318.443
Exp/Cntr=0.3,0.1