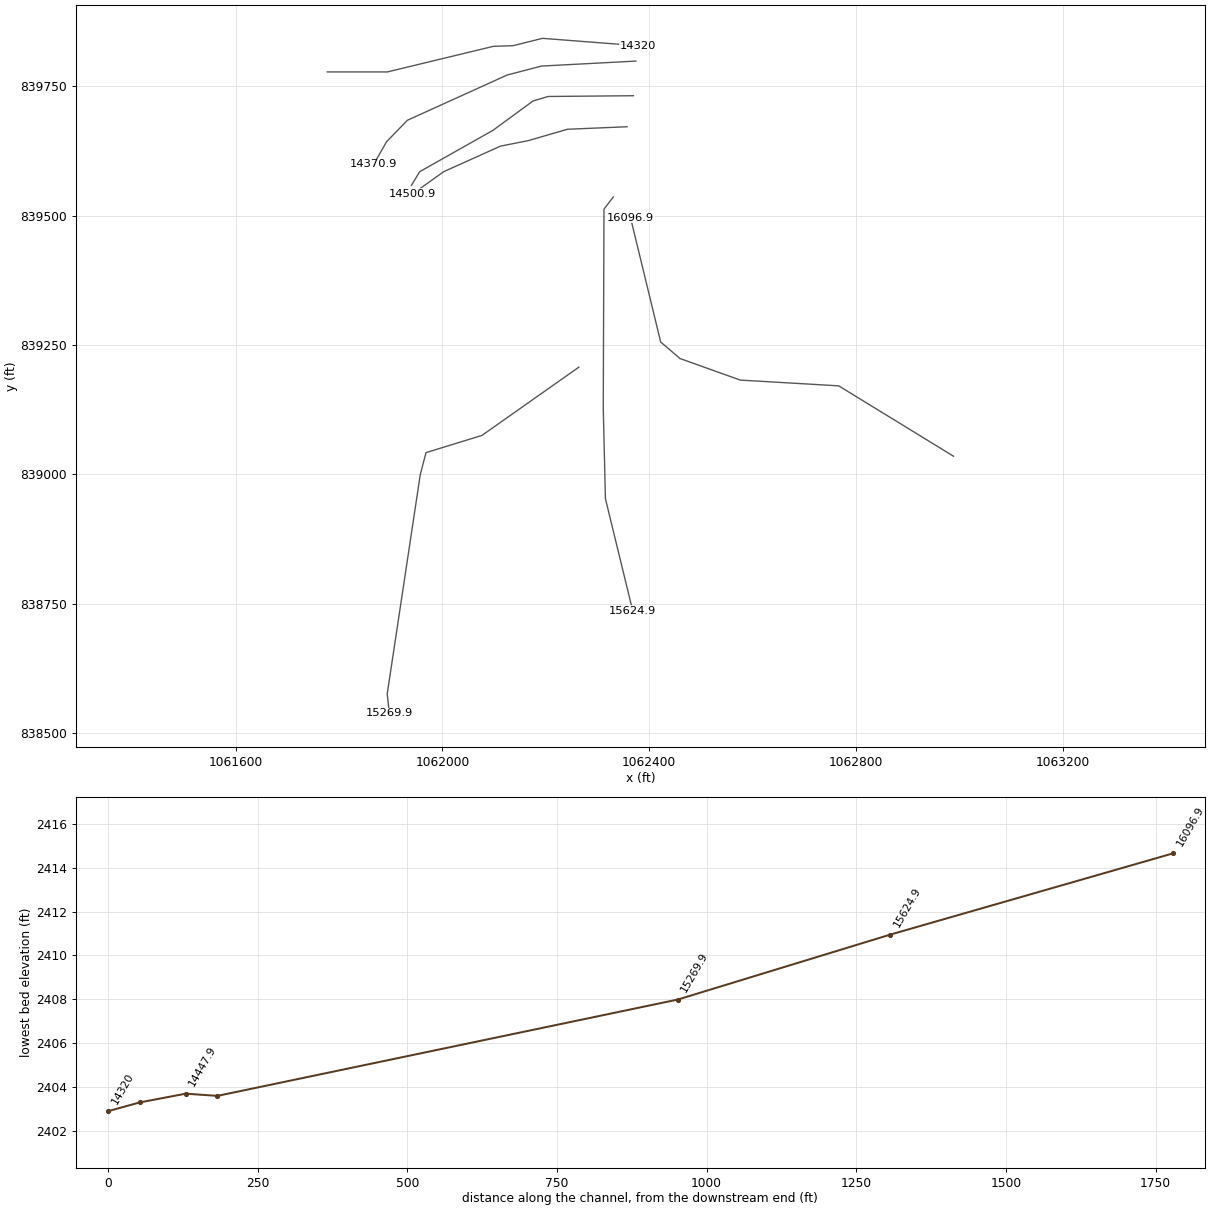
HEC-RAS study dtl_cane_crk.prj: cane creek

--- dtl_cane_crk.g01 (geometry) --- (continued)

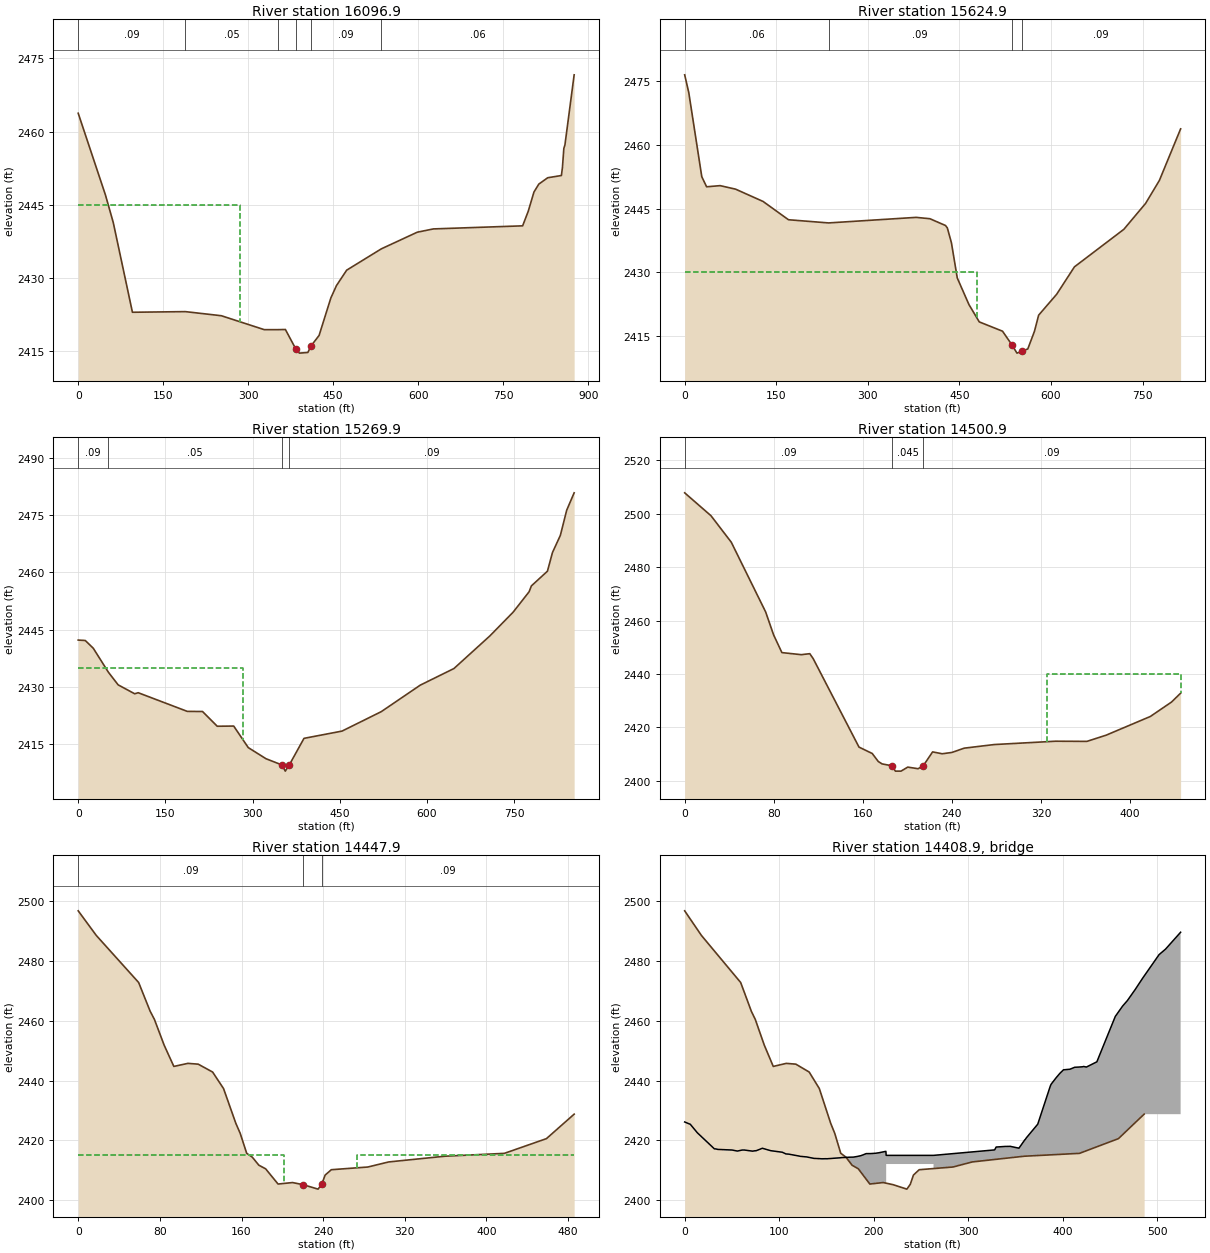
Type RM Length L Ch R = 1 ,16096.9 ,497.37,472,453.82
XS GIS Cut Line= 6
 1062988.7136653  839035.0782807 1062766.5365819  839171.1616141
 1062576.2969985  839182.2761975 1062459.6615818  839223.9324475
 1062422.1615818  839255.8699475 1062363.8386651  839496.0991143
#Sta/Elev= 30
       0 2463.78   47.97 2447.08   61.87 2441.39   95.69 2423.02  189.04 2423.15
  252.61 2422.31  328.24 2419.46  352.86 2419.46  365.61 2419.49  384.25 2415.44
  390.25 2414.65  405.19 2414.78  411.06 2416.16  425.05 2418.27  445.84 2425.95
   455.7 2428.48  473.74 2431.64  534.96 2436.01  598.35 2439.42  626.88 2440.09
  784.26 2440.72  794.18 2443.71  804.18 2447.63  812.82 2449.27   828.5 2450.57
  852.66 2451.03   854.5 2452.65  856.97 2456.58  858.91  2457.3  875.17 2471.65
#Mann= 6 ,-1 , 0
       0     .09       0  189.04     .05       0  352.86     .09       0
  384.25     .04       0  411.06     .09       0  534.96     .06       0
#XS Ineff= 2 , 0
       0     285    2445               0
Permanent Ineff=
       F       F
Bank Sta=384.25,411.06
Exp/Cntr=0.3,0.1

Type RM Length L Ch R = 1 ,15624.9 ,358.7,355,345.46
XS GIS Cut Line= 5
 1062330.5157484  839536.3699476  1062312.463665  839512.7553643
 1062311.0782484  839128.1199474  1062315.244915  838953.1511974
 1062368.0053317  838736.5261973
#Sta/Elev= 30
       0 2476.55    6.74 2472.35   28.01 2452.54    35.9 2450.16   58.07 2450.43
   83.39  2449.6  128.44  2446.7  170.04 2442.39  235.79 2441.64  379.05 2442.95
  401.71 2442.63  427.25 2441.03  430.23 2440.47  436.95 2436.95   446.5 2428.67
  465.59 2422.41  482.54 2418.31  520.64 2416.12  535.66 2412.97  544.31 2410.95
  552.39 2411.39  562.03 2411.94  572.95  2416.1  579.77 2419.89  609.33 2424.83
  638.45 2431.29  719.33 2440.13  754.98 2446.24  777.58 2451.66  812.34 2463.81
#Mann= 4 ,-1 , 0
       0     .06       0  235.79     .09       0  535.66     .04       0
  552.39     .09       0
#XS Ineff= 2 , 0
       0  478.39    2430               0
Permanent Ineff=
       F       F
Bank Sta=535.66,552.39
Exp/Cntr=0.3,0.1

Type RM Length L Ch R = 1 ,15269.9 ,794.4,769,737.42
XS GIS Cut Line= 6
 1062263.8594983  839207.2657808 1062076.4011649  839075.3491141
 1061968.0886649  839042.0261974 1061956.9844982   838998.974114
 1061893.1094982  838575.4532805 1061897.2761648  838537.9636972
#Sta/Elev= 30
       0  2442.3   12.13 2442.19   25.93 2440.16   51.89 2433.89   68.72 2430.57
   97.18 2428.24  103.17 2428.52  187.63 2423.63  213.82  2423.6  239.12 2419.74
  267.46 2419.79   292.5 2414.15  322.97 2411.24   350.6 2409.59  356.17 2407.99
  362.99 2409.59  388.36 2416.57  453.76 2418.47  521.16 2423.55  588.34  2430.5
  646.28 2434.85  708.15  2443.4  748.11 2449.61  775.71 2454.98  779.44 2456.48
  807.09 2460.33  815.75 2465.22  829.31 2469.71   840.2 2476.29  853.04 2480.85
#Mann= 4 ,-1 , 0
       0     .09       0   51.89     .05       0   350.6    .045       0
  362.99     .09       0
#XS Ineff= 2 , 0
       0  284.18    2435               0
Permanent Ineff=
       F       F
Bank Sta=350.6,362.99
Exp/Cntr=0.3,0.1

Type RM Length L Ch R = 1 ,14500.9 ,50.28,53,60.96
XS GIS Cut Line= 6
 1062357.1303317  839672.0991144 1062241.7969983   839667.203281
 1062166.5990816  839645.4011977 1062112.2969983  839634.5991143
 1062002.2449149   839585.140781 1061942.3178315  839542.2553643
#Sta/Elev= 30
       0 2507.82   23.65 2499.23   41.85 2489.32   72.71 2463.21   79.85 2454.62
   87.29 2447.99  104.69 2447.21  112.36 2447.58 115.424  2445.7 156.526  2412.6
 168.416  2410.2 173.849  2407.2 177.278  2406.3 186.184  2405.6 189.168  2403.6
 194.244  2403.6   200.3  2405.1 209.652  2404.5 214.372  2405.7  222.61  2410.8
 231.249  2410.1 240.022  2410.6 250.977  2412.2  277.92 2413.55  333.11  2414.8
  361.18 2414.74  378.48 2417.07   418.1 2424.06  437.15 2429.47  445.31 2432.79
#Mann= 3 ,-1 , 0
       0     .09       0 186.184    .045       0 214.372     .09       0
#XS Ineff= 2 , 0
       0                     325       0    2440
Permanent Ineff=
       F       F
Bank Sta=186.184,214.372
Exp/Cntr=0.5,0.3

Type RM Length L Ch R = 1 ,14447.9 ,83.57,77,68.68
BEGIN DESCRIPTION:
u/s of 5396 surveyed section
END DESCRIPTION:
XS GIS Cut Line= 6
 1062369.4740817  839732.0366144  1062204.401165  839730.5991144
 1062175.0990816   839721.797031 1062097.4949149  839664.9949477
 1061955.8282482   839585.140781 1061939.9636649   839558.703281
#Sta/Elev= 30
       0 2496.85    17.7 2488.62   59.23 2472.86    70.5 2463.24   74.66 2460.52
   84.17 2451.92    93.7 2444.77  107.45 2445.79  117.56 2445.53  131.69 2442.89
  142.41 2437.36  154.46 2425.71  158.71 2422.39 165.078  2415.7 170.569  2414.4
 177.032  2411.7 183.641  2410.5 195.839  2405.4  209.98  2405.9 220.282  2405.2
 235.006  2403.7 238.602  2405.3 241.956  2408.4  248.03  2410.2 283.796  2411.1
  304.23  2412.8  359.11 2414.71  417.57 2415.67  458.79  2420.6  485.95 2428.79
#Mann= 3 ,-1 , 0
       0     .09       0 220.282     .04       0 238.602     .09       0
#XS Ineff= 2 , 0
       0     202    2415     273       0    2415
Permanent Ineff=
       F       F
Bank Sta=220.282,238.602
Exp/Cntr=0.5,0.3

Type RM Length L Ch R = 3 ,14408.9 ,,,
BEGIN DESCRIPTION:
fbstr 1389
END DESCRIPTION:
Bridge Culvert--1,0,-1,-1, 0
Deck Dist Width WeirC Skew NumUp NumDn MinLoCord MaxHiCord MaxSubmerge Is_Ogee
14.6,57.5,2.6,0, 84, 85, , , 0.95, 0, 1,1,,
       0    4.05    5.91   13.31   31.41   32.83   35.21   50.18   55.71    60.9
   63.03   71.83   74.72   75.41   82.19   90.94  103.24  107.03  108.38  110.07
  120.39  122.46  129.04  136.74  141.51   141.7  145.22  149.37  150.44  163.61
  164.19   165.6  174.49  178.22  182.43  186.33  189.09  191.93  196.64  201.93
  205.48   211.2  212.82 213.105 213.105 263.205 263.205  327.43  328.03   329.4
  337.91  338.51  343.39  344.22   344.4  347.42  353.42  353.57  359.79  360.13
  361.24  373.42  386.68  387.54  392.61  396.62  400.63  407.43  412.52  416.44
  420.93  421.94  424.88  435.97  436.36  436.92  455.44  463.19  468.23  476.59
  484.49  501.77  508.58  524.54
 2426.18 2425.63 2425.42 2422.59 2417.18 2417.16 2416.99 2416.79 2416.44 2416.79
 2416.79 2416.41 2416.56 2416.53 2417.38 2416.57 2416.05 2415.48 2415.45 2415.41
 2414.81 2414.67 2414.48 2413.99 2413.92 2413.92 2413.85 2413.88 2413.86 2414.17
 2414.18 2414.24 2414.39 2414.41 2414.63  2414.9 2415.22 2415.59  2415.6 2415.71
 2415.88 2416.25 2416.35    2415    2415    2415    2415 2416.82 2416.93 2417.79
 2417.97 2417.99 2418.01 2418.03 2418.02 2417.82 2417.41 2417.42 2420.23 2420.27
 2420.82 2425.44 2438.18  2438.8 2440.88 2442.39 2443.64 2443.83 2444.49 2444.55
 2444.66 2444.76 2444.56 2446.32 2446.64 2447.08 2461.51 2464.98 2466.81 2470.57
 2474.36  2482.2 2484.03 2489.69
                                                                                
                                                                                
                                                                                
                                                                                
                                  2412.1  2412.1
                                                                                
                                                                                
                                                                                
                                
       0    4.05    5.91   13.31   31.41   32.83   35.21   50.18   55.71    60.9
   63.03   71.83   74.72   75.41   82.19   90.94  103.24  107.03  108.38  110.07
  120.39  122.46  129.04  136.74  141.51   141.7  145.22  149.37  150.44  163.61
  164.19   165.6  174.49  178.22  182.43  186.33  189.09  191.93  196.64  201.93
  205.48   211.2  212.82 213.105 213.105 263.205 263.205  327.43  328.03   329.4
  337.91  338.51  343.39  344.22   344.4  347.42  353.42  353.57  359.79  360.13
  361.24  373.42  386.68  387.54  392.61  396.62  400.63  407.43  412.52  416.44
  420.93  421.94  424.88  435.97  436.36  436.92  455.44  463.19  468.23  476.59
  484.49  501.77  508.58  524.54  573.43
 2426.18 2425.63 2425.42 2422.59 2417.18 2417.16 2416.99 2416.79 2416.44 2416.79
 2416.79 2416.41 2416.56 2416.53 2417.38 2416.57 2416.05 2415.48 2415.45 2415.41
 2414.81 2414.67 2414.48 2413.99 2413.92 2413.92 2413.85 2413.88 2413.86 2414.17
 2414.18 2414.24 2414.39 2414.41 2414.63  2414.9 2415.22 2415.59  2415.6 2415.71
 2415.88 2416.25 2416.35    2415    2415    2415    2415 2416.82 2416.93 2417.79
 2417.97 2417.99 2418.01 2418.03 2418.02 2417.82 2417.41 2417.42 2420.23 2420.27
 2420.82 2425.44 2438.18  2438.8 2440.88 2442.39 2443.64 2443.83 2444.49 2444.55
 2444.66 2444.76 2444.56 2446.32 2446.64 2447.08 2461.51 2464.98 2466.81 2470.57
 2474.36  2482.2 2484.03 2489.69 2429.77
                                                                                
                                                                                
                                                                                
                                                                                
                                  2412.1  2412.1
                                                                                
                                                                                
                                                                                
                                        
BR Coef=-1 , 0 , 0 ,, 0 ,,,0.8,0,,0,
WSPro=,,,, 1 ,,,, 0 ,,,, 0 ,,,,-1 ,-1 ,-1 , 0 , 0 , 0 , 0 , 0
BC Design=,, 0 ,, 0 ,,,,,,

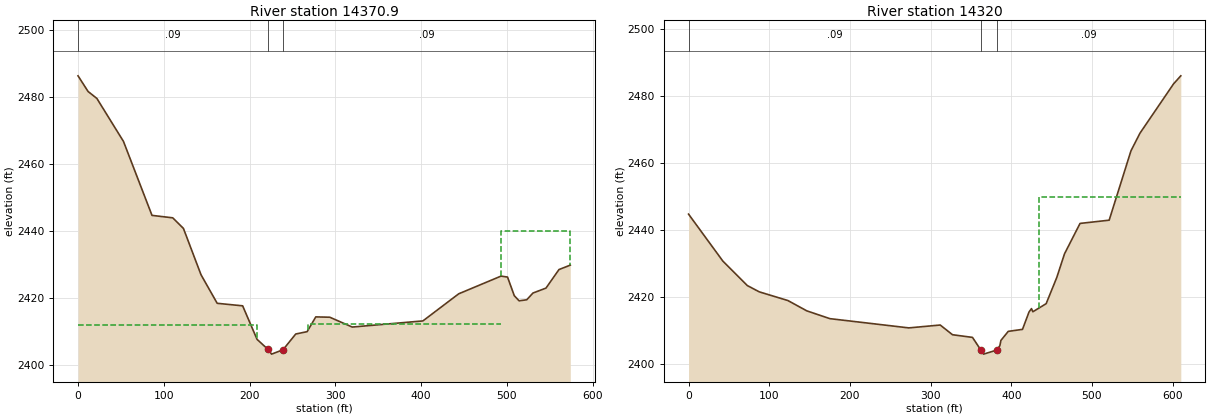
Type RM Length L Ch R = 1 ,14370.9 ,56.99,53,55.67
BEGIN DESCRIPTION:
d/s of 5396 surveyed section
END DESCRIPTION:
XS GIS Cut Line= 6
 1062374.1719984  839799.0157811 1062191.7032483  839789.4011977
 1062125.2032483  839772.0991144 1061932.2344982   839684.640781
 1061891.7969982  839643.0261977 1061867.1719982  839599.6511977
#Sta/Elev= 30
       0 2486.26    11.7  2481.6      22 2479.51      53  2466.7   86.24 2444.66
  110.41 2443.93  122.87 2440.78   143.4 2426.96  162.25 2418.45 191.916  2417.7
 208.732  2407.7  221.53  2404.7 225.662  2403.3 238.977  2404.6 253.841  2409.3
 267.099    2410 277.199  2414.4 293.498  2414.3  319.71 2411.37  402.08  2413.2
  443.82 2421.28  493.18 2426.56  500.74 2426.27  508.62 2420.72  514.22 2419.19
  523.14  2419.5  530.37 2421.51  545.56 2422.98  560.71 2428.51  573.91 2429.83
#Mann= 3 ,-1 , 0
       0     .09       0  221.53    .045       0 238.977     .09       0
#XS Ineff= 3 ,-1
       0  208.73    2412   268.2  493.18  2412.2   493.2  573.43    2440
Permanent Ineff=
       F       F       F
Bank Sta=221.53,238.977
Exp/Cntr=0.5,0.3

Type RM Length L Ch R = 1 ,14320   ,15.49,14321.19,19.05
XS GIS Cut Line= 6
 1061777.0574148  839778.0574477 1061893.5469982  839778.0574477
 1062098.2969983  839827.4949478 1062136.5990816  839828.7970311
 1062193.5990816  839842.9949478 1062377.7657484  839828.7241144
#Sta/Elev= 30
       0 2444.74   42.62 2430.68   72.81  2423.4   87.69 2421.51  123.22 2418.91
  146.59 2415.83  175.27  2413.5  273.08 2410.74 311.963  2411.6 327.155  2408.7
 351.927  2407.9 362.116  2404.2 365.716  2402.9 381.823  2404.1  385.85  2405.4
 387.193    2407 396.284  2409.7 413.917  2410.3 422.031  2415.5 425.082  2416.5
  426.79 2415.56  443.26 2417.98   456.4 2425.79  466.01 2432.88  485.25 2441.96
  521.35 2442.93  548.38 2463.66  559.51 2468.92  601.15 2483.66  610.14 2486.07
#Mann= 3 ,-1 , 0
       0     .09       0 362.116     .04       0 381.823     .09       0
#XS Ineff= 2 , 0
       0                     434       0    2450
Permanent Ineff=
       F       F
Bank Sta=362.116,381.823
Exp/Cntr=0.5,0.3
Stream Node=river           ,main            , 0 , 0 ,Upstream end
Stream Node=river           ,main            , 0 , 1 ,Downstream end

Chan Stop Cuts=-1
Use User Specified Reach Order=0
User Specified Reach Order=river           ,main