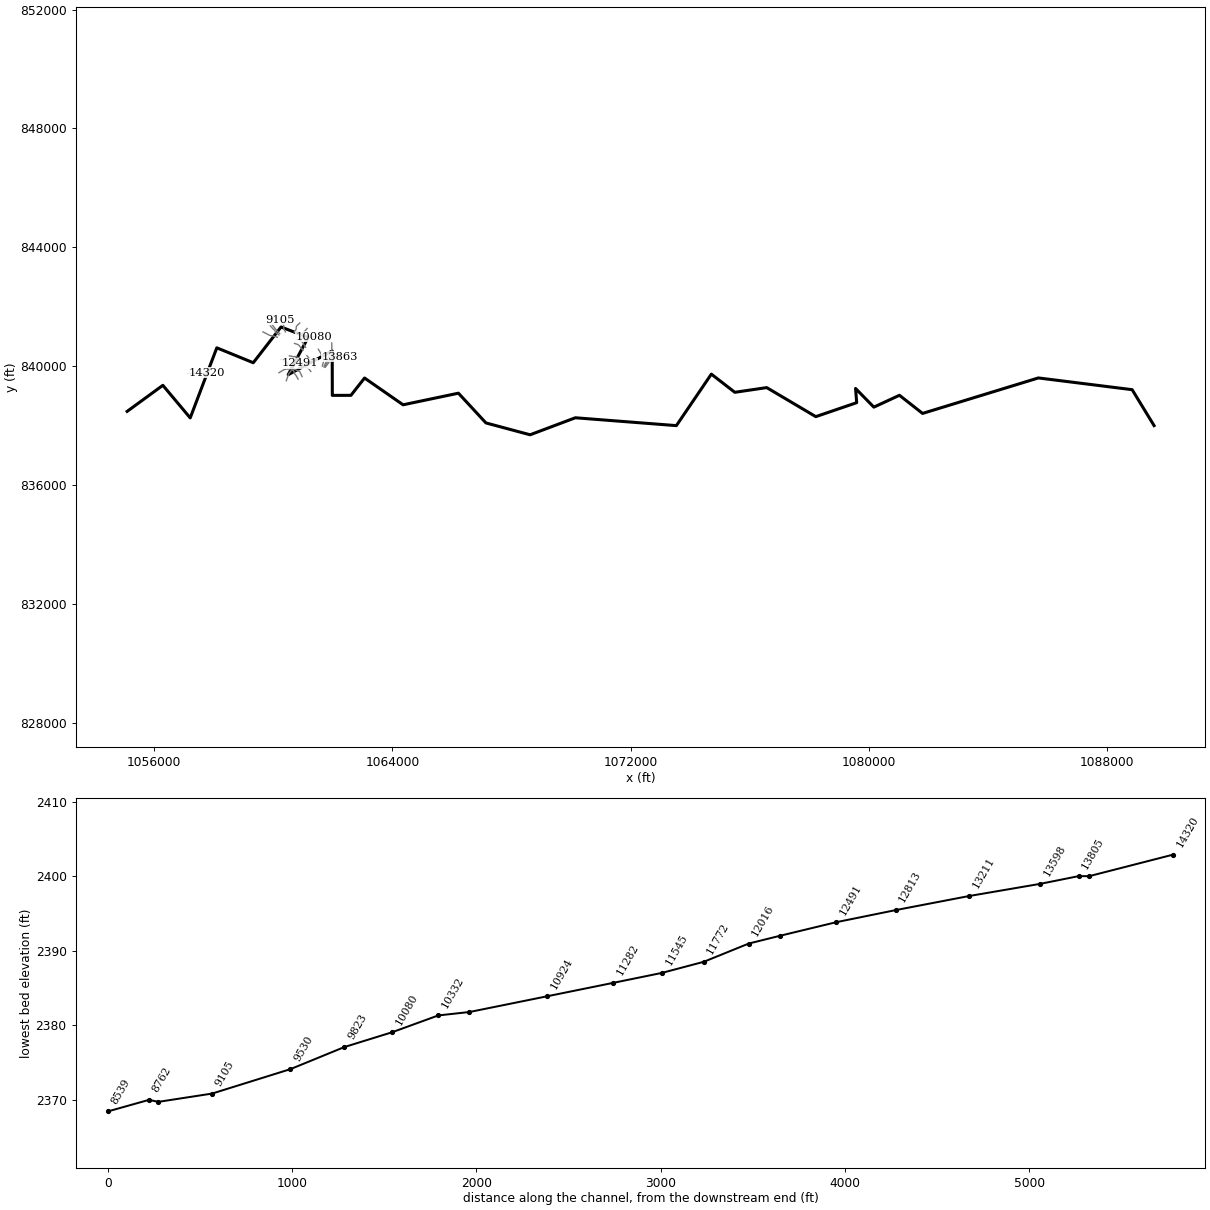
--- lds_cane_crk_lower.prj (project) ---

Proj Title=Cane Creek Limited Detail Study
Current Plan=p02
Default Exp/Contr=0.3,0.1
English Units
Geom File=g01
Flow File=f02
Plan File=p02
Y Axis Title=Elevation
X Axis Title(PF)=Main Channel Distance
X Axis Title(XS)=Station
BEGIN DESCRIPTION:
Cane Creek
END DESCRIPTION:
DSS Export Rating Curves= 0
DSS Export Rating Curve Sorted= 0
DSS Export Volume Flow Curves= 0
DXF OffsetX= 0
DXF OffsetY= 0
DXF ScaleX= 1
DXF ScaleY= 10

--- lds_cane_crk_lower.p02 (plan) ---

Plan Title=Floodway Run
Program Version=3.13
Short Identifier=Multiple
Geom File=g01
Flow File=f02
Subcritical Flow
K Sum by GR= 0
Std Step Tol= 0.01
Critical Tol= 0.01
Num of Std Step Trials= 20
Max Error Tol= 0.3
Flow Tol Ratio= 0.001
Split Flow NTrial= 30
Split Flow Tol= 0.02
Split Flow Ratio= 0.02
Log Output Level= 0
Friction Slope Method= 1
Unsteady Friction Slope Method= 2
Unsteady Bridges Friction Slope Method= 1
Parabolic Critical Depth
Global Vel Dist= 0 , 0 , 0
Global Log Level= 0
CheckData=True
Encroach Param=-1 ,7,7, 2
Encroach River=Cane Creek
Encroach Reach=Reach-1
Encroach Node=14320
       4      .7
Encroach Node=13863
       4      .7
Encroach Node=13805
       1    4900  5041.5
Encroach Node=13598
       1    4900  5018.9
Encroach Node=13211
       1  4870.7    5035
Encroach Node=12813
       1    4860  5045.7
Encroach Node=12491
       1  4942.6    5097
Encroach Node=12185
       1    4845  5028.1
Encroach Node=12016
       1    4955    5073
Encroach Node=11772
       1    4974    5080
Encroach Node=11545
       1    4958    5053
Encroach Node=11282
       1    4955    5078
Encroach Node=10924
       1    4935    5028
Encroach Node=10501
       1    4950    5065
Encroach Node=10332
       1    4970    5070
Encroach Node=10080
       1    4905    5032
Encroach Node=9823
       1    4940    5030
Encroach Node=9530
       4      .7
Encroach Node=9105
       1    4968    5100
Encroach Node=8814
       1    4880    5022
Encroach Node=8762
       1    4886  5043.8
Encroach Node=8539
       1    4905    5073
Encroach Node=8139
       1    4965    5125
Encroach Node=7724
       1    4954    5100
Encroach Node=7409
       4      .7
Encroach Node=7159
       1    4967    5060
Encroach Node=6656
       4      .7
Encroach Node=6597
       1    4845    5032
Encroach Node=6460
       1    4875    5072
Encroach Node=6238
       1    4950    5072
Encroach Node=6191
       1    4950    5060
Encroach Node=5796
       1    4950    5030
Encroach Node=5519
       1    4975    5085
Encroach Node=5235
       4      .7
Encroach Node=4895
       4      .7
Encroach Node=4781
       1 4970.14  5055.9
Encroach Node=4297
       4      .7
Encroach Node=3873
       1    4890    5035
Encroach Node=3802
       1  4961.5    5046
Encroach Node=3730
       1    4910    5050
Encroach Node=3048
       1    4925    5080
Encroach Node=2511
       1    4940    5085
Encroach Node=2264
       1 4953.14 5038.91
Encroach Node=2207
       1    4950 5034.64
Encroach Node=1798
       1    4925    5013
Encroach Node=1491
       1    4951    5017
Encroach Node=1107
       1    4981    5040
Encroach Node=823
       1  4935.3 5023.65
Encroach Node=531
       1  4963.4  5043.3
Encroach Node=295
       1  4934.4    5110
Encroach Node=213
       1    4924    5076
Encroach Node=161
       4      .7
BEGIN DESCRIPTION:
Multiple Run
END DESCRIPTION:
Computation Interval=1HOUR
Output Interval=1HOUR
Run HTab= 0
Run UNet= 0
Run PostProcess= 0
UNET Theta= 1
UNET Theta Warmup= 1
UNET ZTol= 0.02
UNET ZSATol= 0.05
UNET MxIter= 20
UNET MaxInSteps= 0
UNET DtIC= 0
UNET DtMin= 0
UNET MaxCRTS= 20
UNET WFStab= 2
UNET SFStab= 1
UNET WFX= 1
UNET SFX= 1
UNET DSS MLevel= 4
UNET DZMax Abort= 100
UNET Convert EG Bridges=-1
UNET Use Existing IB Tables=-1
UNET Froude Reduction=False
UNET Froude Limit= 1
UNET Froude Power= 10
Instantaneous Interval=1HOUR
Write IC File= 0
Echo Input=False
Echo Output=False
Write Detailed= 0
Detailed Automatic Start=False, 10

--- lds_cane_crk_lower.f02 (steady flow) ---

Flow Title=Floodway
Program Version=3.13
Number of Profiles= 2
Profile Names=100-year,100-FW
River Rch & RM=Cane Creek,Reach-1         ,14320
    7390    7390
River Rch & RM=Cane Creek,Reach-1         ,13863
    7480    7480
River Rch & RM=Cane Creek,Reach-1         ,6460
    8200    8200
River Rch & RM=Cane Creek,Reach-1         ,3048
    8850    8850
Boundary for River Rch & Prof#=Cane Creek,Reach-1         , 1
Up Type= 0
Dn Type= 3
Dn Slope=0.019
Boundary for River Rch & Prof#=Cane Creek,Reach-1         , 2
Up Type= 0
Dn Type= 3
Dn Slope=0.019
DSS Import GetInterval= 0
DSS Import GetPeak= 0
DSS Import FillOption= 0

--- lds_cane_crk_lower.g01 (geometry) ---

Geom Title=Existing Conditions
Program Version=3.13

River Reach=Cane Creek      ,Reach-1
Reach XY= 30
       1089579.7       837995.46      1088842.98       839205.26
      1085693.37       839600.03      1081804.28        838405.7
      1081027.61       839016.45      1080167.97       838617.39
       1079553.9        839245.7      1079591.83       838767.67
      1078218.48       838297.25      1076570.71       839274.78
      1075498.34       839116.71      1074710.49       839728.77
      1073535.68       837995.01       1070142.3       838259.48
      1068623.31       837686.49      1067140.32       838085.23
      1066215.99        839086.9       1064356.7       838696.02
      1063062.88       839597.66      1062605.92       839014.45
      1061980.26        839013.6      1061976.91       840508.55
      1060498.45        839709.4      1061168.12       840964.83
      1060257.88       841314.83      1059325.05       840111.92
      1058100.92       840613.96      1057207.84       838254.29
      1056288.97       839351.95      1055089.25       838474.54

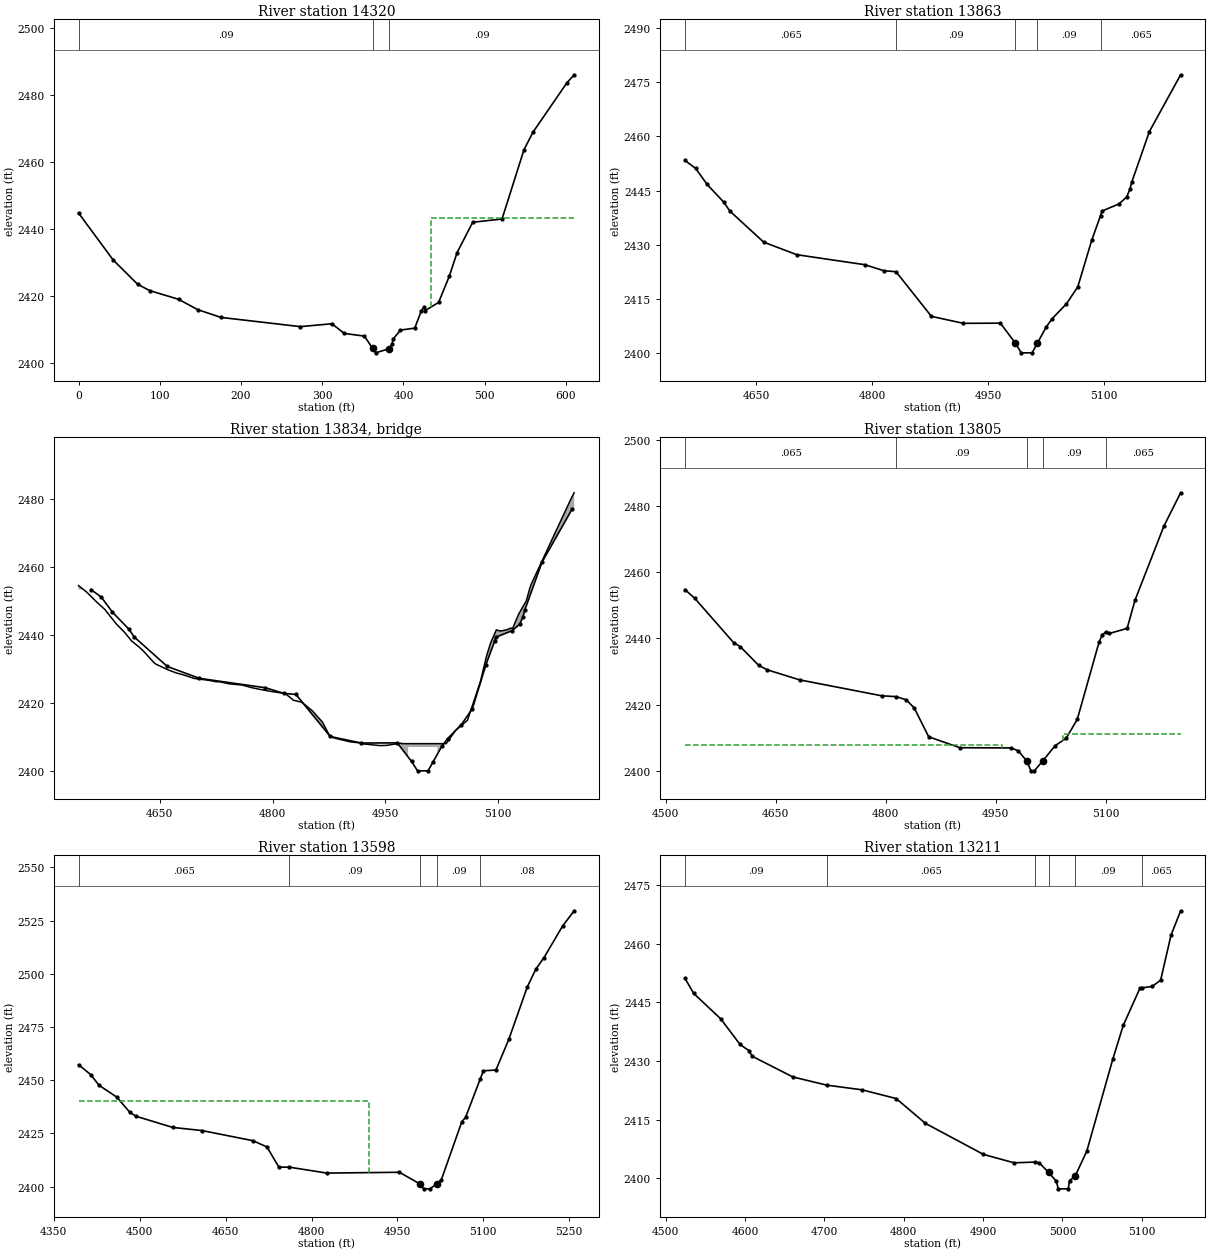
Type RM Length L Ch R = 1 ,14320   ,457,457,457
BEGIN DESCRIPTION:
XS 58
END DESCRIPTION:
XS GIS Cut Line= 2
 1057143.0400977       839778.36 1057753.1379303       839778.36
#Sta/Elev= 30
       0 2444.74   42.62 2430.68   72.81  2423.4   87.69 2421.51  123.22 2418.91
  146.59 2415.83  175.27  2413.5  273.08 2410.74 311.963  2411.6 327.155  2408.7
 351.927  2407.9 362.116  2404.2 365.716  2402.9 381.823  2404.1  385.85  2405.4
 387.193    2407 396.284  2409.7 413.917  2410.3 422.031  2415.5 425.082  2416.5
  426.79 2415.56  443.26 2417.98   456.4 2425.79  466.01 2432.88  485.25 2441.96
  521.35 2442.93  548.38 2463.66  559.51 2468.92  601.15 2483.66  610.14 2486.07
#Mann= 3 ,-1 , 0
       0     .09       0 362.116     .04       0 381.823     .09       0
#XS Ineff= 2 , 0
       0                     434       0  2443.3
Permanent Ineff=
       F       F
Bank Sta=362.116,381.823
Exp/Cntr=0.5,0.3

Type RM Length L Ch R = 1 ,13863   ,58,58,58
BEGIN DESCRIPTION:
XS 57
END DESCRIPTION:
XS GIS Cut Line= 6
      1061745.71       839957.71      1061880.84       840146.81
      1061913.02       840220.22       1061963.3       840264.47
      1062076.94       840267.49      1062216.73       840314.75
#Sta/Elev= 30
  4558.2 2453.33    4572 2451.13  4586.8 2446.69  4608.5 2441.74  4616.1 2439.33
  4659.9  2430.7  4702.7 2427.21  4790.5 2424.44  4815.2 2422.78  4831.1 2422.48
  4876.8 2410.11  4918.1 2408.18    4966 2408.23  4985.1 2402.75    4993    2400
    5007    2400  5013.8 2402.69  5025.3  2407.2    5033 2409.48  5051.4 2413.61
    5066 2418.28  5084.1 2431.24  5095.5 2438.07  5097.4 2439.32  5119.3 2441.28
  5129.2  2443.2  5133.3 2445.29  5135.8 2447.31  5158.6 2461.35    5199 2477.09
#Mann= 5 ,-1 , 0
  4558.2    .065       0  4831.1     .09       0  4985.1     .05       0
  5013.8     .09       0  5095.5    .065       0
#XS Ineff= 2 , 0
       0  4958.5 2407.76  5041.5       0 2411.21
Permanent Ineff=
       F       F
Bank Sta=4985.1,5013.8
Exp/Cntr=0.5,0.3

Type RM Length L Ch R = 3 ,13834   ,,,
BEGIN DESCRIPTION:
XS 56 TOR
Structure ID: XS 56
Approximate Survey Structure
END DESCRIPTION:
Bridge Culvert--1,0,-1,-1, 0
Deck Dist Width WeirC Skew NumUp NumDn MinLoCord MaxHiCord MaxSubmerge Is_Ogee
22,14,3,0, 60, 60, , , , 0, 1,1,,
  4541.7  4552.9    4567  4576.7    4592  4603.1  4612.5  4621.4  4627.6  4642.7
  4645.2  4660.7  4671.7  4680.6  4695.9  4715.5  4724.5    4730  4742.6  4759.4
  4772.2  4781.6  4798.4  4816.7    4828  4838.7  4852.9  4866.3  4876.7  4884.6
  4902.8  4916.2  4919.4  4943.6  4952.3  4968.8  4971.5  4971.9  4980.5  4980.5
  5019.5  5019.5  5031.1  5043.8  5059.5  5076.4  5077.3  5084.8  5090.2  5097.9
  5103.3  5111.5    5117  5119.6  5127.7  5137.9  5142.2  5144.4  5196.8  5201.5
 2454.51 2452.52 2449.42 2447.49 2443.21 2440.72 2438.18  2436.6 2435.36  2431.7
 2431.33 2429.73 2428.81 2428.28 2427.18 2426.62 2426.23 2426.18 2425.58 2425.25
 2424.47 2424.03 2423.34 2422.76 2420.75  2420.2 2417.68 2414.37 2410.02 2409.51
 2408.56 2408.22 2407.95 2407.42  2407.5 2408.11  2408.1    2408    2408    2408
    2408    2408    2408 2411.94 2414.89 2426.06 2426.81 2433.73 2437.58 2441.47
 2441.12 2441.47    2442  2441.9 2446.15 2450.06 2453.54 2454.95 2479.79  2481.8
    2380    2380    2380    2380    2380    2380    2380    2380    2380    2380
    2380    2380    2380    2380    2380    2380    2380    2380    2380    2380
    2380    2380    2380    2380    2380    2380    2380    2380    2380    2380
    2380    2380    2380    2380    2380    2380    2380    2380    2380    2407
    2407    2380    2380    2380    2380    2380    2380    2380    2380    2380
    2380    2380    2380    2380    2380    2380    2380    2380    2380    2380
  4541.7  4552.9    4567  4576.7    4592  4603.1  4612.5  4621.4  4627.6  4642.7
  4645.2  4660.7  4671.7  4680.6  4695.9  4715.5  4724.5    4730  4742.6  4759.4
  4772.2  4781.6  4798.4  4816.7    4828  4838.7  4852.9  4866.3  4876.7  4884.6
  4902.8  4916.2  4919.4  4943.6  4952.3  4968.8  4971.5  4971.9  4980.5  4980.5
  5019.5  5019.5  5031.1  5043.8  5059.5  5076.4  5077.3  5084.8  5090.2  5097.9
  5103.3  5111.5    5117  5119.6  5127.7  5137.9  5142.2  5144.4  5196.8  5201.5
 2454.51 2452.52 2449.42 2447.49 2443.21 2440.72 2438.18  2436.6 2435.36  2431.7
 2431.33 2429.73 2428.81 2428.28 2427.18 2426.62 2426.23 2426.18 2425.58 2425.25
 2424.47 2424.03 2423.34 2422.76 2420.75  2420.2 2417.68 2414.37 2410.02 2409.51
 2408.56 2408.22 2407.95 2407.42  2407.5 2408.11  2408.1    2408    2408    2408
    2408    2408    2408 2411.94 2414.89 2426.06 2426.81 2433.73 2437.58 2441.47
 2441.12 2441.47    2442  2441.9 2446.15 2450.06 2453.54 2454.95 2479.79  2481.8
    2380    2380    2380    2380    2380    2380    2380    2380    2380    2380
    2380    2380    2380    2380    2380    2380    2380    2380    2380    2380
    2380    2380    2380    2380    2380    2380    2380    2380    2380    2380
    2380    2380    2380    2380    2380    2380    2380    2380    2380    2407
    2407    2380    2380    2380    2380    2380    2380    2380    2380    2380
    2380    2380    2380    2380    2380    2380    2380    2380    2380    2380
Abutment Skew #Up #Dn= , 2 , 2
  4980.5  4987.5
    2407 2401.76
  4980.5  4987.5
    2407 2404.47
Abutment Skew #Up #Dn= , 2 , 2
  5012.5  5019.5
 2402.08    2407
  5012.5  5019.5
 2402.07    2407
BR Coef= 1 , 1 , 0 ,1.25, 0 ,,,0.8,0,2,0,
WSPro=,,,, 1 ,,,, 0 ,,,, 0 ,,,,-1 ,-1 ,-1 , 0 , 0 , 0 , 0 , 0
BC Design=,, 0 ,, 0 ,,,,,,
BC HTab HWMax=2477.09

Type RM Length L Ch R = 1 ,13805   ,207,207,207
BEGIN DESCRIPTION:
XS 55
END DESCRIPTION:
XS GIS Cut Line= 5
      1061725.56       839973.83      1061880.72       840255.95
      1061946.83       840315.79      1062056.37        840325.4
      1062205.51       840365.61
#Sta/Elev= 30
  4526.5 2454.73  4539.9 2452.08  4592.7 2438.75    4602 2437.48    4627 2431.85
  4638.6 2430.51  4682.8 2427.47  4794.5 2422.67  4814.8  2422.4  4828.4  2421.4
    4839 2418.97  4858.7 2410.28  4901.2 2406.98    4971 2406.92  4980.9 2406.04
  4992.3 2402.98  4998.1    2400  5002.7    2400  5014.4 2403.07  5031.1 2407.62
    5046 2409.81  5061.2 2415.54  5091.1    2439  5095.5 2441.14    5100 2441.87
  5104.9 2441.48  5129.2 2443.02  5139.8 2451.47  5179.2 2473.86  5202.1 2483.97
#Mann= 5 ,-1 , 0
  4526.5    .065       0  4814.8     .09       0  4992.3     .05       0
  5014.4     .09       0    5100    .065       0
#XS Ineff= 2 , 0
       0  4958.5 2407.76  5041.5       0 2411.21
Permanent Ineff=
       F       F
Bank Sta=4992.3,5014.4
Exp/Cntr=0.5,0.3

Type RM Length L Ch R = 1 ,13598   ,387,387,387
BEGIN DESCRIPTION:
XS 54
END DESCRIPTION:
XS GIS Cut Line= 5
      1061697.35       839973.83      1061804.15       840215.65
      1061955.28       840469.55      1061965.36       840544.11
      1061961.26        840774.7
#Sta/Elev= 30
  4393.1 2457.28  4414.4 2452.62  4428.8 2447.63    4460 2442.04  4482.8 2434.88
  4493.9 2433.02  4557.9  2427.8  4608.7 2426.35  4697.6 2421.59  4722.3 2418.64
    4743 2409.16  4761.3 2409.15  4826.8 2406.37  4953.6 2406.75  4988.8 2401.34
  4995.8 2398.97  5006.9 2398.97  5018.9 2401.34  5026.9 2403.34  5062.5  2430.5
  5069.1 2432.56  5094.7 2450.62  5100.3 2454.42  5122.1 2454.77  5144.8 2469.36
  5176.8 2493.78  5192.1 2502.32    5206 2507.56  5238.6 2522.46  5258.7 2529.57
#Mann= 5 ,-1 , 0
  4393.1    .065       0  4761.3     .09       0  4988.8    .045       0
  5018.9     .09       0  5094.7     .08       0
#XS Ineff= 2 , 0
       0    4900    2440               0
Permanent Ineff=
       F       F
Bank Sta=4988.8,5018.9
Exp/Cntr=0.3,0.1

Type RM Length L Ch R = 1 ,13211   ,398,398,398
BEGIN DESCRIPTION:
XS 53
END DESCRIPTION:
XS GIS Cut Line= 5
      1061644.95       839998.01      1061701.38       840213.63
      1061604.65       840405.07      1061576.44       840455.45
      1061509.94       840566.28
#Sta/Elev= 30
  4524.5 2451.11  4535.5 2447.27  4569.5 2440.78  4593.9 2434.22  4605.2 2432.63
  4609.2 2431.21  4660.3 2425.93  4703.1 2423.83  4747.4 2422.64  4790.6  2420.4
  4827.4 2414.06  4900.5 2406.13  4939.1 2403.98  4965.2 2404.17    4971 2403.92
 4982.71 2401.52  4992.4 2399.24  4994.7 2397.33  5007.3 2397.33  5008.9 2399.45
  5015.8  2400.5  5030.7 2406.97  5063.6 2430.58  5076.6 2439.09  5097.8 2448.68
  5099.7 2448.68    5113 2449.06  5123.7 2450.65  5136.8 2462.16  5148.9 2468.39
#Mann= 6 ,-1 , 0
  4524.5     .09       0  4703.1    .065       0  4965.2     .09       0
 4982.71     .05       0  5015.8     .09       0  5099.7    .065       0
Bank Sta=4982.71,5015.8
Exp/Cntr=0.3,0.1

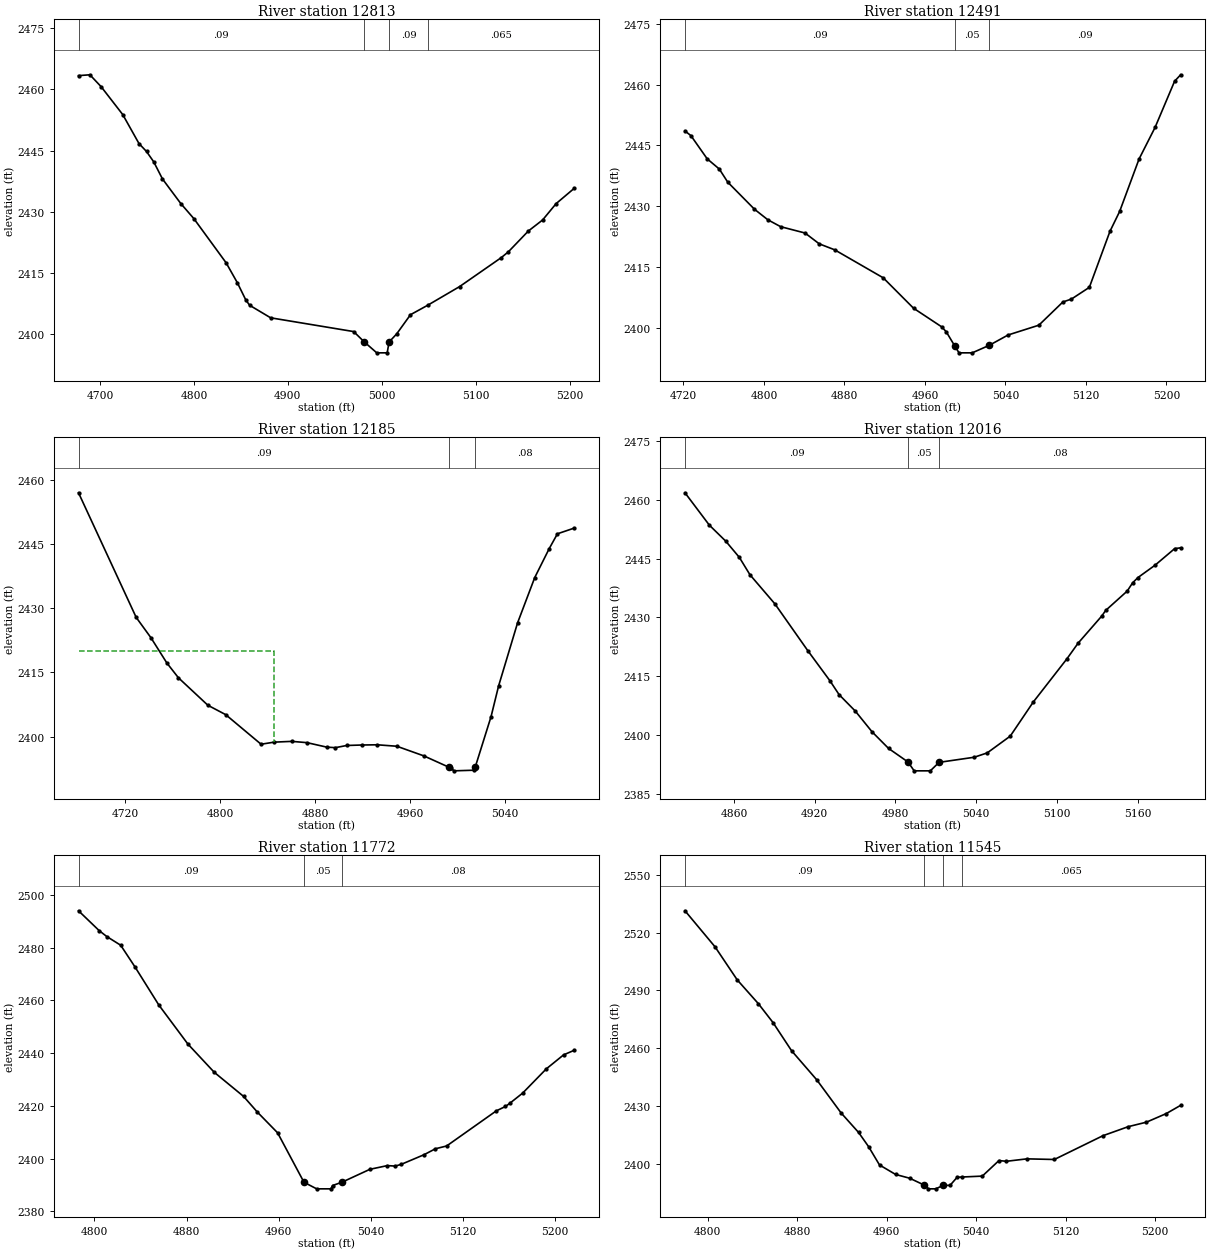
Type RM Length L Ch R = 1 ,12813   ,322,322,322
BEGIN DESCRIPTION:
XS 52
END DESCRIPTION:
XS GIS Cut Line= 5
      1061391.05       839933.53      1061378.96       840072.57
      1061336.64        840169.3      1061227.82       840231.77
      1061125.05       840350.66
#Sta/Elev= 30
  4677.1 2463.35  4689.2 2463.56  4701.2 2460.64  4724.2 2453.81  4741.5 2446.71
  4749.5 2444.77  4757.2 2442.23  4766.5 2438.04  4786.1 2431.99  4799.9 2428.33
  4834.3 2417.49  4846.2 2412.63  4855.3 2408.37  4859.4 2407.08  4881.7 2404.02
  4970.1 2400.65  4981.1 2398.18  4994.7 2395.44  5005.8 2395.44  5007.8 2398.09
  5015.9 2400.08  5030.6 2404.78  5049.1 2407.12  5082.9 2411.67  5127.3 2418.77
  5134.8 2420.18  5156.1 2425.28  5171.3 2427.99  5185.7    2432  5204.9 2435.73
#Mann= 4 ,-1 , 0
  4677.1     .09       0  4981.1     .05       0  5007.8     .09       0
  5049.1    .065       0
Bank Sta=4981.1,5007.8
Exp/Cntr=0.3,0.1

Type RM Length L Ch R = 1 ,12491   ,306,306,306
BEGIN DESCRIPTION:
XS 51
END DESCRIPTION:
XS GIS Cut Line= 5
      1061260.06       839816.65      1061187.52       839911.36
      1061060.57       839959.72      1061018.25       840028.24
      1060877.19       840096.75
#Sta/Elev= 30
  4721.6 2448.57  4727.5 2447.42  4743.7 2441.69  4755.7 2439.18  4764.1 2435.94
  4790.6 2429.27  4803.9 2426.66  4816.7 2424.95  4840.9 2423.39    4855 2420.72
  4870.3 2419.25  4918.6 2412.33  4948.7 2404.83  4976.7 2400.23  4981.2 2399.02
  4989.5 2395.58  4993.9 2393.82    5007 2393.82  5023.9 2395.67  5042.7 2398.23
  5073.2 2400.64  5097.1 2406.37  5105.6 2407.09  5123.4 2409.98  5143.9 2423.82
  5153.5 2428.71  5172.8 2441.66  5188.7 2449.45  5208.1 2460.85  5214.1 2462.44
#Mann= 3 ,-1 , 0
  4721.6     .09       0  4989.5     .05       0  5023.9     .09       0
Bank Sta=4989.5,5023.9
Exp/Cntr=0.3,0.1

Type RM Length L Ch R = 1 ,12185   ,169,169,169
BEGIN DESCRIPTION:
XS 50
END DESCRIPTION:
XS GIS Cut Line= 4
      1060966.54       839642.92      1060885.25       839816.65
      1060774.42         839863.      1060687.77       839923.45
#Sta/Elev= 30
  4680.5    2457  4729.1 2427.86  4741.5 2423.12  4754.9 2417.22  4764.7 2413.74
  4789.5 2407.32  4804.5 2405.13  4834.3 2398.21  4845.4  2398.7  4860.2 2398.88
    4873 2398.58  4889.7 2397.53  4896.9 2397.41  4906.5 2397.92  4919.5 2398.03
  4932.2 2398.08  4948.7 2397.74  4971.6 2395.47  4992.4 2392.86  4994.6 2392.61
  4996.7 2391.99    5014 2392.14  5014.9    2393  5028.1 2404.69  5034.4 2411.81
  5050.4 2426.57  5064.9 2437.19  5077.1 2443.96    5084 2447.41  5098.1 2448.74
#Mann= 3 ,-1 , 0
  4680.5     .09       0  4992.4     .04       0  5014.9     .08       0
#XS Ineff= 2 , 0
       0    4845    2420               0
Permanent Ineff=
       F       F
Bank Sta=4992.4,5014.9
Exp/Cntr=0.3,0.1

Type RM Length L Ch R = 1 ,12016   ,244,244,244
BEGIN DESCRIPTION:
XS 49
END DESCRIPTION:
XS GIS Cut Line= 4
      1060830.68       839563.13      1060752.25       839697.76
      1060711.95       839742.09      1060671.65        839889.2
#Sta/Elev= 30
  4823.6 2461.75  4841.7 2453.51  4853.9 2449.43    4864  2445.3  4871.9 2440.87
  4890.4 2433.47  4914.8 2421.58  4931.3 2413.89  4938.1 2410.36  4950.2 2406.15
  4962.6 2400.89  4974.9 2396.65  4989.3 2393.21  4993.9 2390.95  5005.9 2390.95
  5012.4 2393.11  5038.5 2394.41  5048.2 2395.52  5065.3 2399.79  5082.4 2408.47
  5107.4 2419.47  5115.7 2423.45  5133.3 2430.37  5136.2 2431.79  5152.2 2436.72
  5156.2 2438.81  5160.2 2440.17  5172.9 2443.31  5187.5 2447.54  5191.9 2447.73
#Mann= 3 ,-1 , 0
  4823.6     .09       0  4989.3     .05       0  5012.4     .08       0
Bank Sta=4989.3,5012.4
Exp/Cntr=0.3,0.1

Type RM Length L Ch R = 1 ,11772   ,227,227,227
BEGIN DESCRIPTION:
XS 48
END DESCRIPTION:
XS GIS Cut Line= 3
       1060433.9       839504.91      1060514.47       839736.05
      1060627.31       839883.15
#Sta/Elev= 30
  4786.2 2494.01  4804.1 2486.49  4810.7 2484.25  4822.8 2480.94  4835.4 2472.58
  4855.9 2458.26  4881.1 2443.46    4904 2432.73  4929.4  2423.6  4941.5 2417.59
    4959 2409.76  4981.9 2390.99  4992.9  2388.5  5005.3  2388.5  5006.7 2389.76
  5014.9 2391.02  5039.1 2395.91  5054.3 2397.32  5061.1 2397.13  5066.4 2397.81
    5086 2401.43    5096 2403.71  5105.7 2404.76  5148.9 2418.11  5156.8 2419.76
  5160.4 2420.91  5171.7 2424.83  5192.2 2434.02  5207.2 2439.33  5216.4 2441.07
#Mann= 3 ,-1 , 0
  4786.2     .09       0  4981.9     .05       0  5014.9     .08       0
Bank Sta=4981.9,5014.9
Exp/Cntr=0.3,0.1

Type RM Length L Ch R = 1 ,11545   ,263,263,263
BEGIN DESCRIPTION:
XS 47
END DESCRIPTION:
XS GIS Cut Line= 4
       1060185.9       839774.46      1060357.29       839879.12
      1060423.79       839897.26      1060597.09        839903.3
#Sta/Elev= 30
  4779.6 2531.39  4806.5 2512.65  4826.3 2495.52  4845.2 2483.16  4858.3 2473.35
  4874.9 2458.72  4897.4 2443.62  4919.2  2426.4  4934.8 2416.29  4943.8 2408.87
  4953.5  2399.4  4967.9 2394.48  4980.5 2392.52  4993.5 2388.95  4997.3 2387.01
  5003.8 2387.01  5010.2 2388.75  5016.6 2388.84  5022.9 2393.02  5027.2 2393.15
  5045.4 2393.62  5060.3  2401.7  5066.9 2401.31  5085.3 2402.58  5109.8 2402.25
  5153.2 2414.59  5175.9  2419.3  5192.1 2421.62  5209.9  2426.1  5222.7 2430.37
#Mann= 4 ,-1 , 0
  4779.6     .09       0  4993.5     .05       0  5010.2     .09       0
  5027.2    .065       0
Bank Sta=4993.5,5010.2
Exp/Cntr=0.3,0.1

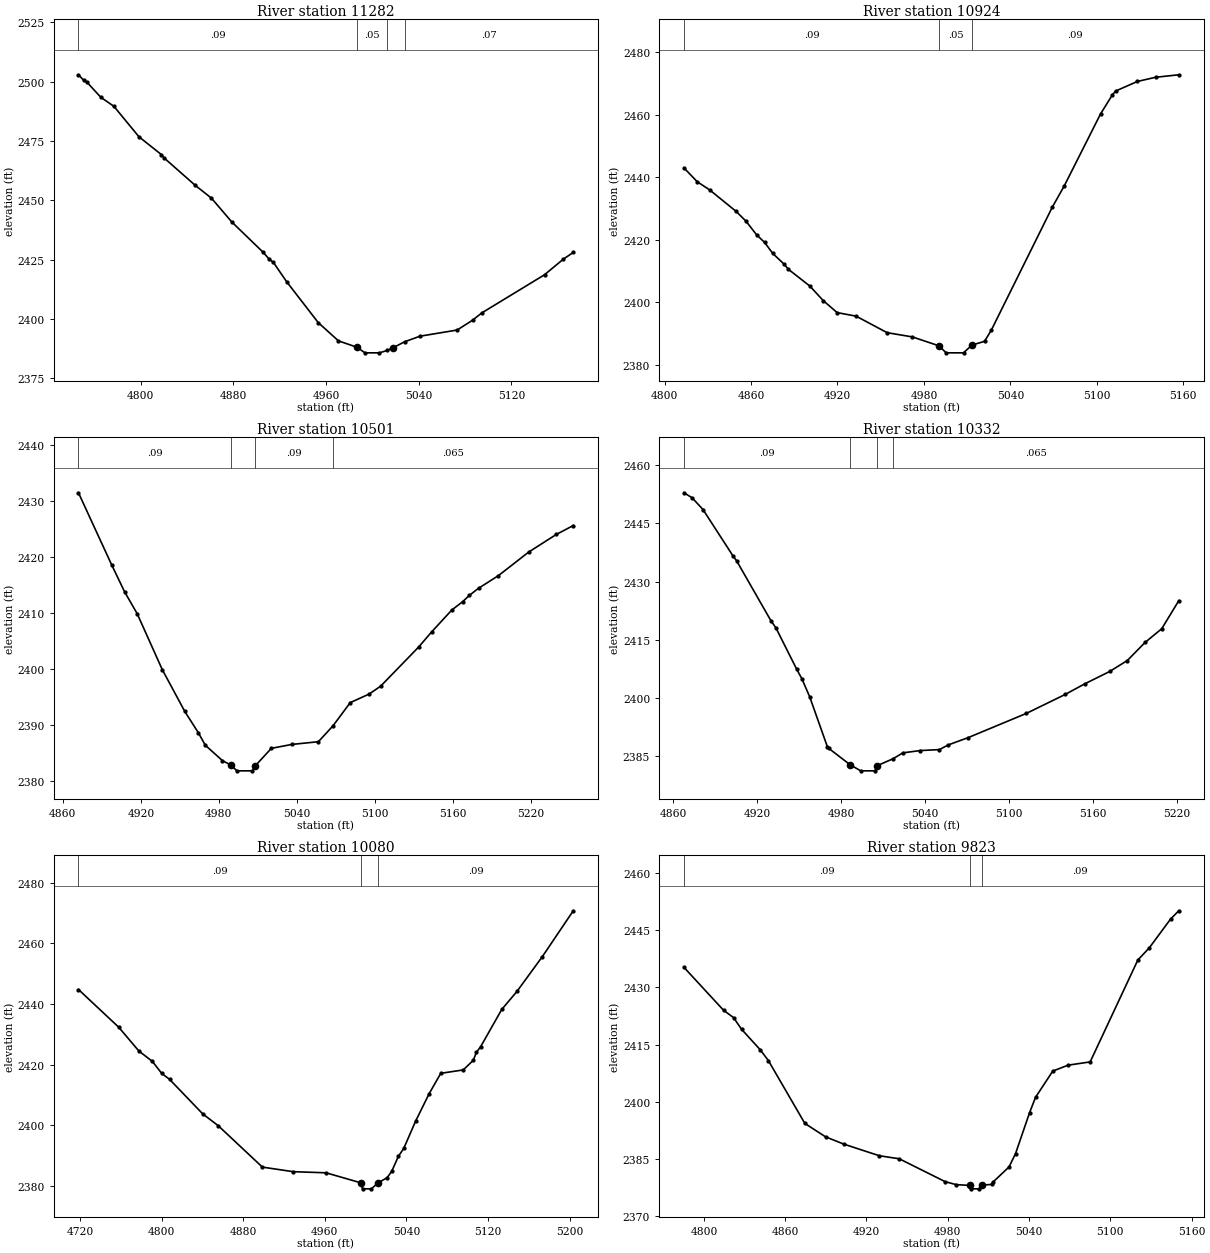
Type RM Length L Ch R = 1 ,11282   ,358,358,358
BEGIN DESCRIPTION:
XS 46
END DESCRIPTION:
XS GIS Cut Line= 4
      1060274.32       840227.32      1060468.12       840106.83
      1060512.45       840042.34      1060627.31       840006.07
#Sta/Elev= 30
  4746.4 2502.88  4751.1 2500.48  4753.9 2499.64  4765.7 2493.39    4777 2489.57
  4798.6 2476.74  4817.9 2469.26  4820.3 2467.82  4847.2 2456.25  4861.1 2450.89
  4878.9 2440.73  4905.3 2428.28  4911.1 2425.11  4914.5 2423.86    4926 2415.67
  4953.3 2398.41  4970.7 2390.73  4986.8 2388.02  4993.6 2385.68  5006.1 2385.68
  5012.7 2386.68  5017.6 2387.78  5027.8 2390.34  5041.1  2392.7  5073.1 2395.29
  5086.4 2399.42  5094.2 2402.45  5148.5 2418.59  5164.6 2425.11  5173.3 2428.01
#Mann= 4 ,-1 , 0
  4746.4     .09       0  4986.8     .05       0  5012.7     .09       0
  5027.8     .07       0
Bank Sta=4986.8,5017.6
Exp/Cntr=0.3,0.1

Type RM Length L Ch R = 1 ,10924   ,423,423,423
BEGIN DESCRIPTION:
XS 45
END DESCRIPTION:
XS GIS Cut Line= 4
      1060538.65       840344.61      1060677.69       840314.39
      1060750.24       840320.43      1060869.13       840272.07
#Sta/Elev= 30
  4813.5 2443.05  4822.7 2438.64  4831.4 2435.99  4849.7 2429.14  4856.5 2426.03
  4863.9 2421.65  4869.5 2419.19  4875.1  2415.7  4882.9 2412.29    4886  2410.6
  4900.8 2405.27  4910.2 2400.57  4919.8 2396.76    4933 2395.61  4954.5 2390.33
  4972.1 2388.97  4990.6  2386.1  4995.4 2383.88  5007.5 2383.88  5013.3 2386.34
  5022.1 2387.57  5026.7 2391.05  5069.2 2430.57  5077.3 2437.19  5102.6 2460.32
  5110.8 2466.42    5113 2467.64  5128.1 2470.71  5140.8 2472.06  5156.9 2472.86
#Mann= 3 ,-1 , 0
  4813.5     .09       0  4990.6     .05       0  5013.3     .09       0
Bank Sta=4990.6,5013.3
Exp/Cntr=0.3,0.1

Type RM Length L Ch R = 1 ,10501   ,169,169,169
BEGIN DESCRIPTION:
XS 44
END DESCRIPTION:
XS GIS Cut Line= 4
      1060709.93       840761.75      1060806.66       840731.52
      1060857.04       840701.29      1060996.08       840530.01
#Sta/Elev= 30
    4872 2431.42  4897.6 2418.52  4907.5 2413.73  4917.2 2409.81  4936.5 2399.83
  4953.8 2392.37  4964.2 2388.58  4969.6 2386.33  4982.8 2383.58  4989.5 2382.76
  4993.9 2381.76  5005.8 2381.76  5008.1 2382.67  5020.4 2385.78  5036.3 2386.48
  5056.6 2386.96  5067.8 2389.79  5081.1 2393.94  5095.7 2395.48  5104.5 2396.88
  5133.7 2403.86  5143.7 2406.56  5159.2 2410.47  5167.6 2411.97  5172.7 2413.09
  5179.8 2414.36  5195.1 2416.62  5218.4 2420.83  5239.6 2423.97  5252.7 2425.57
#Mann= 4 ,-1 , 0
    4872     .09       0  4989.5     .05       0  5008.1     .09       0
  5067.8    .065       0
Bank Sta=4989.5,5008.1
Exp/Cntr=0.3,0.1

Type RM Length L Ch R = 1 ,10332   ,252,252,252
BEGIN DESCRIPTION:
XS 43
END DESCRIPTION:
XS GIS Cut Line= 4
       1060865.1        840902.8       1060945.7       840836.31
      1060983.99       840791.97      1061082.73       840628.75
#Sta/Elev= 30
  4867.7 2452.83  4873.5 2451.55  4881.3 2448.52    4903 2436.45  4905.3 2435.36
  4929.8 2419.97  4933.5 2418.05  4948.4 2407.38    4952 2405.01  4957.6 2400.36
  4970.2 2387.56  4971.1 2387.12  4986.6 2382.85  4994.1  2381.3  5004.4  2381.3
    5006 2382.64  5017.3 2384.42  5024.3 2385.93  5036.8 2386.52  5050.4 2386.76
  5056.6 2387.95    5071 2389.85  5112.5 2396.06  5140.3 2400.94  5154.3 2403.67
  5172.2 2406.86  5184.8 2409.68  5197.5 2414.33  5209.4 2417.85  5221.6 2425.06
#Mann= 4 ,-1 , 0
  4867.7     .09       0  4986.6     .05       0    5006     .09       0
  5017.3    .065       0
Bank Sta=4986.6,5006
Exp/Cntr=0.3,0.1

Type RM Length L Ch R = 1 ,10080   ,257,257,257
BEGIN DESCRIPTION:
XS 42
END DESCRIPTION:
XS GIS Cut Line= 4
      1060889.28       840935.05      1061082.73       840935.05
      1061197.59       840945.12      1061367.64        840990.7
#Sta/Elev= 30
  4718.6 2444.79    4758 2432.36  4777.8 2424.49    4791 2421.08  4800.2  2417.1
  4807.8 2415.17  4840.3 2403.77  4855.7 2399.81  4898.8  2386.2    4929 2384.69
  4961.2 2384.32  4995.3 2381.01  4996.9 2379.03  5005.5 2379.03  5012.4 2381.04
  5021.1 2382.73  5025.6 2384.85    5032 2389.71  5037.4 2392.43  5048.9 2401.34
  5062.3 2410.48  5073.6 2417.14  5095.6 2418.26  5105.4 2421.41  5108.5 2424.05
  5112.7 2425.95  5133.4 2438.24  5148.2 2444.14  5173.1 2455.63  5203.4 2470.76
#Mann= 3 ,-1 , 0
  4718.6     .09       0  4995.3     .05       0  5012.4     .09       0
Bank Sta=4995.3,5012.4
Exp/Cntr=0.3,0.1

Type RM Length L Ch R = 1 ,9823    ,293,293,293
BEGIN DESCRIPTION:
XS 41
END DESCRIPTION:
XS GIS Cut Line= 4
      1060881.22       841003.56      1060983.99       841110.36
      1061052.51       841170.82      1061135.13       841265.53
#Sta/Elev= 30
  4785.3 2435.28  4814.5 2424.01  4821.9 2422.07  4827.8 2419.01  4841.5 2413.65
  4847.6 2410.78  4874.5 2394.26  4889.8 2390.73  4903.3 2388.81  4929.5 2385.76
  4944.2 2384.96    4978 2378.96  4986.2 2378.16  4996.5 2377.96  4997.5 2377.06
  5002.9 2377.06  5005.2 2378.03  5012.6 2378.23  5013.4 2378.84  5025.2 2382.81
    5030  2386.3  5040.4  2397.1  5044.8 2401.13  5057.5 2408.01  5068.8 2409.57
  5085.1 2410.43  5120.3 2437.22  5128.8 2440.44  5144.4 2447.96  5150.5 2450.16
#Mann= 3 ,-1 , 0
  4785.3     .09       0  4996.5     .05       0  5005.2     .09       0
Bank Sta=4996.5,5005.2
Exp/Cntr=0.3,0.1

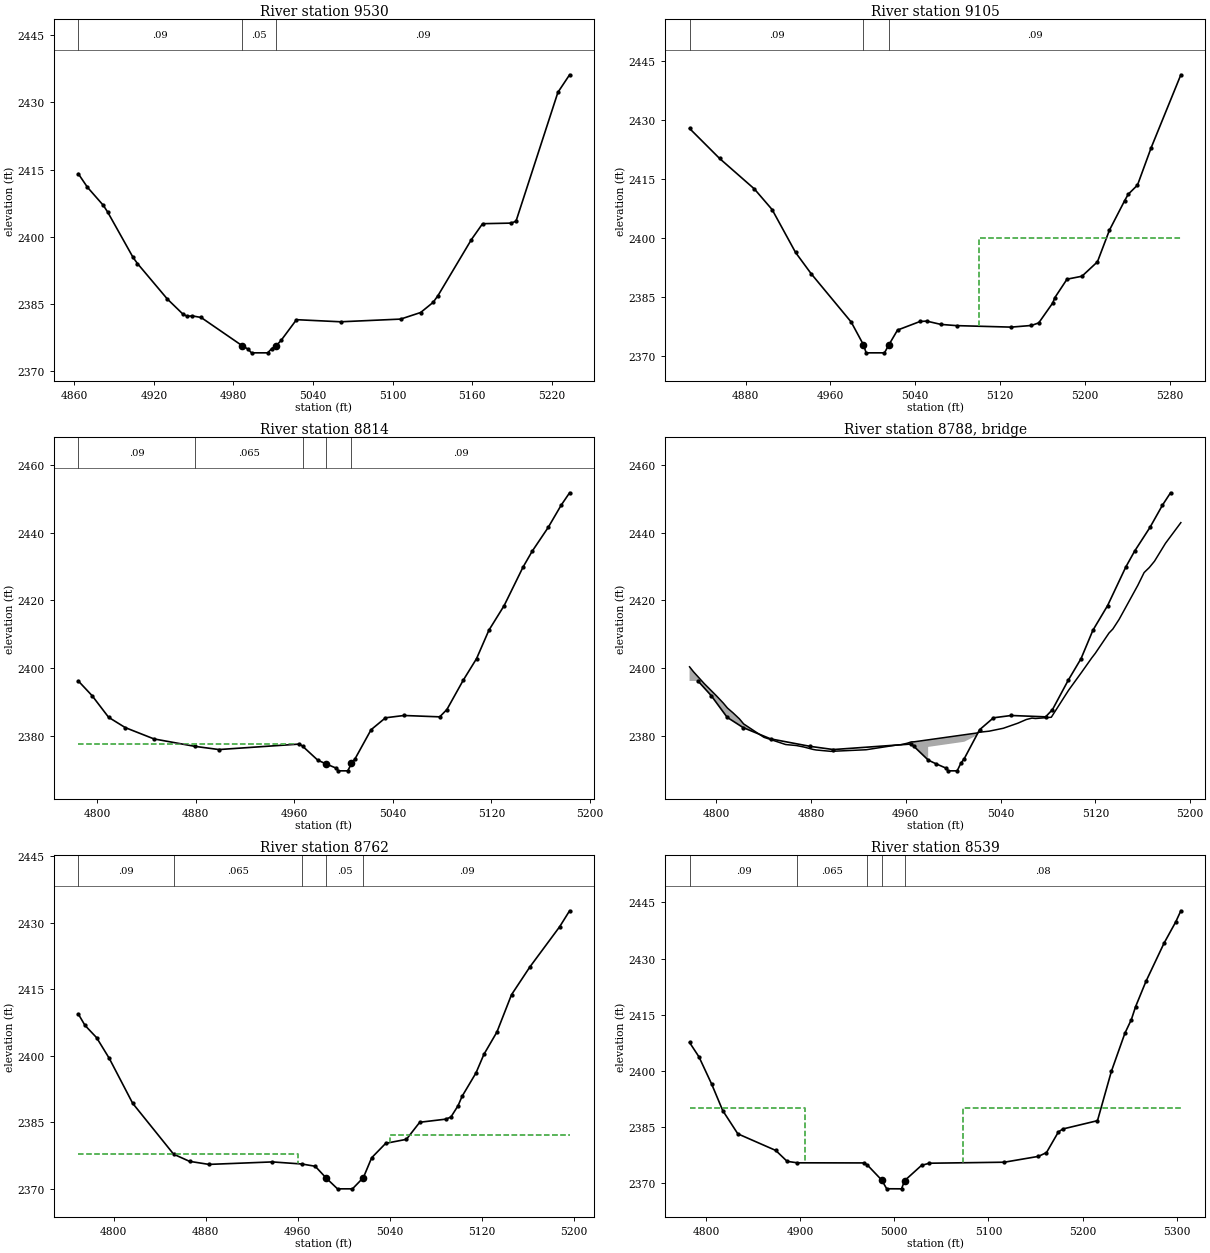
Type RM Length L Ch R = 1 ,9530    ,425,425,425
BEGIN DESCRIPTION:
XS 40
END DESCRIPTION:
XS GIS Cut Line= 5
      1060701.87       841144.62      1060766.36       841243.36
      1060770.39       841330.01      1060806.66       841374.34
      1060887.26       841446.89
#Sta/Elev= 30
    4863 2414.06  4869.9 2411.04  4881.9 2406.99  4885.1 2405.53  4904.3 2395.38
  4907.6 2394.02  4930.1 2386.11    4942  2382.7  4945.1 2382.26  4949.1 2382.33
  4955.6 2381.98  4986.5 2375.69  4990.8 2374.95  4993.6 2374.09  5005.8 2374.09
  5008.9 2375.05  5012.2 2375.65  5016.1 2376.95  5027.5 2381.49  5060.8 2381.02
    5106 2381.62  5121.1 2383.09  5130.5 2385.35  5134.2 2386.87  5159.4 2399.38
  5167.8 2402.91  5189.3 2403.04    5193 2403.46  5224.6 2432.23  5233.4 2436.14
#Mann= 3 ,-1 , 0
    4863     .09       0  4986.5     .05       0  5012.2     .09       0
Bank Sta=4986.5,5012.2
Exp/Cntr=0.3,0.1

Type RM Length L Ch R = 1 ,9105    ,291,291,291
BEGIN DESCRIPTION:
XS 39
END DESCRIPTION:
XS GIS Cut Line= 5
      1060405.65       841148.65      1060343.18        841275.6
      1060349.23       841352.18      1060323.03       841454.95
      1060236.38       841563.77
#Sta/Elev= 30
  4827.1 2427.87  4855.4 2420.25  4888.2  2412.5    4905 2407.24  4927.1 2396.34
  4941.8 2390.94  4979.6 2378.64  4991.2 2372.84  4993.7 2370.81    5011 2370.81
    5015 2372.78  5023.3  2376.6  5044.5 2378.78  5050.8 2378.88  5064.2 2378.04
    5079 2377.73  5130.5 2377.35  5149.6 2377.77  5156.5 2378.42  5169.8 2383.52
  5171.6  2384.8  5183.2 2389.54  5197.3 2390.29  5211.9 2393.95  5223.2 2401.99
  5237.6 2409.52  5240.9 2411.12  5249.7 2413.47  5262.6 2422.98  5290.6 2441.52
#Mann= 3 ,-1 , 0
  4827.1     .09       0  4991.2     .05       0    5015     .09       0
#XS Ineff= 2 , 0
       0                    5100       0    2400
Permanent Ineff=
       F       F
Bank Sta=4991.2,5015
Exp/Cntr=0.5,0.3

Type RM Length L Ch R = 1 ,8814    ,52,52,52
BEGIN DESCRIPTION:
XS 38
END DESCRIPTION:
XS GIS Cut Line= 6
      1060215.21       841090.67      1060126.65       841171.39
      1060099.74       841217.36      1060062.75       841257.72
      1060031.35        841299.2      1059957.36       841392.25
#Sta/Elev= 30
  4784.7 2396.22  4795.9 2391.88  4809.3  2385.5  4822.8 2382.46  4846.1 2379.12
  4879.2 2376.93  4898.9 2375.98  4964.2  2377.6  4966.7 2376.98    4979 2372.86
  4985.4  2371.8  4994.2 2370.47  4995.7  2369.7  5003.4  2369.7  5006.4 2371.88
  5009.4 2373.32  5022.3 2381.83    5034 2385.35    5049 2386.03    5078 2385.63
  5083.8 2387.77    5097 2396.38  5107.9 2402.81  5117.9 2411.18  5130.3 2418.46
  5145.6  2429.8    5153 2434.47    5166  2441.5  5176.6  2448.1  5183.4 2451.74
#Mann= 5 ,-1 , 0
  4784.7     .09       0  4879.2    .065       0  4966.7     .09       0
  4985.4     .05       0  5006.4     .09       0
#XS Ineff= 2 , 0
       0    4960 2377.74    5040       0  2382.1
Permanent Ineff=
       F       F
Bank Sta=4985.4,5006.4
Exp/Cntr=0.5,0.3

Type RM Length L Ch R = 3 ,8788    ,,,
BEGIN DESCRIPTION:
XS 37 TOR
Structure ID: XS 37
Approximate Survey Structure
END DESCRIPTION:
Bridge Culvert--1,0,-1,-1, 0
Deck Dist Width WeirC Skew NumUp NumDn MinLoCord MaxHiCord MaxSubmerge Is_Ogee
19,14,3,0, 48, 48, , , , 0, 1,1,,
  4777.6  4780.9  4789.9  4800.1  4806.1  4809.6  4814.3  4819.7  4823.2  4840.3
  4858.7  4867.8  4873.9  4881.8  4884.5  4896.9  4926.5  4951.3    4956  4961.3
  4964.6  4967.1  4978.9  4978.9  5019.7    5021    5021  5021.8  5030.3  5042.3
  5054.6  5061.7  5066.5  5069.4  5082.8  5097.4  5108.3  5116.9  5119.9  5131.5
  5134.7    5140  5155.8  5161.1  5165.5  5169.9  5179.1  5192.1
 2400.39 2398.94 2395.47  2391.9 2389.68 2388.22  2386.8 2385.02 2383.55  2379.6
 2377.46 2377.16 2376.74 2376.02 2375.85 2375.45 2375.92 2377.26 2377.41 2377.85
 2378.24 2378.27 2378.85 2378.85 2380.85 2380.99 2380.99 2381.08  2381.4 2382.26
 2383.76 2384.84 2385.26 2385.14 2385.51 2393.49 2398.75 2403.01 2404.37 2410.37
 2411.53 2414.38 2424.44  2428.2 2429.69 2431.57 2436.82 2442.93
    2344    2344    2344    2344    2344    2344    2344    2344    2344    2344
    2344    2344    2344    2344    2344    2344    2344    2344    2344    2344
    2344    2344    2344 2376.76 2378.79 2378.85    2344    2344    2344    2344
    2344    2344    2344    2344    2344    2344    2344    2344    2344    2344
    2344    2344    2344    2344    2344    2344    2344    2344
  4777.6  4780.9  4789.9  4800.1  4806.1  4809.6  4814.3  4819.7  4823.2  4840.3
  4858.7  4867.8  4873.9  4881.8  4884.5  4896.9  4926.5  4951.3    4956  4961.3
  4964.6  4967.1  4978.9  4978.9  5019.7    5021    5021  5021.8  5030.3  5042.3
  5054.6  5061.7  5066.5  5069.4  5082.8  5097.4  5108.3  5116.9  5119.9  5131.5
  5134.7    5140  5155.8  5161.1  5165.5  5169.9  5179.1  5192.1
 2400.39 2398.94 2395.47  2391.9 2389.68 2388.22  2386.8 2385.02 2383.55  2379.6
 2377.46 2377.16 2376.74 2376.02 2375.85 2375.45 2375.92 2377.26 2377.41 2377.85
 2378.24 2378.27 2378.85 2378.85 2380.85 2380.99 2380.99 2381.08  2381.4 2382.26
 2383.76 2384.84 2385.26 2385.14 2385.51 2393.49 2398.75 2403.01 2404.37 2410.37
 2411.53 2414.38 2424.44  2428.2 2429.69 2431.57 2436.82 2442.93
    2344    2344    2344    2344    2344    2344    2344    2344    2344    2344
    2344    2344    2344    2344    2344    2344    2344    2344    2344    2344
    2344    2344    2344 2376.76 2378.79 2378.85    2344    2344    2344    2344
    2344    2344    2344    2344    2344    2344    2344    2344    2344    2344
    2344    2344    2344    2344    2344    2344    2344    2344
Abutment Skew #Up #Dn= , 2 , 2
    4979  4987.5
 2376.76 2371.23
  4978.7  4983.9
 2376.76 2372.76
Abutment Skew #Up #Dn= , 2 , 2
  5012.5    5021
 2375.44 2378.86
  5017.9    5021
 2373.52 2378.82
BR Coef= 1 , 1 , 0 ,1.25, 0 ,,,0.8,0,2,0,
WSPro=,,,, 1 ,,,, 0 ,,,, 0 ,,,,-1 ,-1 ,-1 , 0 , 0 , 0 , 0 , 0
BC Design=,, 0 ,, 0 ,,,,,,
BC HTab HWMax=2451.74

Type RM Length L Ch R = 1 ,8762    ,223,223,223
BEGIN DESCRIPTION:
XS 36
END DESCRIPTION:
XS GIS Cut Line= 5
      1060187.19       841045.83      1060080.68       841132.15
      1060053.78       841196.05      1059994.36        841246.5
      1059897.94       841351.89
#Sta/Elev= 30
  4769.2 2409.38    4775 2406.82  4785.1 2404.05  4796.1 2399.39  4816.5 2389.24
  4852.1 2377.77  4865.9 2376.16  4882.8 2375.47  4937.9 2376.03  4963.6 2375.56
  4975.2 2375.05    4985 2372.33  4994.6 2369.96  5007.6 2369.96  5017.1  2372.5
  5024.3 2376.97  5036.5 2380.22  5054.5 2381.12  5066.1 2384.97  5088.7 2385.67
  5093.2 2386.15  5099.4 2388.69  5102.9 2390.81    5115 2396.09  5121.9 2400.28
  5133.2 2405.31  5145.9 2413.73  5161.9    2420  5187.8 2429.07  5196.4 2432.65
#Mann= 5 ,-1 , 0
  4769.2     .09       0  4852.1    .065       0  4963.6     .09       0
    4985     .05       0  5017.1     .09       0
#XS Ineff= 2 , 0
       0    4960 2377.74    5040       0  2382.1
Permanent Ineff=
       F       F
Bank Sta=4985,5017.1
Exp/Cntr=0.5,0.3

Type RM Length L Ch R = 1 ,8539    ,400,400,400
BEGIN DESCRIPTION:
XS 35
END DESCRIPTION:
XS GIS Cut Line= 5
      1060135.62       840971.32      1059962.32       841019.68
       1059879.7       841031.77      1059760.81       841094.24
      1059649.98       841150.67
#Sta/Elev= 30
  4782.4 2407.55  4792.4 2403.71    4806 2396.36  4817.7 2389.32  4833.7 2383.12
    4874 2378.68  4886.1 2375.76    4897 2375.37  4967.7 2375.34  4971.4 2374.77
  4986.6 2370.76  4991.9 2368.43  5007.7 2368.41  5010.9 2370.59  5028.9 2374.68
  5037.2 2375.26  5116.9 2375.53  5153.1 2377.09  5161.7  2378.1  5174.3  2383.6
    5179 2384.41  5215.9 2386.64  5230.7 2399.85    5245    2410  5251.9 2413.68
  5256.4 2417.13  5267.4 2423.88  5286.6 2434.09  5299.2 2439.86  5304.5 2442.77
#Mann= 5 ,-1 , 0
  4782.4     .09       0    4897    .065       0  4971.4     .09       0
  4986.6     .05       0  5010.9     .08       0
#XS Ineff= 2 , 0
       0    4905    2390    5073       0    2390
Permanent Ineff=
       F       F
Bank Sta=4986.6,5010.9
Exp/Cntr=0.3,0.1