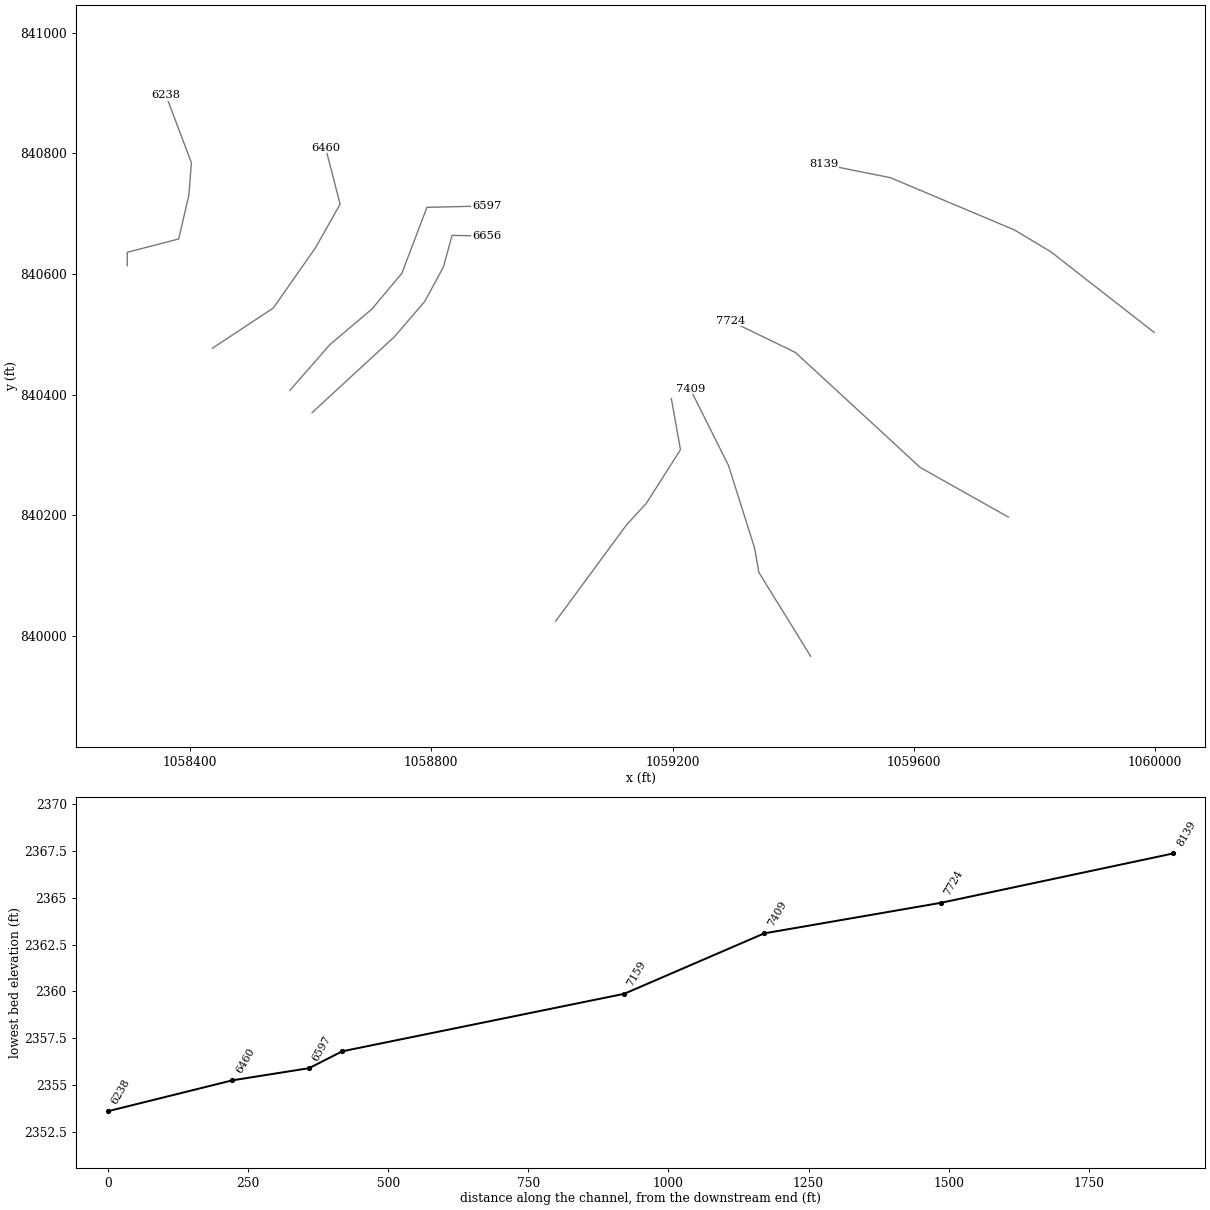
HEC-RAS study lds_cane_crk_lower.prj: Cane Creek Limited Detail Study

--- lds_cane_crk_lower.g01 (geometry) --- (continued)

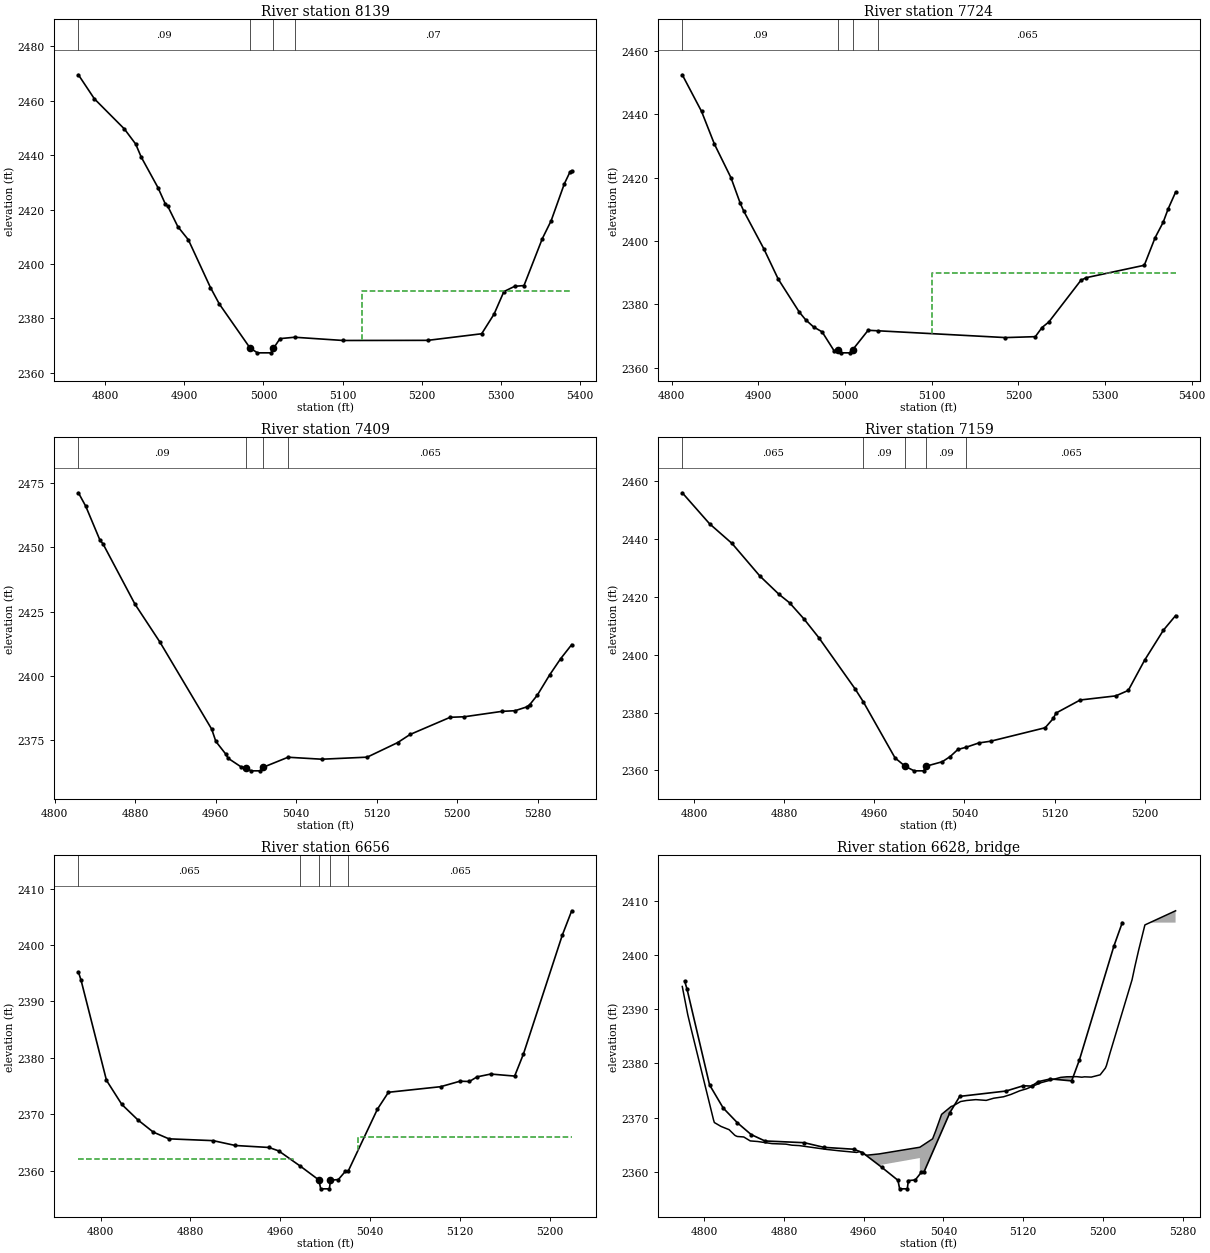
Type RM Length L Ch R = 1 ,8139    ,415,415,415
BEGIN DESCRIPTION:
XS 34
END DESCRIPTION:
XS GIS Cut Line= 5
      1059998.29       840503.34      1059827.31       840636.81
      1059766.85       840673.08      1059561.31       840759.73
      1059450.48        840781.9
#Sta/Elev= 30
  4766.1 2469.53  4786.3  2460.7  4824.2 2449.63  4838.5 2444.09  4845.5  2439.3
  4866.7 2428.06    4876 2422.05  4879.2 2421.16  4891.8 2413.73  4905.1  2408.9
    4933 2391.37  4944.2 2385.33    4983 2369.17  4992.4 2367.37  5009.5 2367.37
  5012.6    2369  5020.9 2372.59  5039.4  2373.1  5100.9 2371.91  5207.8 2371.96
  5275.8 2374.38  5291.5 2381.61  5303.9 2389.87  5317.5 2391.81  5329.3 2392.09
  5352.5 2409.36  5363.6 2415.89  5380.3 2429.48  5387.4 2433.81  5389.6 2434.26
#Mann= 4 ,-1 , 0
  4766.1     .09       0    4983     .05       0  5012.6     .09       0
  5039.4     .07       0
#XS Ineff= 2 , 0
       0                    5125       0    2390
Permanent Ineff=
       F       F
Bank Sta=4983,5012.6
Exp/Cntr=0.3,0.1

Type RM Length L Ch R = 1 ,7724    ,315,315,315
BEGIN DESCRIPTION:
XS 33
END DESCRIPTION:
XS GIS Cut Line= 5
      1059756.77       840197.13      1059610.18       840279.63
      1059568.87       840317.91      1059403.63       840470.06
      1059295.82       840522.45
#Sta/Elev= 30
  4812.3  2452.4  4834.5 2440.87  4849.4 2430.53  4868.5 2419.93  4879.2 2411.87
  4883.2 2409.43  4906.4 2397.53    4923 2387.98  4947.3 2377.57  4954.6 2375.16
  4963.7 2372.91  4973.6 2371.35  4987.6 2365.31  4991.7 2365.65  4995.9 2364.73
  5005.4 2364.73  5008.7 2365.65  5026.7 2371.84  5038.4 2371.68  5185.1 2369.54
  5219.6 2369.83  5227.3 2372.71  5235.2 2374.47  5272.1 2387.57    5278 2388.41
  5345.3 2392.34  5357.8 2401.05  5367.1 2405.91  5372.9 2410.17  5381.4 2415.38
#Mann= 4 ,-1 , 0
  4812.3     .09       0  4991.7     .05       0  5008.7     .09       0
  5038.4    .065       0
#XS Ineff= 2 , 0
       0                    5100       0    2390
Permanent Ineff=
       F       F
Bank Sta=4991.7,5008.7
Exp/Cntr=0.3,0.1

Type RM Length L Ch R = 1 ,7409    ,250,250,250
BEGIN DESCRIPTION:
XS 32
END DESCRIPTION:
XS GIS Cut Line= 5
      1059428.99       839966.39      1059343.17       840105.32
      1059336.12       840145.62      1059292.79       840282.65
      1059229.32        840409.6
#Sta/Elev= 30
  4823.7 2471.23    4831    2466    4845 2452.91  4848.2 2451.32  4879.9 2427.91
  4904.6 2413.21  4956.1  2379.3  4960.2 2374.54    4970 2369.64  4972.4 2367.99
  4985.3 2364.63  4990.2 2364.39  4994.9  2363.1  5004.5  2363.1    5007 2364.45
  5031.9 2368.39  5065.4 2367.62  5110.5 2368.42  5140.7 2374.07  5153.1 2377.24
  5192.9 2383.92    5207 2384.13  5244.4 2386.23  5257.3 2386.48  5269.2 2387.99
    5272 2388.86  5279.5 2392.56  5291.6 2400.35  5302.6  2406.7  5313.6 2412.18
#Mann= 4 ,-1 , 0
  4823.7     .09       0  4990.2     .05       0    5007     .09       0
  5031.9    .065       0
Bank Sta=4990.2,5007
Exp/Cntr=0.3,0.1

Type RM Length L Ch R = 1 ,7159    ,503,503,503
BEGIN DESCRIPTION:
XS 31
END DESCRIPTION:
XS GIS Cut Line= 5
      1059006.33       840024.61      1059123.52       840183.91
      1059156.77       840220.18       1059213.2       840308.85
      1059198.08       840393.48
#Sta/Elev= 30
  4789.5 2455.88  4813.7 2445.19  4833.7 2438.37  4858.4 2427.13  4875.4 2420.81
  4884.8 2417.88  4897.3 2412.43  4910.7 2405.87  4942.8 2388.25  4950.1 2383.79
  4978.4 2364.34  4987.5 2361.41  4995.4 2359.87  5003.9 2359.87  5005.5 2361.41
  5020.4 2363.02  5027.4 2364.81  5034.2 2367.25  5041.5 2368.01  5052.8  2369.5
  5063.3  2370.1  5111.7 2374.75  5118.9 2377.95  5121.3 2379.81  5142.8 2384.33
  5174.4 2385.75  5185.5 2387.64  5199.9 2398.01  5216.7 2408.44  5227.5 2413.47
#Mann= 5 ,-1 , 0
  4789.5    .065       0  4950.1     .09       0  4987.5     .05       0
  5005.5     .09       0  5041.5    .065       0
Bank Sta=4987.5,5005.5
Exp/Cntr=0.5,0.3

Type RM Length L Ch R = 1 ,6656    ,59,59,59
BEGIN DESCRIPTION:
XS 30
END DESCRIPTION:
XS GIS Cut Line= 6
      1058602.53       840370.26      1058739.36       840496.38
      1058789.34       840554.68      1058820.27        840611.8
      1058834.55       840664.15      1058891.66       840662.96
#Sta/Elev= 30
  4780.2 2395.24  4782.6 2393.74  4805.2 2376.03  4818.9 2371.75  4833.2 2369.01
  4846.9 2366.85  4860.8 2365.66  4900.2 2365.34    4920 2364.48  4949.9 2364.13
  4958.6 2363.52  4977.9 2360.81  4994.3 2358.38    4996  2356.8  5003.7  2356.8
  5004.7 2358.32  5011.7 2358.45  5017.9 2359.89  5020.4 2359.91  5046.5 2370.92
  5056.3 2373.91  5102.8  2374.9    5120 2375.87  5128.4 2375.82  5135.2 2376.64
  5147.4 2377.14  5168.7 2376.78  5176.5 2380.68  5211.1 2401.74  5219.5 2406.07
#Mann= 5 ,-1 , 0
  4780.2    .065       0  4977.9     .09       0  4994.3     .05       0
  5004.7     .09       0  5020.4    .065       0
#XS Ineff= 2 , 0
       0    4971    2362    5029       0 2366.01
Permanent Ineff=
       F       F
Bank Sta=4994.3,5004.7
Exp/Cntr=0.5,0.3

Type RM Length L Ch R = 3 ,6628    ,,,
BEGIN DESCRIPTION:
XS 29 TOR
Structure ID: XS 29
Approximate Survey Structure
END DESCRIPTION:
Bridge Culvert--1,0,-1,-1, 0
Deck Dist Width WeirC Skew NumUp NumDn MinLoCord MaxHiCord MaxSubmerge Is_Ogee
18,20,3,0, 56, 56, , , , 0, 1,1,,
  4777.8  4783.3  4786.4  4809.2    4810  4816.7  4824.8  4830.5  4831.4    4833
  4839.5    4846  4853.5  4867.9  4881.8  4887.8  4895.4  4922.5  4936.5  4952.8
  4955.9  4962.7  4975.3  4975.3  5016.3  5016.3  5029.1  5032.2  5038.1  5047.7
  5049.6  5057.2  5063.2  5072.4  5082.9  5090.4  5100.3  5107.7  5116.5  5123.5
  5137.8  5157.7  5163.9  5173.7  5178.9  5181.6  5188.4  5197.3  5202.5  5203.6
  5207.3  5229.3  5232.1  5235.9  5242.2    5273
 2394.25 2389.03 2386.63 2369.54 2369.07 2368.35 2367.75 2366.72 2366.62 2366.49
  2366.4 2365.67 2365.56 2365.17 2365.07 2364.88  2364.8  2364.1 2363.82 2363.54
 2363.69 2363.02 2363.26 2363.26  2364.5  2364.5 2366.06 2367.53 2370.58 2372.04
 2372.15 2372.96 2373.15 2373.31 2373.17 2373.57 2373.84 2374.27 2374.94 2375.32
 2376.44 2377.43 2377.54 2377.56 2377.46 2377.53 2377.48  2377.9 2379.14 2379.62
    2382 2395.49 2397.91 2400.96 2405.64 2408.26
    2328    2328    2328    2328    2328    2328    2328    2328    2328    2328
    2328    2328    2328    2328    2328    2328    2328    2328    2328    2328
    2328    2328    2328 2361.17  2362.5    2328    2328    2328    2328    2328
    2328    2328    2328    2328    2328    2328    2328    2328    2328    2328
    2328    2328    2328    2328    2328    2328    2328    2328    2328    2328
    2328    2328    2328    2328    2328    2328
  4777.8  4783.3  4786.4  4809.2    4810  4816.7  4824.8  4830.5  4831.4    4833
  4839.5    4846  4853.5  4867.9  4881.8  4887.8  4895.4  4922.5  4936.5  4952.8
  4955.9  4962.7  4975.3  4975.3  5016.3  5016.3  5029.1  5032.2  5038.1  5047.7
  5049.6  5057.2  5063.2  5072.4  5082.9  5090.4  5100.3  5107.7  5116.5  5123.5
  5137.8  5157.7  5163.9  5173.7  5178.9  5181.6  5188.4  5197.3  5202.5  5203.6
  5207.3  5229.3  5232.1  5235.9  5242.2    5273
 2394.25 2389.03 2386.63 2369.54 2369.07 2368.35 2367.75 2366.72 2366.62 2366.49
  2366.4 2365.67 2365.56 2365.17 2365.07 2364.88  2364.8  2364.1 2363.82 2363.54
 2363.69 2363.02 2363.26 2363.26  2364.5  2364.5 2366.06 2367.53 2370.58 2372.04
 2372.15 2372.96 2373.15 2373.31 2373.17 2373.57 2373.84 2374.27 2374.94 2375.32
 2376.44 2377.43 2377.54 2377.56 2377.46 2377.53 2377.48  2377.9 2379.14 2379.62
    2382 2395.49 2397.91 2400.96 2405.64 2408.26
    2328    2328    2328    2328    2328    2328    2328    2328    2328    2328
    2328    2328    2328    2328    2328    2328    2328    2328    2328    2328
    2328    2328    2328 2361.17  2362.5    2328    2328    2328    2328    2328
    2328    2328    2328    2328    2328    2328    2328    2328    2328    2328
    2328    2328    2328    2328    2328    2328    2328    2328    2328    2328
    2328    2328    2328    2328    2328    2328
BR Coef= 1 , 1 , 0 ,1.25, 0 ,,,0.8,0,2,0,
WSPro=,,,, 1 ,,,, 0 ,,,, 0 ,,,,-1 ,-1 ,-1 , 0 , 0 , 0 , 0 , 0
BC Design=,, 0 ,, 0 ,,,,,,
BC HTab HWMax=2406.07

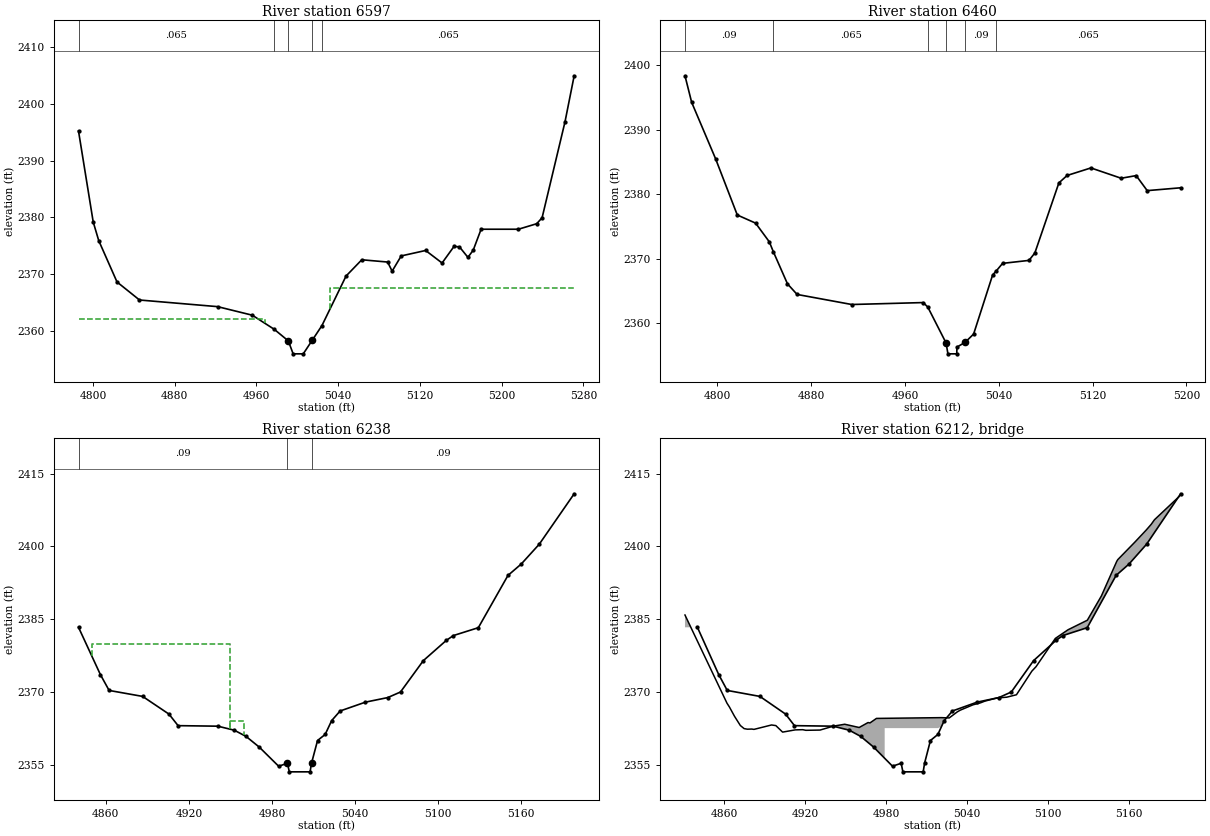
Type RM Length L Ch R = 1 ,6597    ,137,137,137
BEGIN DESCRIPTION:
XS 28
END DESCRIPTION:
XS GIS Cut Line= 6
      1058565.64       840407.14      1058632.28       840483.29
      1058701.29       840541.59      1058751.26       840601.09
       1058792.9       840710.55      1058891.66       840712.93
#Sta/Elev= 30
  4785.8 2395.22  4800.2 2379.16  4805.6 2375.88  4823.5 2368.58  4845.5  2365.4
  4921.9 2364.23  4955.9 2362.72  4977.4 2360.23  4991.2 2358.18  4995.9  2355.9
  5005.8  2355.9  5014.6  2358.3  5024.1 2360.89  5047.7 2369.63  5063.1  2372.5
  5088.4  2372.1  5092.8 2370.49  5101.7 2373.18  5125.6 2374.14  5141.7 2371.93
  5153.4 2374.86  5158.7 2374.78    5167 2372.93  5172.2  2374.2  5179.9 2377.89
  5216.4 2377.89  5234.3 2378.86  5239.6 2379.91    5262 2396.82    5271 2404.97
#Mann= 5 ,-1 , 0
  4785.8    .065       0  4977.4     .09       0  4991.2     .05       0
  5014.6     .09       0  5024.1    .065       0
#XS Ineff= 2 , 0
       0    4968    2362    5032       0 2367.44
Permanent Ineff=
       F       F
Bank Sta=4991.2,5014.6
Exp/Cntr=0.5,0.3

Type RM Length L Ch R = 1 ,6460    ,222,222,222
BEGIN DESCRIPTION:
XS 27
END DESCRIPTION:
XS GIS Cut Line= 5
      1058437.37       840477.11      1058538.13       840543.61
      1058608.66       840644.36      1058648.96        840715.9
      1058624.78       840809.61
#Sta/Elev= 30
  4772.5 2398.37  4778.2 2394.25  4798.6  2385.5  4817.1 2376.78  4832.7 2375.52
  4844.4 2372.62  4847.8  2371.1  4859.9  2366.1  4868.1 2364.46  4914.7  2362.9
  4975.6  2363.2  4979.5 2362.51  4995.1 2356.94  4996.7 2355.25  5004.2 2355.25
  5004.4  2356.3  5011.4 2357.04  5018.6 2358.32  5034.8 2367.48  5037.7 2368.06
  5043.3 2369.28  5065.8 2369.74  5070.8 2370.89  5091.3 2381.76  5098.3 2382.91
  5118.6 2384.08  5144.4 2382.48  5157.2 2382.89  5166.6 2380.56  5195.1    2381
#Mann= 6 ,-1 , 0
  4772.5     .09       0  4847.8    .065       0  4979.5     .09       0
  4995.1     .05       0  5011.4     .09       0  5037.7    .065       0
Bank Sta=4995.1,5011.4
Exp/Cntr=0.5,0.3

Type RM Length L Ch R = 1 ,6238    ,47,47,47
BEGIN DESCRIPTION:
XS 26
END DESCRIPTION:
XS GIS Cut Line= 6
      1058296.12       840613.95      1058296.12       840636.06
      1058381.39       840658.16      1058398.24       840730.81
      1058402.45        840784.5      1058360.34       840896.09
#Sta/Elev= 30
  4840.3 2383.36  4856.1 2373.62  4862.4 2370.36  4886.6 2369.13  4905.6 2365.49
  4912.2 2363.11  4940.9    2363  4952.8 2362.17  4961.3 2360.89  4970.9 2358.67
  4984.8 2354.76  4991.2 2355.36  4992.5  2353.6  5007.5  2353.6  5008.6 2355.43
  5012.9 2360.05  5018.4  2361.3  5023.1 2364.15  5029.2 2366.13  5047.5 2367.95
  5063.6 2368.89  5072.8 2370.04  5089.3  2376.5  5105.9 2380.67    5111 2381.66
    5129 2383.28  5150.4 2394.04    5160 2396.39    5173 2400.47  5198.2 2410.85
#Mann= 3 ,-1 , 0
  4840.3     .09       0  4991.2    .055       0  5008.6     .09       0
#XS Ineff= 3 ,-1
    4850    4950    2380    4950    4960    2364    5040    5100 2366.87
Permanent Ineff=
       F       F       F
Bank Sta=4991.2,5008.6
Exp/Cntr=0.5,0.3

Type RM Length L Ch R = 3 ,6212    ,,,
BEGIN DESCRIPTION:
XS 25 TOR
Structure ID: XS 25
Approximate Survey Structure
END DESCRIPTION:
Bridge Culvert--1,0,-1,-1, 0
Deck Dist Width WeirC Skew NumUp NumDn MinLoCord MaxHiCord MaxSubmerge Is_Ogee
19,14,3,0, 48, 48, , , , 0, 1,1,,
  4831.1  4862.2  4864.1  4867.8  4872.1  4874.9  4877.3  4880.6  4882.2  4895.2
  4898.4  4903.4  4912.8  4918.3  4920.6  4931.1  4940.9  4949.4  4960.1  4966.7
  4968.1  4972.9    4979    4979    5021    5021  5026.8  5032.9    5035  5044.4
  5050.1  5053.2  5062.2  5069.4  5076.6    5088  5091.1  5105.4  5114.8  5129.1
  5139.5  5150.9  5151.7  5164.1  5172.6  5176.4  5178.8  5197.2
 2385.89 2367.74 2366.91 2365.03 2363.14  2362.5 2362.38 2362.41 2362.34 2363.25
 2363.12 2361.78 2362.24 2362.28 2362.15  2362.2    2363  2363.4 2362.73 2363.75
 2363.67  2364.6 2364.62 2364.62 2364.76 2364.76  2364.7 2365.97  2366.3  2367.4
 2367.82 2368.16 2368.81 2368.97 2369.47 2374.33 2375.25 2381.07 2382.85 2384.82
 2389.81 2396.95 2397.31 2400.84 2403.35 2404.56  2405.5 2410.31
  2333.6  2333.6  2333.6  2333.6  2333.6  2333.6  2333.6  2333.6  2333.6  2333.6
  2333.6  2333.6  2333.6  2333.6  2333.6  2333.6  2333.6  2333.6  2333.6  2333.6
  2333.6  2333.6  2333.6  2362.6  2362.6  2333.6  2333.6  2333.6  2333.6  2333.6
  2333.6  2333.6  2333.6  2333.6  2333.6  2333.6  2333.6  2333.6  2333.6  2333.6
  2333.6  2333.6  2333.6  2333.6  2333.6  2333.6  2333.6  2333.6
  4831.1  4862.2  4864.1  4867.8  4872.1  4874.9  4877.3  4880.6  4882.2  4895.2
  4898.4  4903.4  4912.8  4918.3  4920.6  4931.1  4940.9  4949.4  4960.1  4966.7
  4968.1  4972.9    4979    4979    5021    5021  5026.8  5032.9    5035  5044.4
  5050.1  5053.2  5062.2  5069.4  5076.6    5088  5091.1  5105.4  5114.8  5129.1
  5139.5  5150.9  5151.7  5164.1  5172.6  5176.4  5178.8  5197.2
 2385.89 2367.74 2366.91 2365.03 2363.14  2362.5 2362.38 2362.41 2362.34 2363.25
 2363.12 2361.78 2362.24 2362.28 2362.15  2362.2    2363  2363.4 2362.73 2363.75
 2363.67  2364.6 2364.62 2364.62 2364.76 2364.76  2364.7 2365.97  2366.3  2367.4
 2367.82 2368.16 2368.81 2368.97 2369.47 2374.33 2375.25 2381.07 2382.85 2384.82
 2389.81 2396.95 2397.31 2400.84 2403.35 2404.56  2405.5 2410.31
  2333.6  2333.6  2333.6  2333.6  2333.6  2333.6  2333.6  2333.6  2333.6  2333.6
  2333.6  2333.6  2333.6  2333.6  2333.6  2333.6  2333.6  2333.6  2333.6  2333.6
  2333.6  2333.6  2333.6  2362.6  2362.6  2333.6  2333.6  2333.6  2333.6  2333.6
  2333.6  2333.6  2333.6  2333.6  2333.6  2333.6  2333.6  2333.6  2333.6  2333.6
  2333.6  2333.6  2333.6  2333.6  2333.6  2333.6  2333.6  2333.6
BR Coef= 1 , 1 , 0 ,1.25, 0 ,,,0.8,0,2,0,
WSPro=,,,, 1 ,,,, 0 ,,,, 0 ,,,,-1 ,-1 ,-1 , 0 , 0 , 0 , 0 , 0
BC Design=,, 0 ,, 0 ,,,,,,
BC HTab HWMax=2410.85