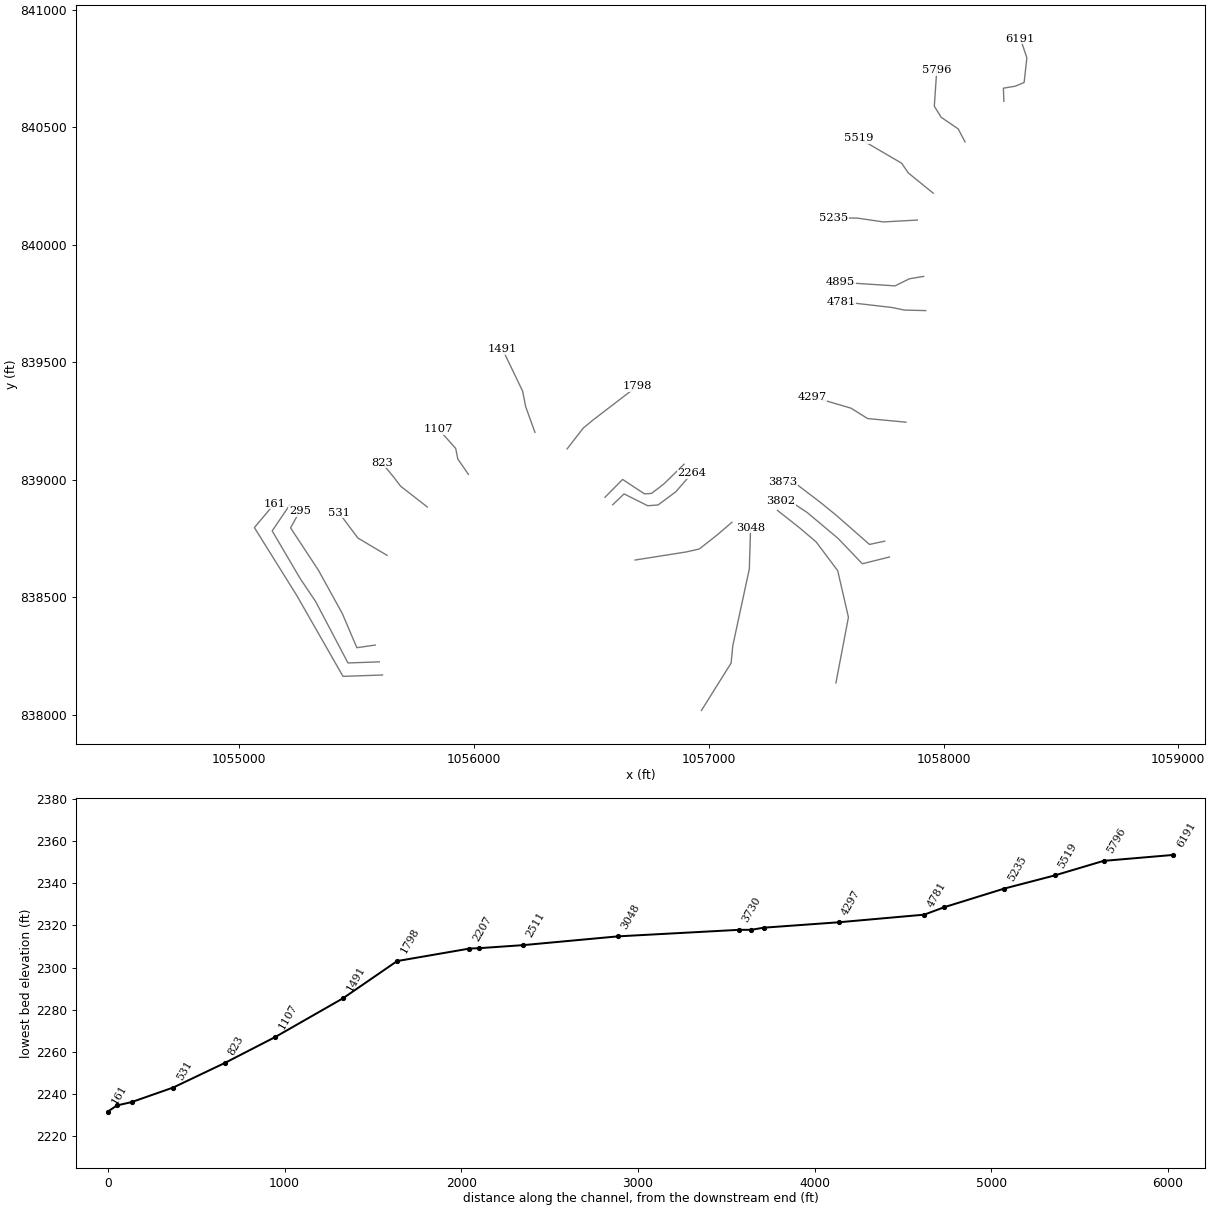
HEC-RAS study lds_cane_crk_lower.prj: Cane Creek Limited Detail Study

--- lds_cane_crk_lower.g01 (geometry) --- (continued)

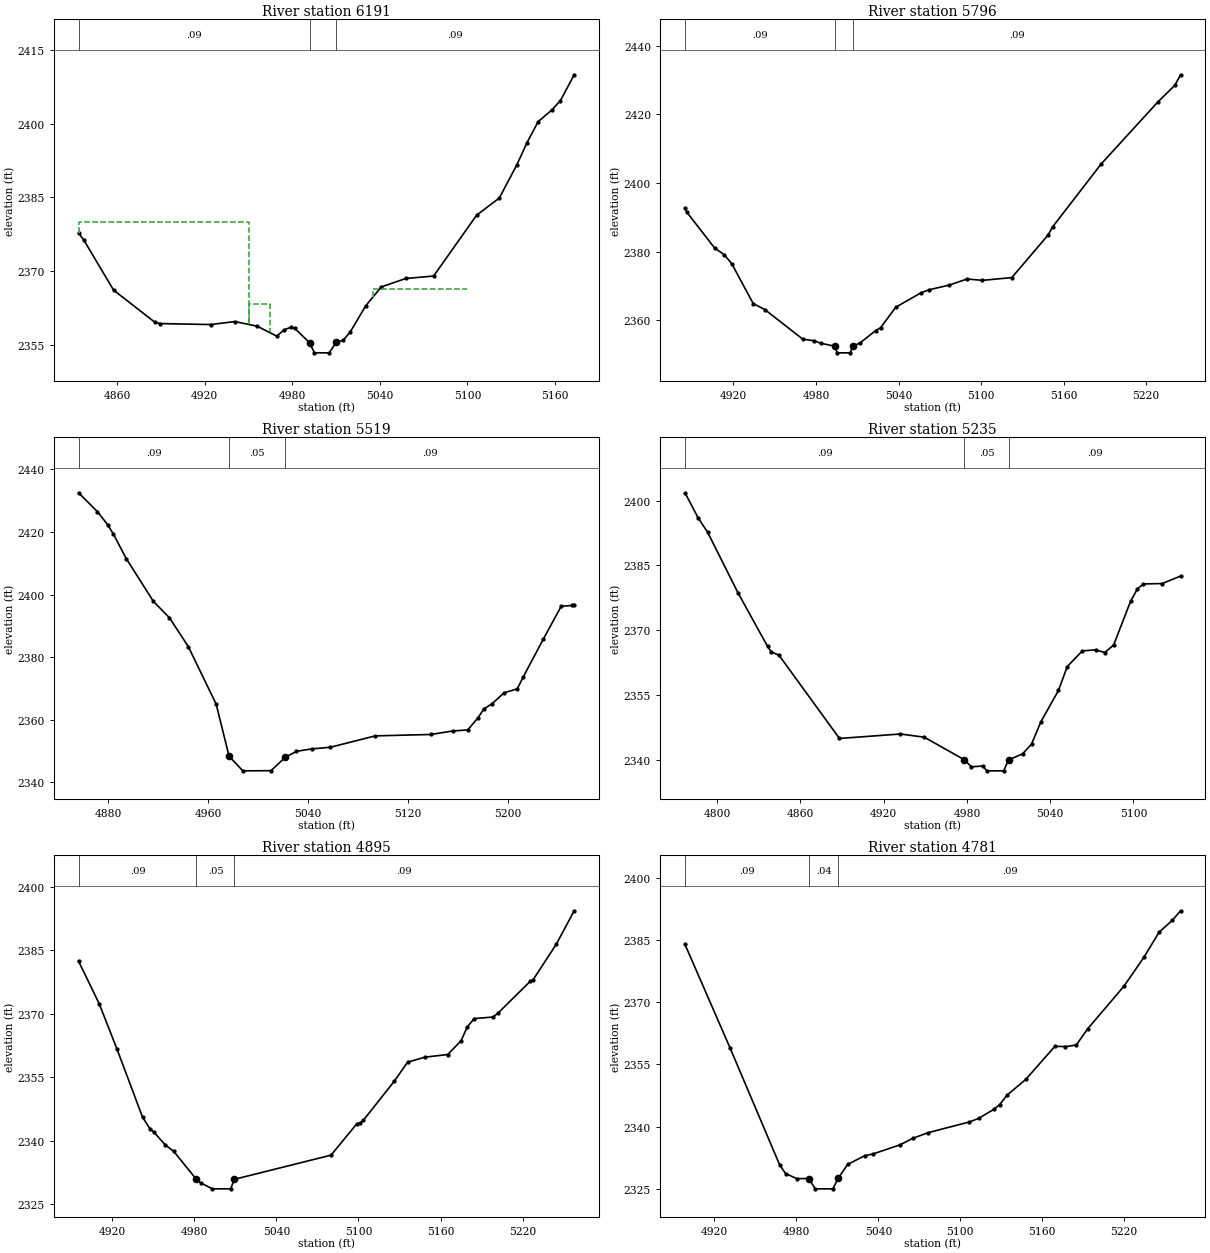
Type RM Length L Ch R = 1 ,6191    ,395,395,395
BEGIN DESCRIPTION:
XS 24
END DESCRIPTION:
XS GIS Cut Line= 6
      1058257.17       840609.74      1058255.06       840665.53
      1058305.59       840673.96      1058343.49       840689.75
      1058355.07       840795.03       1058327.7       840876.09
#Sta/Elev= 30
  4833.5 2377.75  4837.1 2376.33  4857.5 2366.13  4885.8 2359.58  4889.4 2359.31
  4924.1 2359.11  4940.6 2359.72  4955.9 2358.78  4969.3 2356.75  4974.3 2358.01
    4979 2358.57  4981.7 2358.32  4991.8 2355.42  4995.1 2353.35  5005.3 2353.35
    5010 2355.49  5014.7 2355.88  5019.6 2357.56  5030.2 2362.89  5040.9 2366.76
  5057.7 2368.49  5076.8 2368.99  5106.3 2381.39  5121.8 2384.87  5133.7 2391.56
  5140.6 2396.03  5148.4 2400.43  5157.6 2402.74  5163.7 2404.73  5173.1 2409.97
#Mann= 3 ,-1 , 0
  4833.5     .09       0  4991.8     .05       0    5010     .09       0
#XS Ineff= 3 ,-1
    4800    4950    2380    4950  4964.4 2363.26    5035    5100  2366.3
Permanent Ineff=
       F       F       F
Bank Sta=4991.8,5010
Exp/Cntr=0.5,0.3

Type RM Length L Ch R = 1 ,5796    ,277,277,277
BEGIN DESCRIPTION:
XS 23
END DESCRIPTION:
XS GIS Cut Line= 5
      1058091.78       840436.81      1058062.56       840492.22
      1057990.01       840541.59      1057960.79       840588.95
      1057971.23       840742.71
#Sta/Elev= 30
  4884.8 2392.69  4886.1 2391.53  4906.4 2381.04  4913.5 2379.07  4918.8 2376.49
  4934.4 2364.87  4942.8 2363.14  4970.4 2354.51  4978.8 2354.02  4983.4 2353.32
  4993.6 2352.46  4995.4 2350.52  5004.9 2350.52    5007 2352.49    5012  2353.4
  5023.3 2356.98    5027 2357.86  5037.9 2363.79  5056.2 2367.99  5062.3 2368.91
  5076.8 2370.26  5089.8 2372.04    5101 2371.65  5122.3 2372.45  5148.6 2384.82
    5152 2387.25  5187.3 2405.59  5228.3 2423.57  5240.7 2428.46    5245 2431.56
#Mann= 3 ,-1 , 0
  4884.8     .09       0  4993.6     .05       0    5007     .09       0
Bank Sta=4993.6,5007
Exp/Cntr=0.3,0.1

Type RM Length L Ch R = 1 ,5519    ,284,284,284
BEGIN DESCRIPTION:
XS 22
END DESCRIPTION:
XS GIS Cut Line= 4
      1057956.14       840218.69      1057849.96       840304.82
      1057821.75       840346.13      1057640.39       840451.92
#Sta/Elev= 30
  4856.2 2432.53  4871.3 2426.52  4879.7 2422.22  4884.2 2419.27  4894.4 2411.49
  4916.2 2397.77    4929 2392.56  4944.1 2383.33  4966.4 2364.92  4976.7 2348.29
  4987.7 2343.62  5010.3 2343.67  5021.5  2347.9  5030.6 2349.86    5043 2350.64
  5057.8 2351.16  5093.7  2354.8  5138.4 2355.25  5155.6 2356.36  5167.7  2356.7
  5175.9 2360.54  5180.6 2363.41  5187.4 2365.15  5196.8 2368.58  5207.4 2369.84
    5212 2373.55  5228.2 2385.73  5242.5 2396.22  5251.2  2396.5  5252.9  2396.8
#Mann= 3 ,-1 , 0
  4856.2     .09       0  4976.7     .05       0  5021.5     .09       0
Bank Sta=4976.7,5021.5
Exp/Cntr=0.3,0.1

Type RM Length L Ch R = 1 ,5235    ,340,340,340
BEGIN DESCRIPTION:
XS 21
END DESCRIPTION:
XS GIS Cut Line= 4
      1057888.25       840104.31      1057744.17       840096.25
      1057634.34       840112.37      1057532.58       840114.39
#Sta/Elev= 30
  4776.9 2401.81  4786.4 2395.99  4793.2 2392.68    4815  2378.7  4836.4 2366.23
  4838.9 2365.01  4844.7 2364.16  4888.2 2344.92  4932.1 2345.95  4949.3 2345.21
  4978.1    2340  4983.2 2338.36  4991.6 2338.53  4994.3 2337.42  5006.5 2337.42
    5010 2339.95  5020.1 2341.34  5026.6 2343.62  5033.4 2348.83    5046 2356.04
  5052.3 2361.56  5063.2  2365.2  5072.8 2365.43  5079.3 2364.82  5085.7 2366.54
  5097.9 2376.64  5102.8 2379.53  5107.2  2380.7  5120.7 2380.79    5134 2382.52
#Mann= 3 ,-1 , 0
  4776.9     .09       0  4978.1     .05       0    5010     .09       0
Bank Sta=4978.1,5010
Exp/Cntr=0.3,0.1

Type RM Length L Ch R = 1 ,4895    ,114,114,114
BEGIN DESCRIPTION:
XS 20
END DESCRIPTION:
XS GIS Cut Line= 4
      1057915.45       839864.51        1057855.       839854.43
      1057793.54       839824.21      1057561.51       839839.16
#Sta/Elev= 30
  4895.4 2382.46  4910.5 2372.39  4923.5 2361.67  4942.2 2345.55  4947.9 2342.66
  4950.3 2342.08  4958.9 2338.95  4964.9 2337.49  4981.6 2330.82  4984.8 2329.98
  4993.3 2328.59  5006.6 2328.59  5009.3 2330.84    5080 2336.56  5098.9 2344.01
  5100.9 2344.09  5103.5 2344.76  5126.3 2354.09  5135.9 2358.54  5148.5 2359.73
  5165.3 2360.36    5175 2363.61  5179.7 2366.98  5184.7 2368.86  5198.3 2369.22
  5201.9 2370.11  5225.6 2377.68  5227.7 2378.04  5244.6 2386.44  5257.7 2394.36
#Mann= 3 ,-1 , 0
  4895.4     .09       0  4981.6     .05       0  5009.3     .09       0
Bank Sta=4981.6,5009.3
Exp/Cntr=0.3,0.1

Type RM Length L Ch R = 1 ,4781    ,484,484,484
BEGIN DESCRIPTION:
XS 19
END DESCRIPTION:
XS GIS Cut Line= 4
      1057923.92       839718.96      1057833.36       839721.16
      1057780.34       839732.21      1057563.66       839757.21
#Sta/Elev= 30
  4898.4 2383.91  4931.4 2358.98  4967.7 2330.83  4972.1 2328.71  4980.3  2327.5
    4989 2327.52  4993.8 2325.04  5006.7 2325.04  5010.6  2327.6  5017.5 2330.92
    5030 2333.02  5036.2 2333.45  5055.9 2335.65    5065 2337.18  5076.4 2338.57
  5106.7 2341.15  5113.4 2342.01  5124.8 2344.24  5128.7 2345.31  5134.4 2347.65
  5147.9 2351.39  5169.3 2359.38    5177 2359.29  5184.9 2359.68  5193.2 2363.57
  5219.8 2373.84  5234.4  2380.8  5245.5 2386.84  5255.2 2389.71  5261.3 2392.01
#Mann= 3 ,-1 , 0
  4898.4     .09       0    4989     .04       0  5010.6     .09       0
Bank Sta=4989,5010.6
Exp/Cntr=0.3,0.1

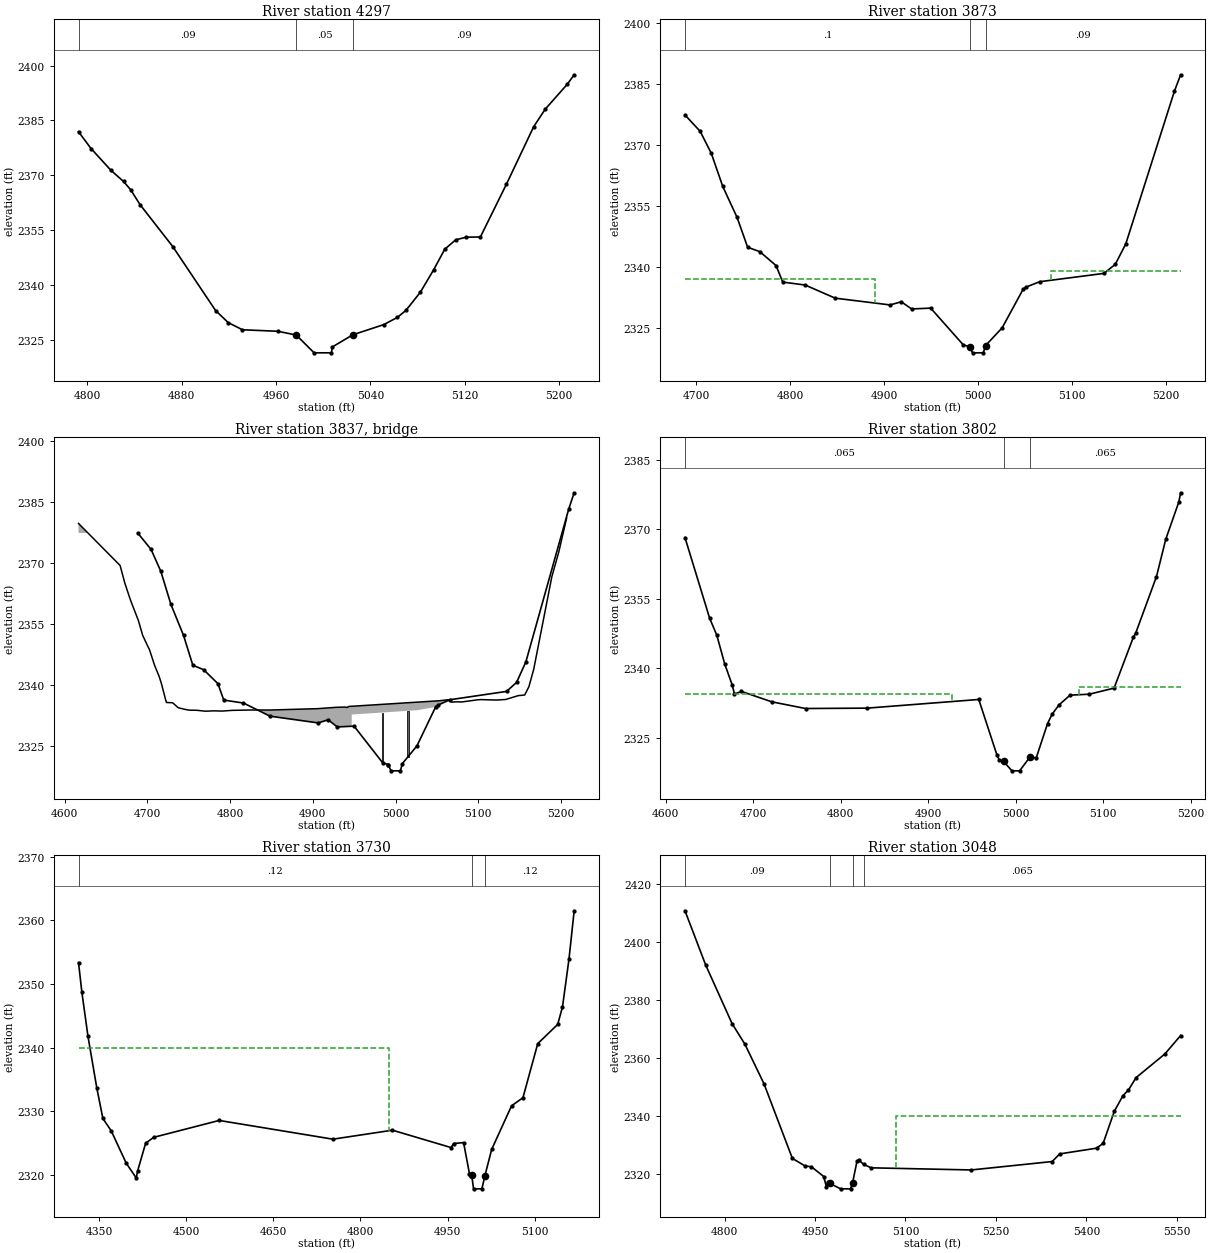
Type RM Length L Ch R = 1 ,4297    ,424,424,424
BEGIN DESCRIPTION:
XS 18
END DESCRIPTION:
XS GIS Cut Line= 4
      1057839.98       839244.04      1057676.53       839259.51
      1057605.84       839303.68      1057440.17       839352.28
#Sta/Elev= 30
  4792.6 2381.92  4803.2 2377.32  4820.1 2371.35  4830.8  2368.3  4836.7 2366.09
  4844.7    2362  4872.5  2350.5  4908.8 2333.01  4919.5  2329.7  4931.6 2327.74
  4961.6 2327.33  4977.2  2326.3  4992.3 2321.44    5007 2321.43  5007.8 2323.04
 5025.07 2326.36  5051.3 2329.14  5062.9 2331.12  5070.1 2333.02  5082.4 2338.01
  5093.8 2344.22  5103.1 2349.78  5112.4 2352.35  5121.3 2353.06  5133.3 2353.12
  5155.3 2367.51  5178.5  2383.3  5188.3  2388.1    5207 2394.91  5212.8 2397.49
#Mann= 3 , 0 , 0
  4792.6     .09       0  4977.2     .05       0 5025.07     .09       0
Bank Sta=4977.2,5025.07
Exp/Cntr=0.5,0.3

Type RM Length L Ch R = 1 ,3873    ,71,71,71
BEGIN DESCRIPTION:
XS 17
END DESCRIPTION:
XS GIS Cut Line= 6
      1057749.72       838737.77      1057684.51        838723.8
      1057542.46       838848.39      1057474.93       838903.11
      1057377.12       838977.63      1057316.57       838991.61
#Sta/Elev= 30
  4688.2 2377.45  4704.4  2373.4  4716.2 2368.01  4728.4 2359.86  4743.7  2352.2
  4754.9 2344.87  4767.9 2343.78  4785.2 2340.35  4792.3 2336.29  4816.1 2335.57
  4848.2 2332.33  4906.5 2330.67  4918.5 2331.44  4929.5 2329.68  4949.8 2329.88
  4984.6  2320.8  4991.2 2320.42  4991.3 2320.37  4994.4 2318.87  5005.8 2318.87
  5008.2 2320.65  5025.9 2325.04  5048.4 2334.61  5051.4 2335.06  5065.7 2336.38
  5134.2 2338.43  5146.3 2340.65  5157.5 2345.69  5209.3 2383.31  5215.9 2387.34
#Mann= 3 ,-1 , 0
  4688.2      .1       0  4991.3     .05       0  5008.2     .09       0
#XS Ineff= 2 , 0
       0    4890    2337  5077.7       0    2339
Permanent Ineff=
       T       F
Bank Sta=4991.2,5008.2
Exp/Cntr=0.5,0.3

Type RM Length L Ch R = 3 ,3837    ,,,
BEGIN DESCRIPTION:
XS 16 TOR
Structure ID: XS 16
Approximate Survey Structure
END DESCRIPTION:
Bridge Culvert--1,0,-1,-1, 0
Deck Dist Width WeirC Skew NumUp NumDn MinLoCord MaxHiCord MaxSubmerge Is_Ogee
21,30,3,0, 49, 49, , , , 0, 1,1,,
  4616.7    4667  4672.5  4678.8  4680.9    4689  4694.3  4700.9  4702.4  4708.6
  4714.2  4716.9  4721.7    4723  4730.5  4737.3  4745.2  4750.6  4759.7    4770
  4780.2  4790.6  4802.3    4824  4848.4  4905.6  4928.8    4939  4941.1  4943.6
    4947    4947    5053    5053  5063.4  5068.3  5074.4    5080  5099.5  5103.3
  5122.1  5133.1  5148.3  5156.1  5161.2    5167  5188.9  5197.3  5206.8
 2379.79 2369.43 2365.23 2361.35 2360.18 2355.93 2352.21 2349.35 2348.77 2344.89
  2342.1 2340.37 2336.62  2335.7 2335.63  2334.4 2334.01 2333.81 2333.78 2333.56
 2333.64 2333.59 2333.76 2333.85 2333.85 2334.18 2334.52 2334.57 2334.47 2334.73
 2334.77 2334.77 2336.13 2336.13 2336.38  2335.8 2335.87 2335.83 2336.37 2336.41
  2336.3 2336.44 2337.39 2337.54  2339.6 2343.87 2366.67 2372.76 2381.13
 2298.89 2298.89 2298.89 2298.89 2298.89 2298.89 2298.89 2298.89 2298.89 2298.89
 2298.89 2298.89 2298.89 2298.89 2298.89 2298.89 2298.89 2298.89 2298.89 2298.89
 2298.89 2298.89 2298.89 2298.89 2298.89 2298.89 2298.89 2298.89 2298.89 2298.89
 2298.89 2332.73 2334.16 2298.89 2298.89 2298.89 2298.89 2298.89 2298.89 2298.89
 2298.89 2298.89 2298.89 2298.89 2298.89 2298.89 2298.89 2298.89 2298.89
  4616.7    4667  4672.5  4678.8  4680.9    4689  4694.3  4700.9  4702.4  4708.6
  4714.2  4716.9  4721.7    4723  4730.5  4737.3  4745.2  4750.6  4759.7    4770
  4780.2  4790.6  4802.3    4824  4848.4  4905.6  4928.8    4939  4941.1  4943.6
    4947    4947    5053    5053  5063.4  5068.3  5074.4    5080  5099.5  5103.3
  5122.1  5133.1  5148.3  5156.1  5161.2    5167  5188.9  5197.3  5206.8
 2379.79 2369.43 2365.23 2361.35 2360.18 2355.93 2352.21 2349.35 2348.77 2344.89
  2342.1 2340.37 2336.62  2335.7 2335.63  2334.4 2334.01 2333.81 2333.78 2333.56
 2333.64 2333.59 2333.76 2333.85 2333.85 2334.18 2334.52 2334.57 2334.47 2334.73
 2334.77 2334.77 2336.13 2336.13 2336.38  2335.8 2335.87 2335.83 2336.37 2336.41
  2336.3 2336.44 2337.39 2337.54  2339.6 2343.87 2366.67 2372.76 2381.13
 2298.89 2298.89 2298.89 2298.89 2298.89 2298.89 2298.89 2298.89 2298.89 2298.89
 2298.89 2298.89 2298.89 2298.89 2298.89 2298.89 2298.89 2298.89 2298.89 2298.89
 2298.89 2298.89 2298.89 2298.89 2298.89 2298.89 2298.89 2298.89 2298.89 2298.89
 2298.89 2332.73 2334.16 2298.89 2298.89 2298.89 2298.89 2298.89 2298.89 2298.89
 2298.89 2298.89 2298.89 2298.89 2298.89 2298.89 2298.89 2298.89 2298.89
Pier Skew, UpSta & Num, DnSta & Num=  ,4984, 2 ,4984, 2 , 0 , 0 , 0 ,,
       2       2
    2330 2334.16
       2       2
    2330 2334.16
Pier Skew, UpSta & Num, DnSta & Num=  ,5015, 2 ,5015, 2 , 0 , 0 , 0 ,,
       2       2
    2330 2334.16
       2       2
    2330 2334.16
BR Coef= 1 , 1 , 0 ,1.25, 0 ,,,0.8,0,2,0,
WSPro=,,,, 1 ,,,, 0 ,,,, 0 ,,,,-1 ,-1 ,-1 , 0 , 0 , 0 , 0 , 0
BC Design=,, 0 ,, 0 ,,,,,,
BC HTab HWMax=2387.34

Type RM Length L Ch R = 1 ,3802    ,72,72,72
BEGIN DESCRIPTION:
XS 15 manning n values used to fix drawdown
END DESCRIPTION:
XS GIS Cut Line= 6
      1057769.51       838670.24      1057654.15       838641.54
      1057550.72       838749.46      1057419.19       838859.63
      1057356.24       838901.23      1057305.65       838910.22
#Sta/Elev= 30
    4622  2368.2  4650.2 2350.79  4658.3 2347.17  4667.5 2340.89  4675.9 2336.45
  4678.6 2334.45  4686.6 2334.99  4721.3 2332.75  4759.8 2331.31  4830.1 2331.39
  4957.9 2333.26 4978.58 2321.33  4981.5 2320.17 4986.32 2319.88  4995.8 2317.86
  5004.6 2317.86 5016.08 2320.75  5023.6 2320.66  5036.5 2328.04  5041.6 2330.02
  5049.6 2332.09  5062.3 2334.19  5084.3  2334.4  5112.6 2335.71  5134.6 2346.67
  5137.3 2347.56  5161.1 2359.79  5171.7 2367.83  5186.6 2375.86  5188.7 2377.86
#Mann= 3 ,-1 , 0
    4622    .065       0 4986.32    .055       0 5016.08    .065       0
#XS Ineff= 2 , 0
       0  4927.1 2334.45    5073       0 2335.85
Permanent Ineff=
       F       F
Bank Sta=4986.32,5016.08
Exp/Cntr=0.5,0.3

Type RM Length L Ch R = 1 ,3730    ,682,682,682
BEGIN DESCRIPTION:
XS 14
END DESCRIPTION:
XS GIS Cut Line= 6
      1057541.59       838134.44      1057594.94        838413.9
      1057549.21       838612.06      1057457.75       838734.01
      1057389.16       838792.44      1057292.62       838868.65
#Sta/Elev= 30
  4314.5 2353.38  4320.3 2348.71  4330.8 2341.79  4345.9 2333.73  4356.4 2328.91
  4370.8 2326.95  4396.7 2321.87    4414 2319.53  4416.1 2320.59  4430.1 2325.01
    4444 2325.93  4556.7 2328.58  4752.6 2325.64  4855.1 2327.05  4956.1 2324.32
  4960.4 2324.96  4977.6  2325.1  4987.7 2320.21  4991.6 2319.94  4994.8 2317.84
  5009.1 2317.84  5014.4 2319.93  5025.9 2324.02  5060.2 2330.88  5079.8 2332.15
  5105.3 2340.65  5139.6 2343.66  5147.9 2346.41  5159.1 2353.94    5168 2361.51
#Mann= 3 ,-1 , 0
  4314.5     .12       0  4991.6    .055       0  5014.4     .12       0
#XS Ineff= 2 , 0
       0    4850    2340               0
Permanent Ineff=
       F       F
Bank Sta=4991.6,5014.4
Exp/Cntr=0.3,0.1

Type RM Length L Ch R = 1 ,3048    ,537,537,537
BEGIN DESCRIPTION:
XS 13
END DESCRIPTION:
XS GIS Cut Line= 5
      1056968.48       838016.96      1057095.03       838218.85
      1057102.25       838292.86      1057172.65       838619.58
      1057178.06       838794.68
#Sta/Elev= 30
  4734.3 2410.91  4768.7 2392.13  4812.6 2371.82  4833.6 2364.82  4865.4 2351.06
  4912.4 2325.29  4933.1  2322.7    4944 2322.38  4964.5 2319.01    4969 2315.25
    4971 2317.03  4974.4 2316.64  4992.4 2314.76  5008.9 2314.76  5012.3 2316.89
  5019.5 2324.24  5022.9 2324.64  5030.7 2323.21    5043 2322.03  5209.1 2321.29
  5343.3  2324.2  5355.7 2326.84  5416.9 2328.82  5427.8 2330.48  5446.3 2341.58
  5460.6 2346.97  5469.8 2348.94  5482.4 2353.22  5530.1 2361.38  5556.3 2367.77
#Mann= 4 ,-1 , 0
  4734.3     .09       0  4974.4     .05       0  5012.3     .09       0
  5030.7    .065       0
#XS Ineff= 2 , 0
       0                    5085       0    2340
Permanent Ineff=
       F       F
Bank Sta=4974.4,5012.3
Exp/Cntr=0.3,0.1

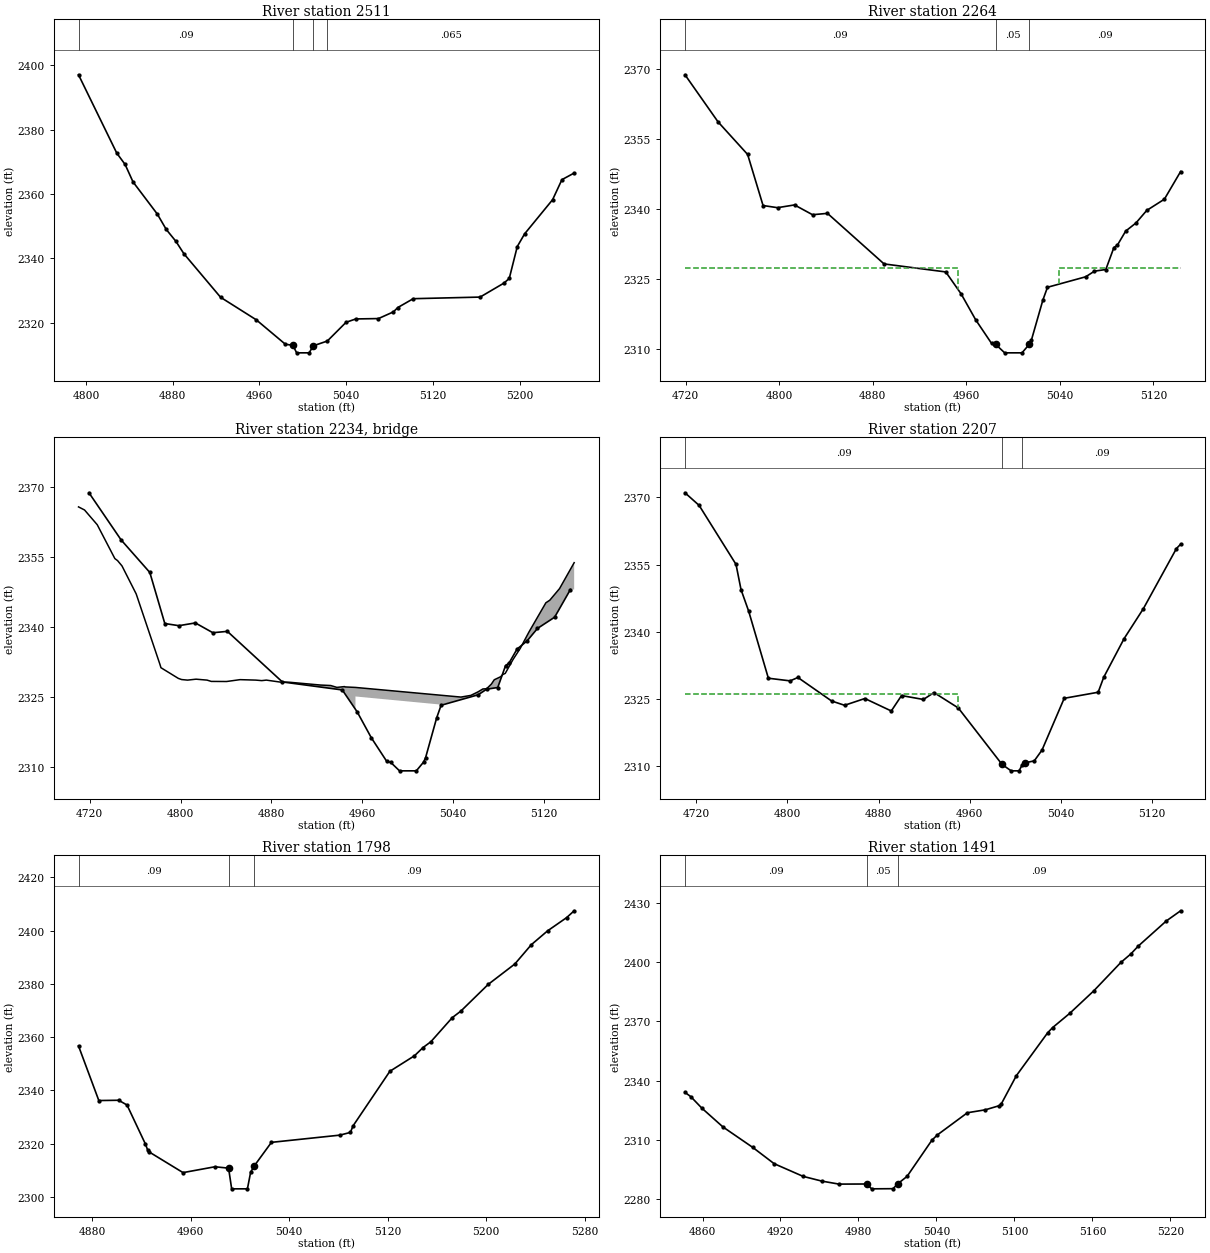
Type RM Length L Ch R = 1 ,2511    ,247,247,247
BEGIN DESCRIPTION:
XS 12
END DESCRIPTION:
XS GIS Cut Line= 5
      1056685.99       838657.42      1056903.69       838691.79
      1056959.64       838704.42      1057035.46       838763.99
      1057098.64       838818.14
#Sta/Elev= 30
    4793 2397.08  4828.3 2372.72    4836 2369.19  4843.3 2363.76  4865.7 2353.77
    4874 2348.96  4882.9 2345.27  4890.3  2341.4  4924.1 2327.88    4957 2320.88
  4983.9 2313.27  4990.8 2312.95  4994.3  2310.6  5005.9  2310.6  5009.5 2312.77
  5022.6 2314.27  5039.9  2320.1  5048.9 2321.14  5069.8 2321.26  5083.6 2323.34
  5087.7  2324.7  5101.9 2327.44  5163.6 2327.94  5185.5 2332.27  5190.5 2333.73
  5197.9 2343.66  5204.7 2347.62  5230.5 2358.23  5239.1 2364.46  5250.4 2366.52
#Mann= 4 ,-1 , 0
    4793     .09       0  4990.8     .05       0  5009.5     .09       0
  5022.6    .065       0
Bank Sta=4990.8,5009.5
Exp/Cntr=0.5,0.3

Type RM Length L Ch R = 1 ,2264    ,57,57,57
BEGIN DESCRIPTION:
XS 11
END DESCRIPTION:
XS GIS Cut Line= 6
      1056590.63       838892.66       1056638.9       838938.87
      1056739.55       838888.55      1056783.71       838891.63
      1056859.71       838948.12      1056928.52        839027.2
#Sta/Elev= 30
  4719.3 2368.84  4747.6 2358.73  4772.9 2351.74  4786.1 2340.78  4798.5 2340.32
    4813 2340.91  4828.4 2338.81  4841.2  2339.1  4889.6 2328.25  4942.4 2326.53
  4955.5 2321.83    4968 2316.25  4981.6 2311.18    4985    2311  4992.8 2309.17
  5007.6 2309.17    5014 2311.05  5015.7 2311.95  5025.5 2320.53  5029.4 2323.24
  5062.1 2325.49  5069.6  2326.7  5079.3 2327.05  5086.2 2331.76  5089.2 2332.28
  5096.3  2335.3  5105.1 2337.04  5114.3 2339.73  5129.4 2342.14  5143.3 2348.08
#Mann= 3 ,-1 , 0
  4719.3     .09       0    4985     .05       0    5014     .09       0
#XS Ineff= 2 , 0
       0 4953.14 2327.46 5038.91       0 2327.46
Permanent Ineff=
       F       F
Bank Sta=4985,5014
Exp/Cntr=0.5,0.3

Type RM Length L Ch R = 3 ,2234    ,,,
BEGIN DESCRIPTION:
XS 10 TOR
Structure ID: XS 10
Approximate Survey Structure
END DESCRIPTION:
Bridge Culvert--1,0,-1,-1, 0
Deck Dist Width WeirC Skew NumUp NumDn MinLoCord MaxHiCord MaxSubmerge Is_Ogee
16,28,3,0, 48, 48, , , , 0, 1,1,,
  4710.1  4715.4  4726.6  4742.1  4744.5  4748.4  4760.9  4781.8  4782.7    4798
  4800.9  4806.1  4813.6  4823.3    4827  4840.5  4852.4  4866.2  4871.5  4875.5
  4887.9  4895.9  4923.3  4932.2  4937.6  4944.4  4944.8    4954    4954    5046
    5046  5046.9  5055.6  5062.1  5066.2  5069.5  5073.7  5076.2  5081.8  5083.9
  5085.9  5092.8  5099.1  5106.8  5121.7  5125.1  5133.7  5146.6
 2365.81 2365.15 2361.98 2354.72 2354.28 2353.14 2347.13 2332.02  2331.3 2329.01
 2328.76 2328.64 2328.84 2328.64 2328.36 2328.34 2328.74 2328.64 2328.53 2328.64
 2328.21 2328.18 2327.58 2327.48 2327.08 2327.25 2327.18 2327.07 2327.07 2325.02
 2325.02    2325 2325.36 2326.14 2326.74 2326.79 2327.79 2328.71 2329.36 2329.86
 2330.08 2333.08 2335.44 2338.97 2345.24 2345.78 2348.27 2353.84
    2289    2289    2289    2289    2289    2289    2289    2289    2289    2289
    2289    2289    2289    2289    2289    2289    2289    2289    2289    2289
    2289    2289    2289    2289    2289    2289    2289    2289 2325.13    2323
    2289    2289    2289    2289    2289    2289    2289    2289    2289    2289
    2289    2289    2289    2289    2289    2289    2289    2289
  4710.1  4715.4  4726.6  4742.1  4744.5  4748.4  4760.9  4781.8  4782.7    4798
  4800.9  4806.1  4813.6  4823.3    4827  4840.5  4852.4  4866.2  4871.5  4875.5
  4887.9  4895.9  4923.3  4932.2  4937.6  4944.4  4944.8    4954    4954    5046
    5046  5046.9  5055.6  5062.1  5066.2  5069.5  5073.7  5076.2  5081.8  5083.9
  5085.9  5092.8  5099.1  5106.8  5121.7  5125.1  5133.7  5146.6
 2365.81 2365.15 2361.98 2354.72 2354.28 2353.14 2347.13 2332.02  2331.3 2329.01
 2328.76 2328.64 2328.84 2328.64 2328.36 2328.34 2328.74 2328.64 2328.53 2328.64
 2328.21 2328.18 2327.58 2327.48 2327.08 2327.25 2327.18 2327.07 2327.07 2325.02
 2325.02    2325 2325.36 2326.14 2326.74 2326.79 2327.79 2328.71 2329.36 2329.86
 2330.08 2333.08 2335.44 2338.97 2345.24 2345.78 2348.27 2353.84
    2289    2289    2289    2289    2289    2289    2289    2289    2289    2289
    2289    2289    2289    2289    2289    2289    2289    2289    2289    2289
    2289    2289    2289    2289    2289    2289    2289    2289 2325.13    2323
    2289    2289    2289    2289    2289    2289    2289    2289    2289    2289
    2289    2289    2289    2289    2289    2289    2289    2289
BR Coef= 1 , 1 , 0 ,1.25, 0 ,,,0.8,0,2,0,
WSPro=,,,, 1 ,,,, 0 ,,,, 0 ,,,,-1 ,-1 ,-1 , 0 , 0 , 0 , 0 , 0
BC Design=,, 0 ,, 0 ,,,,,,
BC HTab HWMax=2368.84

Type RM Length L Ch R = 1 ,2207    ,409,409,409
BEGIN DESCRIPTION:
XS 9
END DESCRIPTION:
XS GIS Cut Line= 6
      1056557.76        838924.5      1056632.74        839000.5
      1056726.13       838938.85      1056755.98       838940.93
      1056808.36       838980.98      1056894.63        839065.2
#Sta/Elev= 30
  4710.1 2371.03  4722.5 2368.22  4754.9 2355.05  4759.3 2349.41    4766 2344.62
  4783.3 2329.64  4802.4 2329.05  4809.2 2329.81  4838.8 2324.56  4850.2  2323.6
    4868 2325.11  4891.2 2322.33  4900.2 2325.77  4919.4  2324.9  4928.7 2326.44
    4950 2323.01  4988.4 2310.41  4996.4 2308.97  5003.4 2308.97  5006.1 2310.32
  5008.9 2310.78  5016.7 2311.19  5023.5  2313.6    5043 2325.16  5072.8 2326.51
  5077.7 2329.86  5095.6 2338.49  5112.5 2345.17  5141.5 2358.58  5145.2 2359.55
#Mann= 3 ,-1 , 0
  4710.1     .09       0  4988.4     .05       0  5006.1     .09       0
#XS Ineff= 2 , 0
       0    4950 2326.15    5050       0 2324.28
Permanent Ineff=
       F       F
Bank Sta=4988.4,5008.9
Exp/Cntr=0.5,0.3

Type RM Length L Ch R = 1 ,1798    ,307,307,307
BEGIN DESCRIPTION:
XS 8
END DESCRIPTION:
XS GIS Cut Line= 4
      1056396.45       839130.43      1056465.04       839218.88
      1056506.56       839253.17      1056694.61       839397.08
#Sta/Elev= 30
  4868.8 2356.72  4885.3 2336.21  4901.4 2336.32  4908.2 2334.53  4923.2 2319.82
  4924.9  2317.7  4926.1 2316.93  4953.7 2309.14  4979.6 2311.34  4990.7 2310.82
  4993.2 2303.05    5006 2303.05  5008.6 2309.27  5011.7 2311.76  5025.5 2320.51
  5081.1 2323.22  5089.7 2324.25  5091.7 2326.63  5121.7  2347.2  5141.7 2353.03
  5148.6  2356.1    5155 2358.29  5172.4 2367.35  5179.4 2369.82  5201.6 2379.84
  5223.2 2387.49  5236.6 2394.74  5249.8 2399.94  5265.3 2404.92  5271.4 2407.48
#Mann= 3 ,-1 , 0
  4868.8     .09       0  4990.7     .05       0  5011.7     .09       0
Bank Sta=4990.7,5011.7
Exp/Cntr=0.3,0.1

Type RM Length L Ch R = 1 ,1491    ,384,384,384
BEGIN DESCRIPTION:
XS 7
END DESCRIPTION:
XS GIS Cut Line= 4
      1056259.26       839200.83      1056219.55       839310.94
      1056206.91       839375.92        1056121.        839554.5
#Sta/Elev= 30
  4846.5 2334.13    4851 2331.97  4859.5 2326.16  4875.7 2316.67  4898.7  2306.3
  4915.1  2298.1  4937.4 2291.68  4951.8 2289.29    4965 2287.77  4986.5 2287.83
  4990.1 2285.38  5006.6 2285.46  5010.4 2288.03  5017.4 2291.68  5036.5 2309.96
  5040.8 2312.68  5063.8 2323.84  5077.7 2325.34  5088.4 2327.43  5089.8 2328.19
  5101.5 2342.59  5125.6 2364.28  5129.4  2366.9  5142.5 2374.05  5161.1 2385.49
  5181.9 2399.82  5189.6 2404.13  5195.3  2408.1  5216.9 2420.81  5227.9 2425.94
#Mann= 3 ,-1 , 0
  4846.5     .09       0  4986.5     .05       0  5010.4     .09       0
Bank Sta=4986.5,5010.4
Exp/Cntr=0.3,0.1

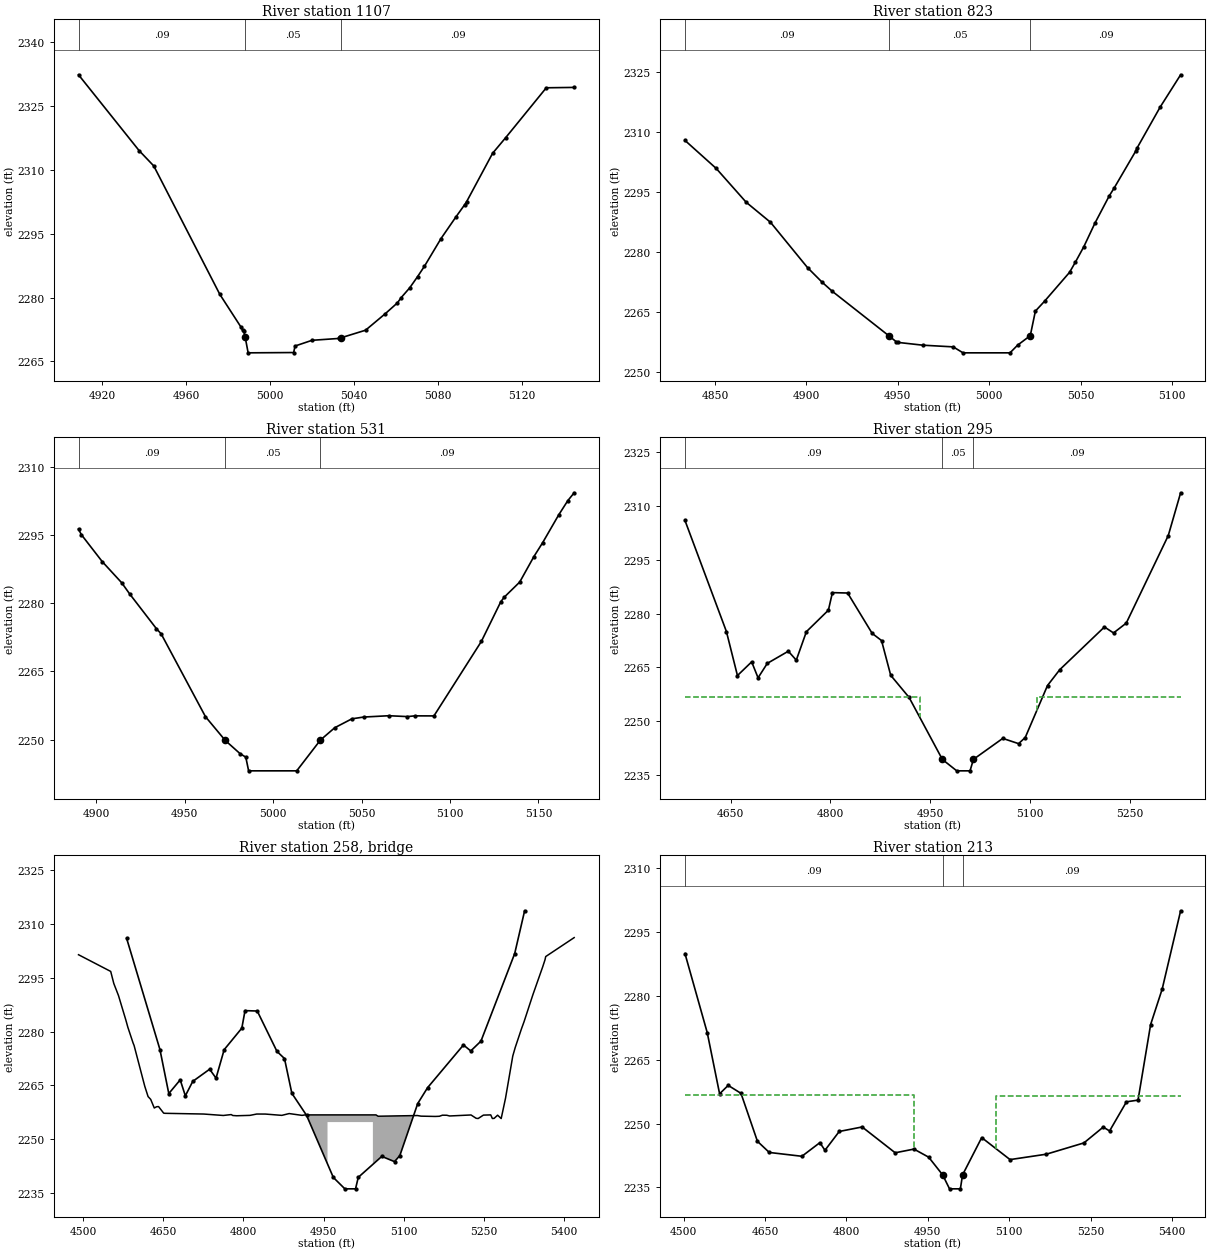
Type RM Length L Ch R = 1 ,1107    ,284,284,284
BEGIN DESCRIPTION:
XS 6
END DESCRIPTION:
XS GIS Cut Line= 4
      1055975.86       839022.12      1055930.73        839087.1
      1055921.71       839132.23       1055847.7       839215.27
#Sta/Elev= 29
  4908.6  2332.4  4937.5 2314.57  4944.5 2310.96    4976 2280.76  4986.1 2273.06
  4986.9 2272.29  4987.4 2272.09  4988.1  2270.7  4989.5 2267.01  5011.2 2267.08
  5011.9 2268.62    5020 2269.96  5032.9  2270.4  5033.8 2270.55  5045.5 2272.33
  5054.9 2276.21  5060.7 2278.76  5062.5    2280  5066.6 2282.32  5070.3 2284.92
  5073.6 2287.38  5081.5 2293.89  5088.5  2298.9  5092.8 2301.86  5093.7 2302.55
  5106.1 2313.94  5112.4 2317.65  5131.7 2329.34    5145 2329.43
#Mann= 3 ,-1 , 0
  4908.6     .09       0  4988.1     .05       0  5033.8     .09       0
Bank Sta=4988.1,5033.8
Exp/Cntr=0.3,0.1

Type RM Length L Ch R = 1 ,823     ,292,292,292
BEGIN DESCRIPTION:
XS 5
END DESCRIPTION:
XS GIS Cut Line= 4
      1055800.77       838883.13      1055687.04       838971.58
      1055658.16       839009.48      1055607.62       839070.86
#Sta/Elev= 28
  4833.5 2307.82  4850.6 2300.82    4867 2292.38  4880.3 2287.38  4900.6 2276.05
  4908.6  2272.4  4914.2 2270.12  4945.4 2258.93  4949.1 2257.56  4950.2 2257.38
  4963.7 2256.69  4980.3 2256.27  4985.7 2254.78  5011.4 2254.78  5015.6 2256.71
  5022.5 2259.07  5025.3  2265.2  5030.3 2267.66    5044 2274.88  5047.1 2277.35
  5051.8 2281.27  5057.9 2287.17  5065.7 2293.95  5068.5    2296  5080.1 2305.06
  5081.1 2306.04  5093.6 2316.15  5104.8 2324.21
#Mann= 3 ,-1 , 0
  4833.5     .09       0  4945.4     .05       0  5022.5     .09       0
Bank Sta=4945.4,5022.5
Exp/Cntr=0.3,0.1

Type RM Length L Ch R = 1 ,531     ,236,236,236
BEGIN DESCRIPTION:
XS 4
END DESCRIPTION:
XS GIS Cut Line= 4
      1055629.28       838677.34      1055549.86       838724.28
      1055504.73       838751.35       1055423.5       838859.66
#Sta/Elev= 30
  4889.9 2296.29  4891.5 2295.09  4903.3 2289.16  4914.3 2284.51  4918.8 2282.06
    4934 2274.38  4936.6 2273.29  4961.7 2255.05  4972.9 2249.82  4981.2 2246.94
  4984.5 2246.15  4986.1 2243.14  5013.3 2243.14  5026.7 2249.91  5034.8 2252.62
  5044.5 2254.58  5051.2 2254.97  5065.4 2255.26  5075.9 2255.07  5080.1 2255.23
  5090.9 2255.22  5117.7 2271.59  5128.7 2280.32  5130.7 2281.35  5139.4 2284.65
  5147.4 2290.24  5152.3 2293.27  5161.4 2299.39  5166.6 2302.56  5170.2 2304.29
#Mann= 3 ,-1 , 0
  4889.9     .09       0  4972.9     .05       0  5026.7     .09       0
Bank Sta=4972.9,5026.7
Exp/Cntr=0.5,0.3

Type RM Length L Ch R = 1 ,295     ,82,82,82
BEGIN DESCRIPTION:
XS 3
END DESCRIPTION:
XS GIS Cut Line= 6
      1055578.72       838295.57      1055500.58       838284.23
      1055438.92       838429.02      1055337.25        838613.3
       1055218.1       838794.41      1055257.81        838865.9
#Sta/Elev= 30
  4581.3  2305.9  4643.6    2275  4660.2 2262.74  4681.6 2266.55  4691.2 2262.11
  4705.1 2266.13  4736.7 2269.51  4748.7 2267.03  4763.9 2274.95    4797 2280.94
    4803 2285.82  4825.9 2285.71  4862.8 2274.48  4876.9 2272.48  4890.7 2262.81
  4918.3 2256.66  4968.4 2239.39    4990 2236.22    5010 2236.22  5015.1 2239.42
  5059.2 2245.25    5083 2243.79    5093 2245.49  5126.5 2259.97  5144.9 2264.37
  5212.1 2276.26  5225.8  2274.6  5244.9 2277.33  5308.1  2301.7  5326.7 2313.61
#Mann= 3 ,-1 , 0
  4581.3     .09       0  4968.4     .05       0  5015.1     .09       0
#XS Ineff= 2 , 0
       0  4934.4  2256.8    5110       0  2256.8
Permanent Ineff=
       F       F
Bank Sta=4968.4,5015.1
Exp/Cntr=0.5,0.3

Type RM Length L Ch R = 3 ,258     ,,,
BEGIN DESCRIPTION:
XS 2 TOR
Structure ID: XS 2
Approximate Survey Structure
END DESCRIPTION:
Bridge Culvert--1,0,-1,-1, 0
Deck Dist Width WeirC Skew NumUp NumDn MinLoCord MaxHiCord MaxSubmerge Is_Ogee
25.5,23,3,0, 60, 60, , , , 0, 1,1,,
  4491.1  4551.4  4557.2    4566  4579.8  4583.5  4593.3  4595.2  4615.2  4621.4
  4626.3    4633  4637.4    4641  4650.6  4653.2  4725.5  4762.3  4777.1  4780.1
  4787.4  4812.4  4824.9  4841.2  4871.9  4885.7  4909.7  4915.6  4957.5  4957.5
  5042.5  5042.5  5048.3  5052.2  5125.9  5132.7  5159.4  5167.1  5172.7  5180.9
  5186.2  5226.3  5235.8  5239.6  5249.5  5263.2  5266.3  5269.6  5276.1  5282.8
  5290.9  5304.5  5309.1  5320.8  5325.7  5342.1  5360.7  5364.9  5366.2  5419.5
 2301.38 2296.73 2293.37    2290 2283.18  2281.2 2276.82 2276.12 2264.77  2261.9
 2261.12 2258.72 2259.07 2259.12 2257.29 2257.24 2257.04 2256.64 2256.89 2256.63
 2256.56 2256.67 2257.04 2257.03 2256.67 2257.17 2256.67  2256.8  2256.8  2256.8
  2256.8  2256.8  2256.8 2256.43 2256.62 2256.45 2256.37 2256.42 2256.72  2256.7
  2256.5 2256.78 2255.86 2255.79 2256.74  2256.8  2255.8 2255.83 2256.72 2255.78
 2261.43 2273.18 2275.56 2280.76 2282.77 2290.21 2298.07 2299.98 2300.87 2306.14
 2216.22 2216.22 2216.22 2216.22 2216.22 2216.22 2216.22 2216.22 2216.22 2216.22
 2216.22 2216.22 2216.22 2216.22 2216.22 2216.22 2216.22 2216.22 2216.22 2216.22
 2216.22 2216.22 2216.22 2216.22 2216.22 2216.22 2216.22 2216.22 2216.22  2254.8
  2254.8 2216.22 2216.22 2216.22 2216.22 2216.22 2216.22 2216.22 2216.22 2216.22
 2216.22 2216.22 2216.22 2216.22 2216.22 2216.22 2216.22 2216.22 2216.22 2216.22
 2216.22 2216.22 2216.22 2216.22 2216.22 2216.22 2216.22 2216.22 2216.22 2216.22
  4491.1  4551.4  4557.2    4566  4579.8  4583.5  4593.3  4595.2  4615.2  4621.4
  4626.3    4633  4637.4    4641  4650.6  4653.2  4725.5  4762.3  4777.1  4780.1
  4787.4  4812.4  4824.9  4841.2  4871.9  4885.7  4909.7  4915.6  4957.5  4957.5
  5042.5  5042.5  5048.3  5052.2  5125.9  5132.7  5159.4  5167.1  5172.7  5180.9
  5186.2  5226.3  5235.8  5239.6  5249.5  5263.2  5266.3  5269.6  5276.1  5282.8
  5290.9  5304.5  5309.1  5320.8  5325.7  5342.1  5360.7  5364.9  5366.2  5419.5
 2301.38 2296.73 2293.37    2290 2283.18  2281.2 2276.82 2276.12 2264.77  2261.9
 2261.12 2258.72 2259.07 2259.12 2257.29 2257.24 2257.04 2256.64 2256.89 2256.63
 2256.56 2256.67 2257.04 2257.03 2256.67 2257.17 2256.67  2256.8  2256.8  2256.8
  2256.8  2256.8  2256.8 2256.43 2256.62 2256.45 2256.37 2256.42 2256.72  2256.7
  2256.5 2256.78 2255.86 2255.79 2256.74  2256.8  2255.8 2255.83 2256.72 2255.78
 2261.43 2273.18 2275.56 2280.76 2282.77 2290.21 2298.07 2299.98 2300.87 2306.14
 2216.22 2216.22 2216.22 2216.22 2216.22 2216.22 2216.22 2216.22 2216.22 2216.22
 2216.22 2216.22 2216.22 2216.22 2216.22 2216.22 2216.22 2216.22 2216.22 2216.22
 2216.22 2216.22 2216.22 2216.22 2216.22 2216.22 2216.22 2216.22 2216.22  2254.8
  2254.8 2216.22 2216.22 2216.22 2216.22 2216.22 2216.22 2216.22 2216.22 2216.22
 2216.22 2216.22 2216.22 2216.22 2216.22 2216.22 2216.22 2216.22 2216.22 2216.22
 2216.22 2216.22 2216.22 2216.22 2216.22 2216.22 2216.22 2216.22 2216.22 2216.22
Abutment Skew #Up #Dn= , 2 , 2
  4957.5  4966.4
 2254.76 2240.18
  4957.5  4973.2
 2254.92 2238.73
Abutment Skew #Up #Dn= , 2 , 2
  5030.2  5042.5
 2243.05 2254.76
  5027.3  5042.5
 2241.78 2254.92
BR Coef= 1 , 1 , 0 ,1.25, 0 ,,,0.8,0,2,0,
WSPro=,,,, 1 ,,,, 0 ,,,, 0 ,,,,-1 ,-1 ,-1 , 0 , 0 , 0 , 0 , 0
BC Design=,, 0 ,, 0 ,,,,,,
BC HTab HWMax=2313.61

Type RM Length L Ch R = 1 ,213     ,52,52,52
BEGIN DESCRIPTION:
XS 1
END DESCRIPTION:
XS GIS Cut Line= 6
       1055596.2       838224.08      1055462.75       838219.32
      1055324.54       838481.44      1055258.96       838578.82
       1055139.8       838781.39      1055213.33       838889.73
#Sta/Elev= 30
  4502.6 2289.94  4543.6 2271.37  4566.4 2256.99  4582.2 2258.97  4605.8  2257.1
  4636.1 2245.83  4657.9 2243.21    4718 2242.31  4751.1 2245.51  4760.5 2243.72
  4786.8 2248.14    4829  2249.2  4889.9 2243.13  4924.5    2244  4951.6  2242.1
  4977.4 2237.93    4990 2234.66    5010 2234.66    5014 2237.93  5049.3  2246.7
  5101.5 2241.53  5168.4  2242.8  5237.6 2245.45  5273.2 2249.17  5284.9 2248.26
    5316 2255.11  5337.3 2255.51  5360.5 2273.26  5381.8  2281.6  5415.8    2300
#Mann= 3 ,-1 , 0
  4502.6     .09       0  4977.4    .052       0    5014     .09       0
#XS Ineff= 2 , 0
       0    4924 2256.79    5076       0 2256.46
Permanent Ineff=
       F       F
Bank Sta=4977.4,5014
Exp/Cntr=0.5,0.3

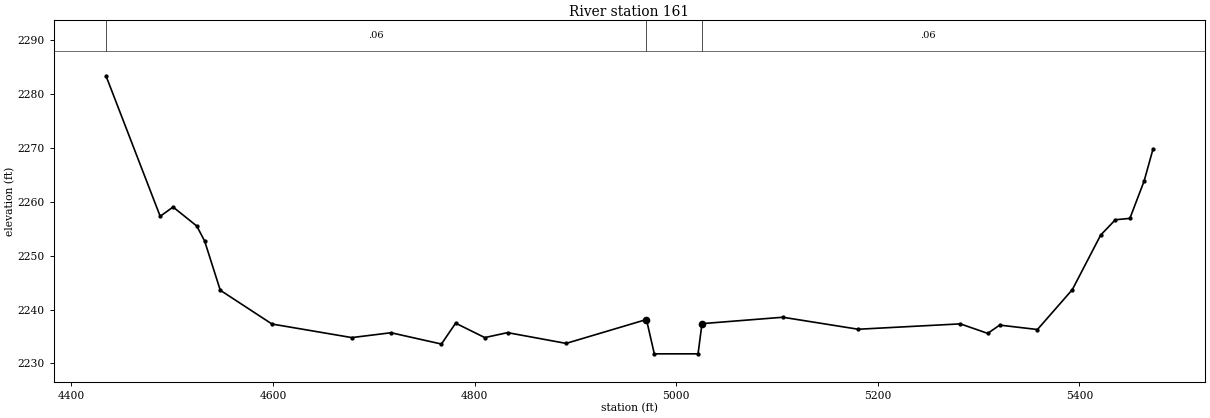
Type RM Length L Ch R = 1 ,161     ,0,0,0
BEGIN DESCRIPTION:
backwater
END DESCRIPTION:
XS GIS Cut Line= 5
      1055609.97       838168.14      1055441.52       838162.33
      1055245.47       838505.04      1055063.95       838795.48
      1055149.63       838897.13
#Sta/Elev= 30
  4434.3 2283.44  4488.1 2257.33  4500.9 2259.05  4524.4 2255.52  4532.2 2252.73
  4547.7 2243.59    4599 2237.31  4678.2 2234.79  4717.1 2235.69  4767.1 2233.59
  4781.2 2237.47  4810.1 2234.79  4832.7 2235.71  4890.8 2233.71  4970.5 2238.15
  4978.3 2231.77  5021.7 2231.77  5025.6 2237.38  5105.8 2238.57  5180.6 2236.34
  5281.9 2237.34  5309.1 2235.57  5320.9 2237.11  5358.4 2236.29    5393  2243.7
  5421.1 2253.83  5435.7 2256.69  5450.1 2256.94  5464.2 2263.86  5473.1 2269.86
#Mann= 3 ,-1 , 0
  4434.3     .06       0  4970.5     .05       0  5025.6     .06       0
Bank Sta=4970.5,5025.6
Exp/Cntr=0.3,0.1

Chan Stop Cuts=-1
Use User Specified Reach Order=0
User Specified Reach Order=Cane Creek      ,Reach-1