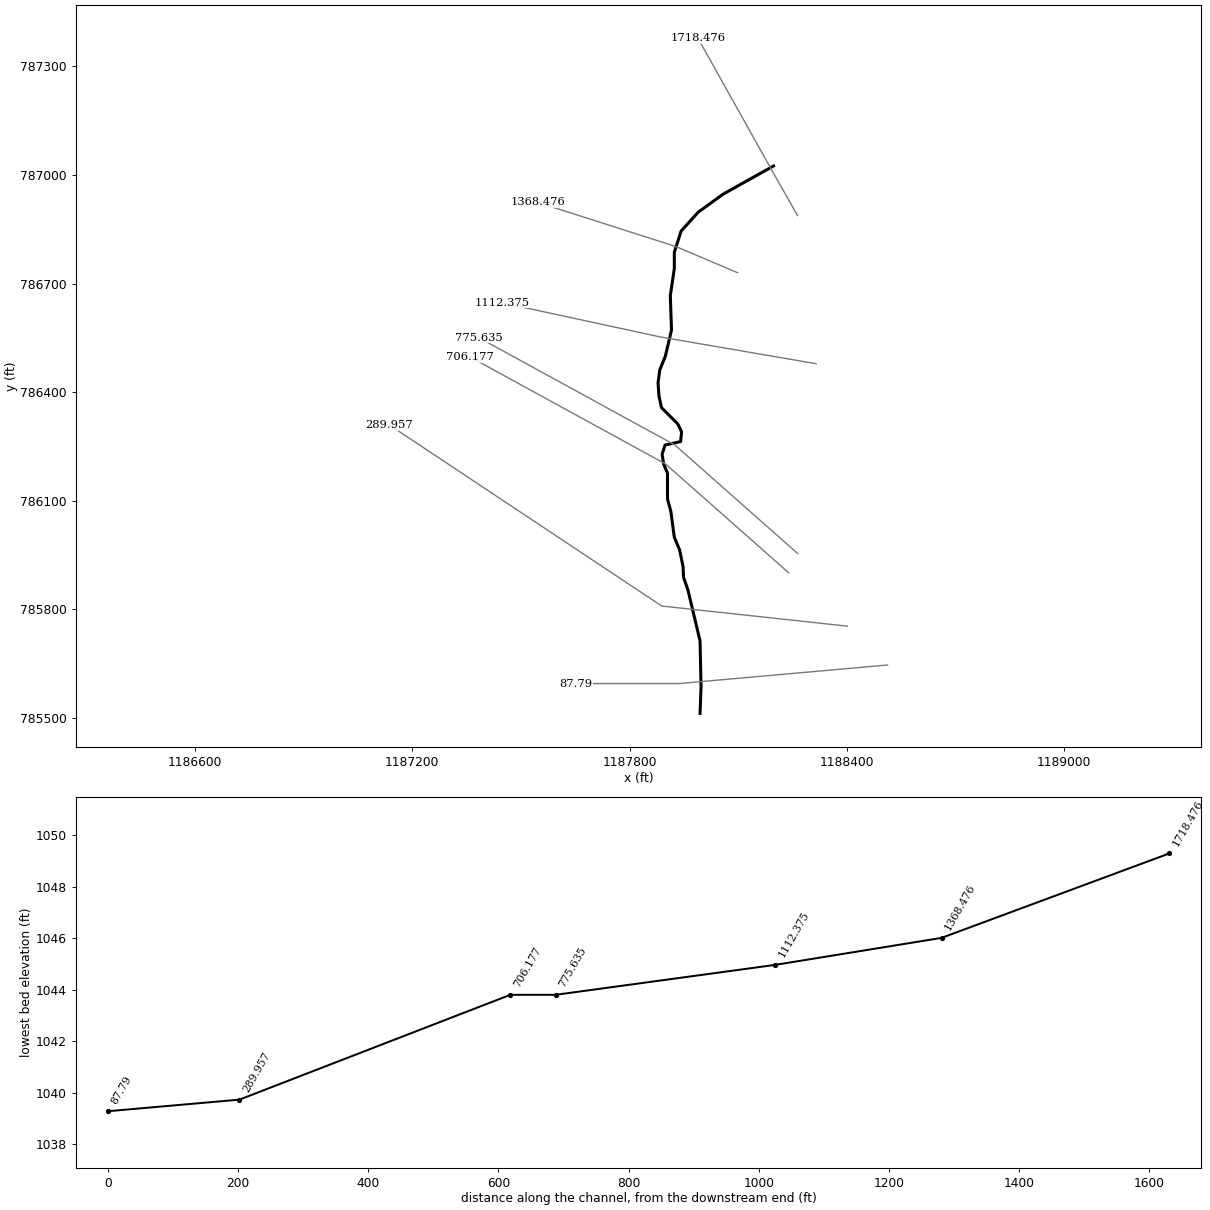
--- Carroll_Cr.prj (project) ---

Proj Title=Carroll_Cr
Current Plan=p02
Default Exp/Contr=0.3,0.1
English Units
Geom File=g02
Geom File=g01
Flow File=f01
Plan File=p02
Plan File=p01
Y Axis Title=Elevation
X Axis Title(PF)=Main Channel Distance
X Axis Title(XS)=Station
BEGIN DESCRIPTION:
END DESCRIPTION:
DSS Export Rating Curves= 0
DSS Export Rating Curve Sorted= 0
DSS Export Volume Flow Curves= 0
DXF OffsetX= 0
DXF OffsetY= 0
DXF ScaleX= 1
DXF ScaleY= 10

--- Carroll_Cr.p02 (plan) ---

Plan Title=Carroll_Cr
Program Version=3.12
Short Identifier=LDS
Geom File=g02
Flow File=f01
Subcritical Flow
K Sum by GR= 0
Std Step Tol= 0.01
Critical Tol= 0.01
Num of Std Step Trials= 20
Max Error Tol= 0.3
Flow Tol Ratio= 0.001
Split Flow NTrial= 30
Split Flow Tol= 0.02
Split Flow Ratio= 0.02
Log Output Level= 0
Friction Slope Method= 1
Unsteady Friction Slope Method= 2
Unsteady Bridges Friction Slope Method= 1
Parabolic Critical Depth
Global Vel Dist= 0 , 0 , 0
Global Log Level= 0
CheckData=True
Encroach Param=-1 ,0,0, 2
Encroach River=Carroll_Cr
Encroach Reach=Main
Encroach Node=1718.476
       1  139.17  299.99
Encroach Node=1368.476
       1  173.92  248.98
Encroach Node=1112.375
       1  398.02  516.55
Encroach Node=775.635
       1     395  559.93
Encroach Node=706.177
       1     400  561.69
Encroach Node=289.957
       1  397.24  553.55
Encroach Node=87.79
       1   332.4   645.9
Computation Interval=1HOUR
Output Interval=1HOUR
Run HTab= 0
Run UNet= 0
Run PostProcess= 0
UNET Theta= 1
UNET Theta Warmup= 1
UNET ZTol= 0.02
UNET ZSATol= 0.05
UNET MxIter= 20
UNET MaxInSteps= 0
UNET DtIC= 0
UNET DtMin= 0
UNET MaxCRTS= 20
UNET WFStab= 2
UNET SFStab= 1
UNET WFX= 1
UNET SFX= 1
UNET DSS MLevel= 4
UNET DZMax Abort= 100
UNET Convert EG Bridges=-1
UNET Use Existing IB Tables=-1
UNET Froude Reduction=False
UNET Froude Limit= 1
UNET Froude Power= 10
Instantaneous Interval=1HOUR
Write IC File= 0
Echo Input=False
Echo Output=False
Write Detailed= 0
Detailed Automatic Start=False, 10

--- Carroll_Cr.f01 (steady flow) ---

Flow Title=Carroll_Cr
Program Version=3.12
Number of Profiles= 2
Profile Names=P100yr,PF 2
River Rch & RM=Carroll_Cr,Main            ,1718.476
    1880    1880
Boundary for River Rch & Prof#=Carroll_Cr,Main            , 1
Up Type= 0
Dn Type= 3
Dn Slope=0.0021
DSS Import GetInterval= 0
DSS Import GetPeak= 0
DSS Import FillOption= 0

--- Carroll_Cr.g02 (geometry) ---

Geom Title=Carroll_Cr
Program Version=3.12

River Reach=Carroll_Cr      ,Main
Reach XY= 30
  1188197.733753   787024.879382  1188058.343411   786946.915294
  1187989.829542   786897.301796  1187942.578582   786845.325694
  1187923.678146   786786.262043  1187923.678146   786741.373621
  1187912.627108   786666.749791  1187915.879332     786571.6898
  1187899.044785   786500.001611  1187883.514865   786461.411635
  1187878.789724   786425.973366  1187881.152262   786390.535162
  1187888.239942   786357.459497  1187933.128364   786312.571075
  1187943.748577   786290.442074  1187941.131218   786263.633745
  1187898.131375   786254.188363  1187890.000817   786228.690806
  1187894.129589    786201.87836  1187904.881625   786176.311133
  1187904.881625   786105.188205  1187914.249168   786070.249317
  1187923.547042    785999.99882  1187938.378703   785964.191553
  1187947.750364    785918.56213   1187949.13479   785889.001287
  1187961.250731   785854.058347  1187994.751927   785713.131365
  1187997.496272   785585.561426  1187994.751927   785513.058123

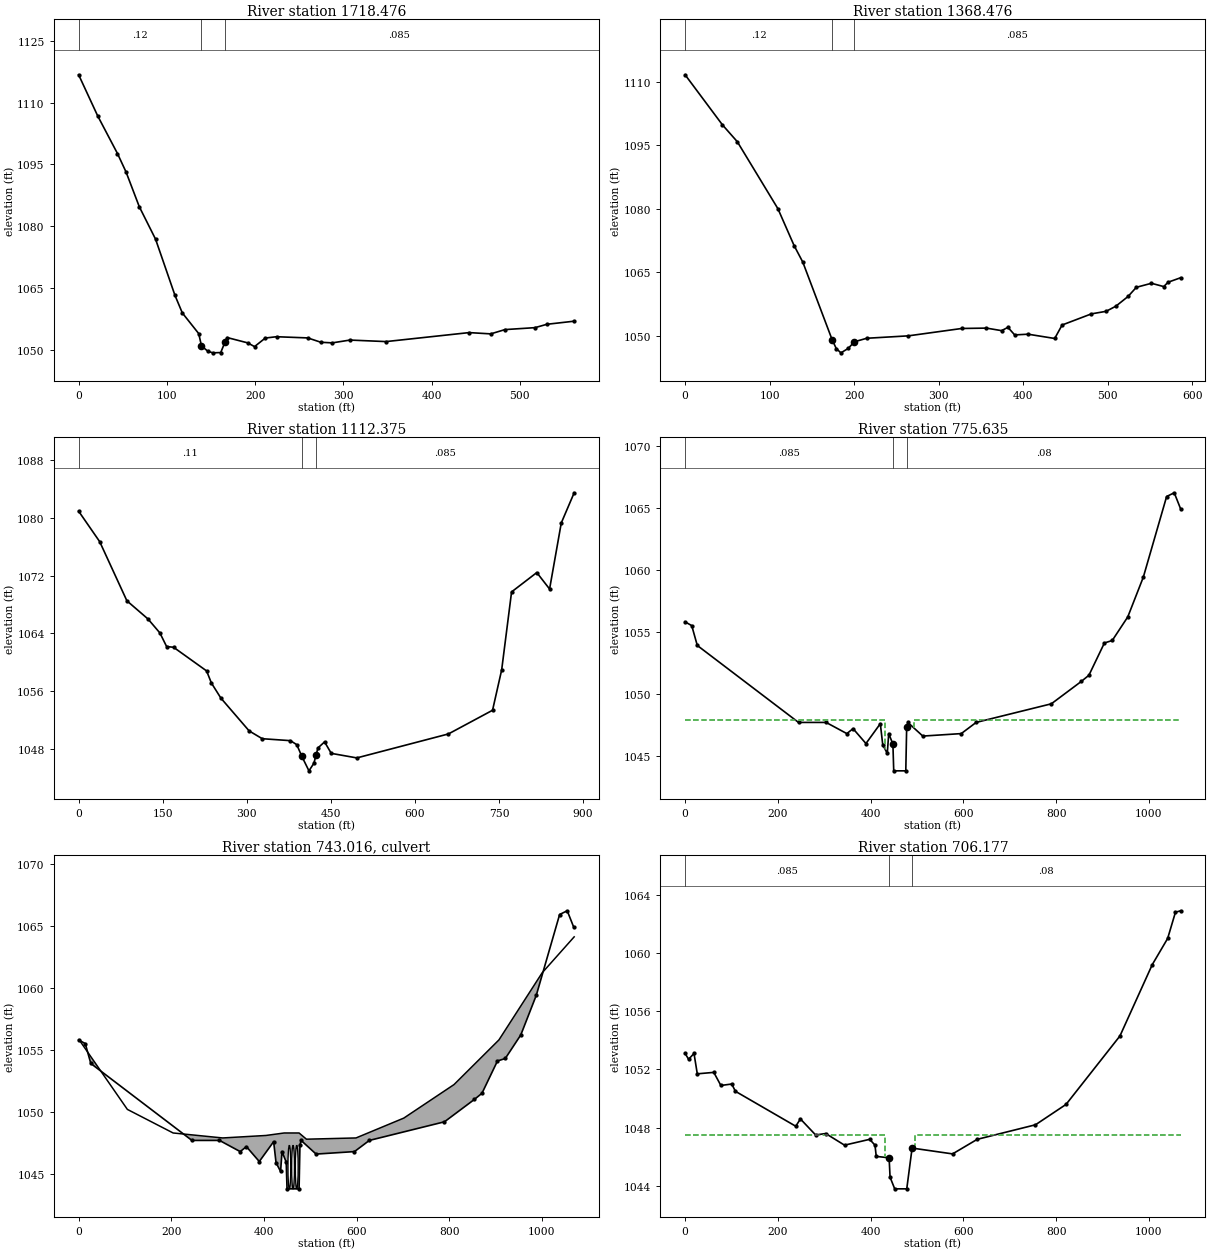
Type RM Length L Ch R = 1 ,1718.476,330.19,350,372.53
XS GIS Cut Line= 3
  1188264.108731   786887.746225  1188189.006172   787019.997844
  1187989.155988   787377.305785
#Sta/Elev= 30
       0 1116.75   21.58 1106.78   44.02 1097.64   53.72 1093.17   68.73 1084.74
   87.16 1076.87  109.15 1063.24  117.49 1058.97   136.1 1053.95  139.17 1050.99
  146.48 1049.66  152.09 1049.29  161.02 1049.36  165.65  1051.8  168.25    1053
  191.54 1051.71  199.32  1050.8  211.51 1052.88  224.22  1053.2  259.58 1052.91
  274.56 1051.85  287.45 1051.71  307.43 1052.39  348.32 1052.02  442.46  1054.2
  466.94 1053.89  483.08 1054.93  517.08  1055.4  530.65 1056.22  561.49 1056.97
#Mann= 3 , 0 , 0
       0     .12       0  139.17    .053       0  165.65    .085       0
Bank Sta=139.17,165.65
Exp/Cntr=0.3,0.1

Type RM Length L Ch R = 1 ,1368.476,249.05,256.1,260.05
XS GIS Cut Line= 3
  1188098.472314   786729.997244  1187928.725621   786802.035346
  1187545.814247   786924.567352
#Sta/Elev= 30
       0 1111.65   44.18 1099.83   61.75 1095.86   109.8 1080.05     129 1071.33
  139.33 1067.41  173.92 1049.15  178.91 1047.01   184.4 1046.01  193.12 1047.06
  200.21 1048.61  214.94 1049.45  264.19 1050.02  327.33 1051.76  356.65 1051.85
  374.53 1051.25  382.07 1052.03  390.04 1050.24  405.88 1050.41  437.39  1049.4
  446.17 1052.58  480.85 1055.21  498.22 1055.81  509.77 1057.02  524.17 1059.31
  534.01 1061.48   551.9 1062.43  566.44 1061.65  571.59 1062.68  586.44 1063.74
#Mann= 3 , 0 , 0
       0     .12       0  173.92    .053       0  200.21    .085       0
Bank Sta=173.92,200.21
Exp/Cntr=0.3,0.1

Type RM Length L Ch R = 1 ,1112.375,346.27,336.74,322.48
XS GIS Cut Line= 3
  1188315.363308   786478.733538  1187885.511216    786552.52964
  1187447.757834   786647.179003
#Sta/Elev= 30
       0 1080.92   37.57  1076.7   86.09 1068.51  123.76 1065.99  144.95 1064.06
  156.91 1062.18  169.42 1062.07  228.28  1058.8  236.86 1057.12   253.8 1055.03
  304.19 1050.49  327.56 1049.41  377.82 1049.14  389.19 1048.58  398.02 1046.99
  410.88 1044.96  419.68 1046.01  423.44  1047.1  426.93 1048.13  438.75 1048.97
  450.66 1047.38  496.26 1046.75  659.68 1050.07   738.4 1053.35  754.69 1058.95
  772.34 1069.74  817.33 1072.42  840.15 1070.14     861 1079.29  884.01 1083.47
#Mann= 3 , 0 , 0
       0     .11       0  398.02    .053       0  423.44    .085       0
Bank Sta=398.02,423.44
Exp/Cntr=0.5,0.3

Type RM Length L Ch R = 1 ,775.635 ,88.02,69.46,60.91
BEGIN DESCRIPTION:
Upstream xs of Bridge 3723-0018
END DESCRIPTION:
XS GIS Cut Line= 3
  1188264.340744   785954.552784  1187925.180474   786254.275809
  1187384.890293   786550.055148
#Sta/Elev= 30
       0  1055.8    14.3  1055.5    26.3  1053.9   244.6  1047.7   304.1  1047.7
   348.8  1046.8   362.2  1047.2     390    1046     421  1047.6   426.2  1045.9
     436  1045.2   439.1  1046.8  448.121045.953   449.9  1043.8   475.9  1043.8
   477.8  1047.3   480.3  1047.7   512.6  1046.6   595.5  1046.8   627.6  1047.7
   789.8  1049.2   854.3    1051   870.8  1051.5   904.2  1054.1   921.1  1054.3
   954.6  1056.2   988.1  1059.4  1038.4  1065.9  1054.8  1066.2  1068.6  1064.9
#Mann= 3 , 0 , 0
       0    .085       0  448.12    .053       0   477.8     .08       0
#XS Ineff= 2 , 0
       0     432  1047.9     493       0  1047.9
Permanent Ineff=
       F       F
Bank Sta=448.12,477.8
Exp/Cntr=0.5,0.3

Type RM Length L Ch R = 2 ,743.016 ,,,
BEGIN DESCRIPTION:
Culvert : 3723-0018
END DESCRIPTION:
Bridge Culvert--1,0,-1,-1, 0
Deck Dist Width WeirC Skew NumUp NumDn MinLoCord MaxHiCord MaxSubmerge Is_Ogee
18.6,28,2.6,0, 17, 17, , , 0.95, 0, 0,0,,
     1.2   105.2     204     311   404.4   443.7   449.9   449.9   475.9   475.9
   491.8   598.8     702   810.4   907.4  1000.6  1069.8
  1055.8  1050.2  1048.3  1047.9  1048.1  1048.3  1048.3  1048.3  1048.3  1048.3
  1047.8  1047.9  1049.5  1052.2  1055.8  1061.2  1064.1
                                                                                
                                                        
    -2.2   101.7   200.6   307.6     401   440.3     452     452     478     478
   499.3   595.4   698.5     807     904   997.1  1066.3
  1055.8  1050.2  1048.3  1047.9  1048.1  1048.3  1048.3  1048.3  1048.3  1048.3
  1047.7  1047.9  1049.5  1052.2  1055.8  1061.2  1064.1
                                                                                
                                                        
BR Coef=-1 , 0 , 0 ,, 0 ,,,0.8,-1,,0,
WSPro=,,,, 1 ,,,, 0 ,,,, 0 ,,,,-1 ,-1 ,-1 , 0 , 0 , 0 , 0 , 0
Multiple Barrel Culv=4,3.5,6,38,0.023,0.5,1,29,1,1043.8,1043.8, 3,Culvert #1  , 0 ,13.6
   454.9     457   462.9     465   470.9     473
Culvert Bottom n=0.023
BC Design=,, 0 ,, 0 ,,,,,,

Type RM Length L Ch R = 1 ,706.177 ,383.1,416.22,430.77
BEGIN DESCRIPTION:
Down stream xs of Bridge 3723-0018
END DESCRIPTION:
XS GIS Cut Line= 3
  1188238.848284   785901.944041  1187899.688014   786201.667065
  1187359.397833   786497.446404
#Sta/Elev= 30
       0  1053.1     7.6  1052.7    19.2  1053.1    26.3  1051.7    61.9  1051.8
    77.1  1050.9   100.6    1051   108.5  1050.5   238.6  1048.1   248.7  1048.6
   281.5  1047.5   303.2  1047.6   343.8  1046.8     398  1047.2   409.5  1046.8
  412.18 1046.03  439.95 1045.93     442  1044.6     452  1043.8     478  1043.8
   489.5  1046.6   576.8  1046.2   629.9  1047.2   755.6  1048.2   821.5  1049.6
   937.7  1054.3  1007.4  1059.2  1040.6    1061  1057.4  1062.8  1068.6  1062.9
#Mann= 3 , 0 , 0
       0    .085       0  439.95    .053       0   489.5     .08       0
#XS Ineff= 2 , 0
       0     432  1047.5   495.9       0  1047.5
Permanent Ineff=
       F       F
Bank Sta=439.95,489.5
Exp/Cntr=0.5,0.3

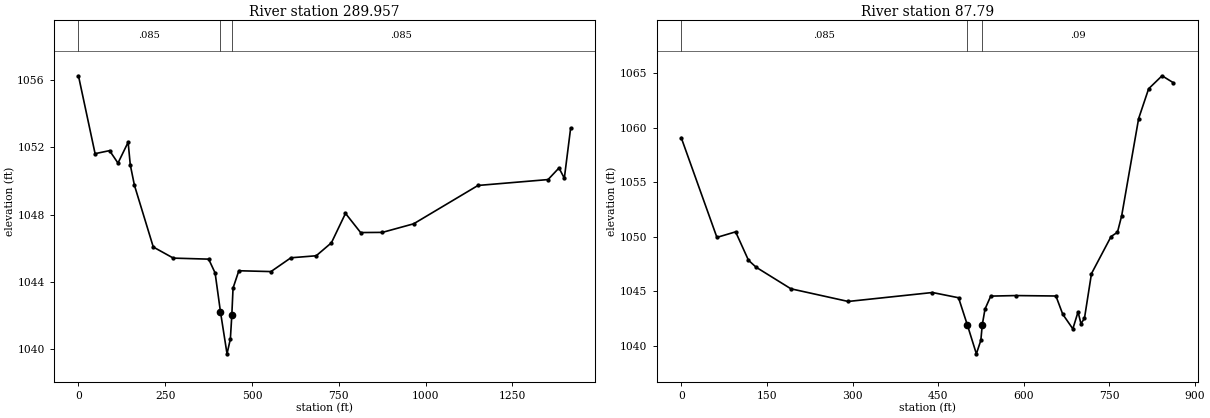
Type RM Length L Ch R = 1 ,289.957 ,195.84,202.17,208.44
XS GIS Cut Line= 3
  1188401.453314    785753.97467  1187889.006301    785809.48971
  1187137.417406   786309.125529
#Sta/Elev= 30
       0 1056.26    47.9 1051.63   89.61 1051.81  113.87 1051.07  143.12 1052.31
  149.24 1050.97  161.23 1049.75  215.57 1046.08   273.4 1045.42  375.11 1045.36
  393.66 1044.54  409.15 1042.22  428.01 1039.73  437.66 1040.62  441.77 1042.02
  445.36 1043.64  462.05 1044.67   554.6 1044.62  611.99 1045.44   684.9 1045.56
   728.7 1046.33  769.32 1048.08  812.91 1046.94  875.55 1046.95  965.65 1047.46
 1151.03 1049.74 1352.91 1050.09 1384.38 1050.78 1399.76 1050.17 1417.95 1053.15
#Mann= 3 , 0 , 0
       0    .085       0  409.15    .053       0  441.77    .085       0
Bank Sta=409.15,441.77
Exp/Cntr=0.3,0.1

Type RM Length L Ch R = 1 ,87.79   ,92.26,87.79,83.32
XS GIS Cut Line= 3
  1188512.563389   785646.656197  1187936.779648   785595.387831
  1187652.831496   785595.387831
#Sta/Elev= 30
       0 1059.09    62.5 1049.95   95.26 1050.46  117.72 1047.86  131.08 1047.22
   192.1 1045.24   292.4 1044.08  439.99  1044.9  485.68 1044.42  501.23 1041.91
  516.92 1039.28  524.75 1040.52  527.21 1041.93  532.03 1043.38  542.07 1044.57
   585.9 1044.62  656.26 1044.58  668.17 1042.91  685.89 1041.57  695.03 1043.13
  700.06 1042.04  706.22 1042.53   718.5 1046.63  752.84 1050.03     764 1050.42
  771.43 1051.94   801.1 1060.84  818.61 1063.57  842.11 1064.76  862.01 1064.12
#Mann= 3 , 0 , 0
       0    .085       0  501.23    .053       0  527.21     .09       0
Bank Sta=501.23,527.21
Exp/Cntr=0.3,0.1

Chan Stop Cuts=-1
Use User Specified Reach Order=0
User Specified Reach Order=Carroll_Cr      ,Main