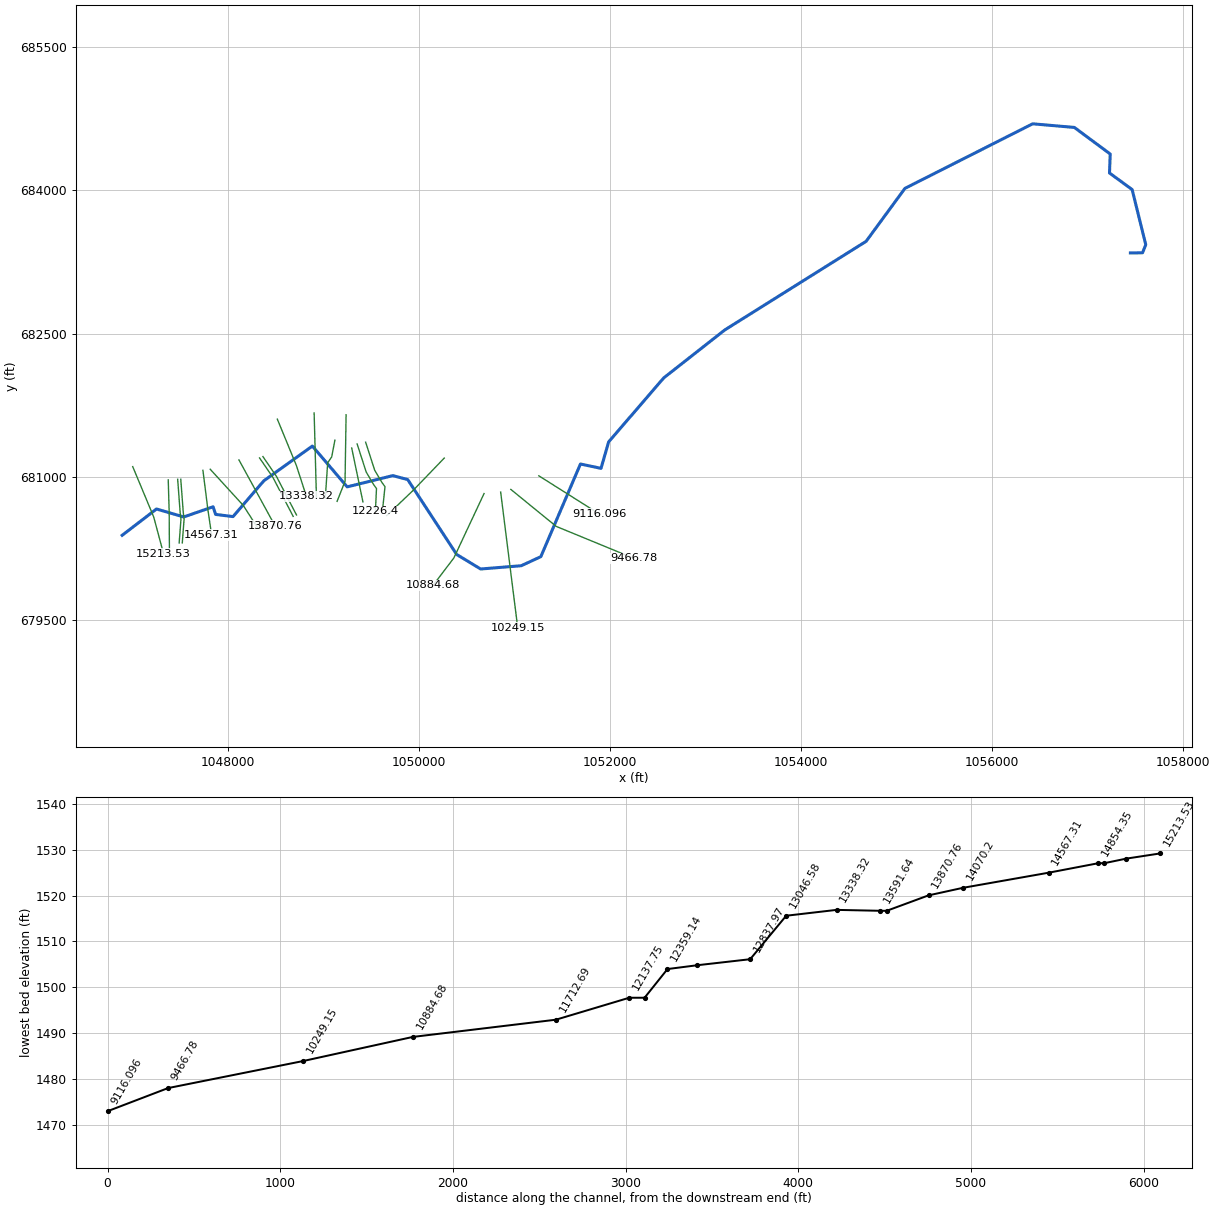
--- Lt_Crooked_Cr.prj (project) ---

Proj Title=Lt_Crooked_Cr
Current Plan=p02
Default Exp/Contr=0.3,0.1
English Units
Geom File=g02
Flow File=f01
Plan File=p02
Y Axis Title=Elevation
X Axis Title(PF)=Main Channel Distance
X Axis Title(XS)=Station
BEGIN DESCRIPTION:
END DESCRIPTION:
DSS Export Rating Curves= 0
DSS Export Rating Curve Sorted= 0
DSS Export Volume Flow Curves= 0
DXF OffsetX= 0
DXF OffsetY= 0
DXF ScaleX= 1
DXF ScaleY= 10

--- Lt_Crooked_Cr.p02 (plan) ---

Plan Title=Lt_Crooked_Cr
Program Version=3.12
Short Identifier=LDS
Geom File=g02
Flow File=f01
Subcritical Flow
K Sum by GR= 0
Std Step Tol= 0.01
Critical Tol= 0.01
Num of Std Step Trials= 20
Max Error Tol= 0.3
Flow Tol Ratio= 0.001
Split Flow NTrial= 30
Split Flow Tol= 0.02
Split Flow Ratio= 0.02
Log Output Level= 0
Friction Slope Method= 1
Unsteady Friction Slope Method= 2
Unsteady Bridges Friction Slope Method= 1
Parabolic Critical Depth
Global Vel Dist= 0 , 0 , 0
Global Log Level= 0
CheckData=True
Encroach Param=-1 ,0,0, 2
Encroach River=Lt_Crooked_Cr
Encroach Reach=Main
Encroach Node=15213.53
       1459.4183     580
Encroach Node=15015.91
       1     322     360
Encroach Node=14888.24
       1     310     419
Encroach Node=14854.35
       1     310420.8014
Encroach Node=14567.31
       1  363.64429.2188
Encroach Node=14070.2
       1  489.32580.9405
Encroach Node=13870.76
       1  362.78421.8836
Encroach Node=13628.78
       1     195344.7971
Encroach Node=13591.64
       1     170     300
Encroach Node=13338.32
       1  450.81523.1506
Encroach Node=13046.58
       1     344  378.42
Encroach Node=12837.97
       1     202     265
Encroach Node=12532.81
       1     600746.3853
Encroach Node=12359.14
       1     340     403
Encroach Node=12226.4
       1     392   440.8
Encroach Node=12137.75
       1     389   429.7
Encroach Node=11712.69
       1374.7446  447.05
Encroach Node=10884.68
       1 608.988     714
Encroach Node=10249.15
       1     740     971
Encroach Node=9466.78
       1     480     650
Encroach Node=9116.096
       1     328     549
Encroach Node=9056.125
       1     348     513
Encroach Node=8543.376
       1     580 824.402
Encroach Node=7935.252
       1938.44511055.813
Encroach Node=7259.751
       1649.3222  868.22
Encroach Node=6816.38
       1     820     950
Encroach Node=6252.28
       1     700     800
Encroach Node=5938.844
       1     410823.6094
Encroach Node=5875.813
       1     410     800
Encroach Node=5616.38
       1274.3683     500
Encroach Node=5327.802
       1284.1611     400
Encroach Node=5025.465
       1264.2784596.2574
Encroach Node=4956.814
       1     323     577
Encroach Node=4747.213
       1  410.05  463.88
Encroach Node=4345.773
       1 540.524  626.79
Encroach Node=3844.177
       1  669.01743.1189
Encroach Node=3120.083
       1789.14121044.326
Encroach Node=2301.944
       1  707.74883.1046
Encroach Node=1636.742
       11737.2522036.169
Encroach Node=857.834
       1   560.7     680
Encroach Node=697.773
       1     585     729
Encroach Node=429.53
       1     450834.6926
Encroach Node=174.158
       1    12632079.294
Computation Interval=1HOUR
Output Interval=1HOUR
Run HTab= 0
Run UNet= 0
Run PostProcess= 0
UNET Theta= 1
UNET Theta Warmup= 1
UNET ZTol= 0.02
UNET ZSATol= 0.05
UNET MxIter= 20
UNET MaxInSteps= 0
UNET DtIC= 0
UNET DtMin= 0
UNET MaxCRTS= 20
UNET WFStab= 2
UNET SFStab= 1
UNET WFX= 1
UNET SFX= 1
UNET DSS MLevel= 4
UNET DZMax Abort= 100
UNET Convert EG Bridges=-1
UNET Use Existing IB Tables=-1
UNET Froude Reduction=False
UNET Froude Limit= 1
UNET Froude Power= 10
Instantaneous Interval=1HOUR
Write IC File= 0
Echo Input=False
Echo Output=False
Write Detailed= 0
Detailed Automatic Start=False, 10

--- Lt_Crooked_Cr.f01 (steady flow) ---

Flow Title=Lt_Crooked_Cr
Program Version=3.12
Number of Profiles= 2
Profile Names=P100yr,enc
River Rch & RM=Lt_Crooked_Cr,Main            ,15213.53
    1330    1330
River Rch & RM=Lt_Crooked_Cr,Main            ,13870.76
    1530    1530
River Rch & RM=Lt_Crooked_Cr,Main            ,13628.78
    1680    1680
River Rch & RM=Lt_Crooked_Cr,Main            ,9466.78
    1835    1835
River Rch & RM=Lt_Crooked_Cr,Main            ,7259.751
    2280    2280
River Rch & RM=Lt_Crooked_Cr,Main            ,3120.083
    2650    2650
River Rch & RM=Lt_Crooked_Cr,Main            ,857.834
    2960    2960
Boundary for River Rch & Prof#=Lt_Crooked_Cr,Main            , 1
Up Type= 0
Dn Type= 3
Dn Slope=0.0008
DSS Import GetInterval= 0
DSS Import GetPeak= 0
DSS Import FillOption= 0

--- Lt_Crooked_Cr.g02 (geometry) ---

Geom Title=Lt_Crooked_Cr
Program Version=3.12

River Reach=Lt_Crooked_Cr   ,Main
Reach XY= 30
   1046890.22318   680387.739235   1047250.30584   680663.498474
  1047535.129398   680580.005642  1047842.751291   680686.309121
  1047869.309743   680606.559977   1048051.63091   680583.749369
  1048373.441358   680957.878017  1048882.381627   681322.438407
  1049246.999379    680895.18874  1049725.498163   681012.940534
  1049881.129807   680971.132679  1050393.879359   680186.941187
  1050644.501316   680035.000065   1051069.87912   680069.189354
  1051274.998584    680164.13054  1051690.251065   681134.628604
  1051905.381168   681088.880394  1051985.130312   681366.130437
  1052562.379604    682036.43674  1053200.380754    682537.68881
   1054681.49844   683466.252025  1055087.878996    684020.75211
  1056425.628485   684697.190136  1056862.380854   684659.248886
  1057238.000459   684380.692202  1057230.377816   684181.999344
  1057467.249485   684008.812284  1057610.130249   683431.558914
  1057576.629058   683346.501374  1057449.128769   683344.940782

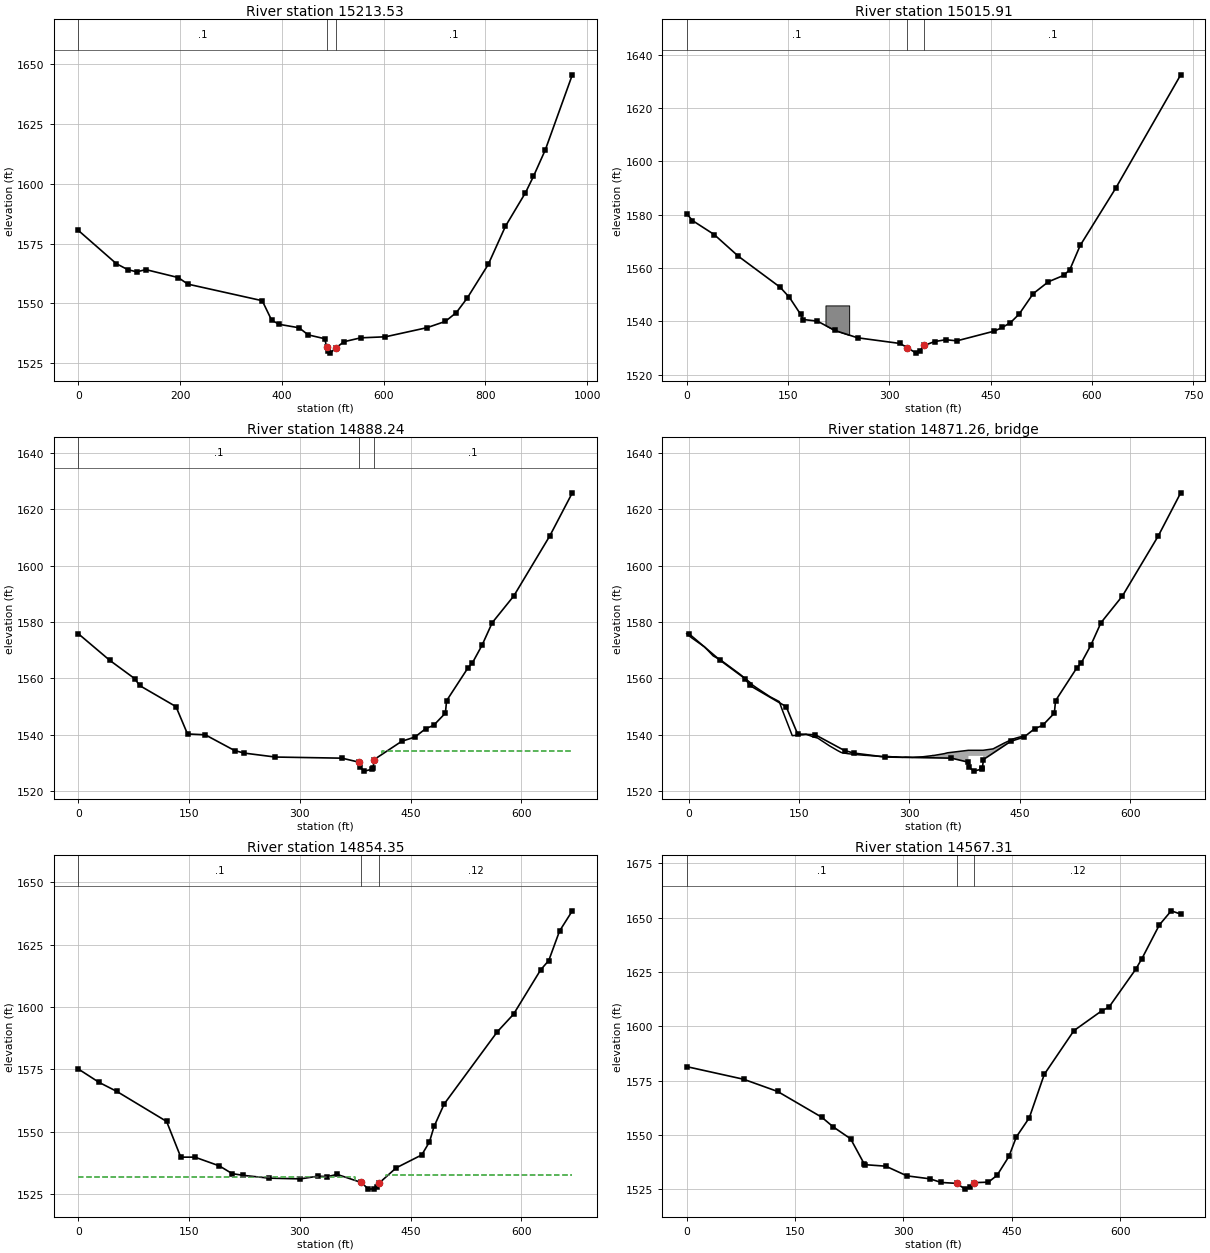
Type RM Length L Ch R = 1 ,15213.53,208.01,197.61,186.28
XS GIS Cut Line= 3
  1047001.189988   681107.105268  1047221.115696   680579.732391
  1047324.346109   680193.740348
#Sta/Elev= 30
       0 1580.58   74.72 1566.66   97.14 1564.16  114.94 1563.22  132.81 1564.16
  196.31 1560.85  215.39 1558.09  361.56 1551.16  379.99 1543.04  394.81 1541.28
  433.99 1539.84  451.79 1536.88  484.41 1535.26  488.26 1531.66  489.93 1530.24
  495.02 1529.24  505.84 1531.34  522.23 1534.01  554.92 1535.63  603.73 1536.07
  685.51 1539.89  721.54 1542.52  743.13 1546.22  764.75 1552.36  805.68  1566.3
   839.6  1582.3  878.92 1596.32  894.52 1603.12  917.87 1614.22  970.95  1645.6
#Mann= 3 , 0 , 0
       0      .1       0  488.26    .045       0  505.84      .1       0
Bank Sta=488.26,505.84
Exp/Cntr=0.3,0.1

Type RM Length L Ch R = 1 ,15015.91,124.87,127.68,130.18
XS GIS Cut Line= 3
  1047373.226997   680968.140547  1047383.046058   680626.928296
  1047385.500814   680236.620741
#Sta/Elev= 30
       0 1580.39    8.52  1577.8   40.78 1572.54   76.63  1564.4  138.45  1552.8
  152.25 1548.98  168.78 1542.64  172.66 1540.69  193.68  1540.1  219.09 1536.63
  253.12 1533.85  315.75 1531.73  326.87 1530.17  339.54  1528.1  345.64 1529.06
  351.74 1530.97  367.19 1532.43  383.78 1533.12  400.28 1532.71  455.73 1536.36
  467.51 1537.73  479.54 1539.52  492.36 1542.71  513.19 1550.39  535.69 1554.84
   558.3 1557.23  567.47 1559.38  582.82 1568.46  635.34 1589.88  731.67  1632.4
#Mann= 3 , 0 , 0
       0      .1       0  326.87    .045       0  351.74      .1       0
#Block Obstruct= 1 ,-1
   205.6  240.68 1545.98
Bank Sta=326.87,351.74
Exp/Cntr=0.5,0.3

Type RM Length L Ch R = 1 ,14888.24,34.12,33.89,32.71
BEGIN DESCRIPTION:
Upstream xs of Bridge 37111-0336
END DESCRIPTION:
XS GIS Cut Line= 4
   1047471.84888   680974.701022  1047497.991396   680625.363238
  1047506.547466   680558.747976   1047487.55787   680308.191496
#Sta/Elev= 30
       0  1575.9    42.8  1566.4    76.6  1559.9      83  1557.5   132.3    1550
   147.9  1540.3   171.9    1540   211.7  1534.4   224.7  1533.5   266.9  1532.1
   357.1  1531.7   379.6  1530.3   381.2  1528.5   387.2  1527.1   398.2  1527.8
   399.2  1528.3   400.5  1531.2   437.9  1537.7   455.8  1539.2   470.4  1542.2
   480.9  1543.3     497  1547.7   498.6  1552.1   527.4  1563.7   533.5  1565.5
   546.6  1571.8   560.4  1579.8   589.6  1589.3   638.3  1610.6   668.8  1625.9
#Mann= 3 , 0 , 0
       0      .1       0   379.6    .045       0   400.5      .1       0
#XS Ineff= 2 , 0
       0                   411.2       0  1534.4
Permanent Ineff=
       F       F
Bank Sta=379.6,400.5
Exp/Cntr=0.5,0.3

Type RM Length L Ch R = 3 ,14871.26,,,
BEGIN DESCRIPTION:
Bridge : 37111-0336 (Gravel Rd)
END DESCRIPTION:
Bridge Culvert--1,0,-1,-1, 0
Deck Dist Width WeirC Skew NumUp NumDn MinLoCord MaxHiCord MaxSubmerge Is_Ogee
11,12,2.6,0, 55, 47, , , 0.95, 0, 0,0,,
      -3     2.1     3.4    20.2      21    33.1    44.6      69    84.6    85.5
      92   110.5   122.9   127.2   140.6   155.2   159.4   168.7   175.4   185.9
   191.1   201.6   207.3   216.1   226.4   240.1   241.3   261.6   265.7   276.5
   278.2   281.6   290.4   294.9   304.2   310.2   318.3     331     332   332.9
   333.9   347.3   351.6   380.2   380.2   400.2   400.2   413.6   414.4   415.1
   429.1   440.6   444.3   449.7     456
  1575.9  1574.8  1574.5  1571.4  1571.3    1568  1566.3  1561.6  1558.3  1557.9
  1556.7  1553.5  1551.8  1548.7  1539.7    1540  1540.2  1539.3  1538.8    1537
  1536.1  1534.5  1533.7  1533.3    1533  1532.7  1532.7  1532.3  1532.4  1532.2
  1532.2  1532.2    1532  1532.1    1532  1532.1  1532.2  1532.6  1532.7  1532.6
  1532.7  1533.3  1533.6  1534.5  1534.5  1534.5  1534.5    1535  1535.1  1535.2
  1537.1  1538.5  1538.8  1539.2  1539.6
                                                                                
                                                                                
                                                                                
                                                                                
                                  1532.5  1532.5
                                        
   245.8   246.9   267.3   271.4   282.2   283.9   287.3   296.1   300.6   309.9
   315.9     324   336.7   337.7   338.6   339.6     353   357.3   385.9   385.9
   405.9   405.9   419.3   420.1   420.8   434.8   446.3     450   455.3   461.7
   463.4   486.7   489.2   489.9   492.6     550   562.2     569   571.4   576.1
   591.2   615.7   628.8   632.7     638   654.2   671.4
  1532.3  1532.7  1532.3  1532.4  1532.2  1532.2  1532.2    1532  1532.1    1532
  1532.1  1532.2  1532.6  1532.7  1532.6  1532.7  1533.3  1533.6  1534.5  1534.5
  1534.5  1534.5    1535  1535.1  1535.2  1537.1  1538.5  1538.8  1539.2  1539.6
  1539.7  1544.4  1545.1  1546.3  1553.8  1576.9  1580.5  1583.8  1585.1  1587.9
  1592.8  1603.6  1609.9  1611.2  1615.5    1623  1631.7
                                                                                
                                                                          1532.5
  1532.5
                                                                                
                                                        
BR Coef=-1 , 1 , 0 ,, 0 ,,,0.8,0,1.2,0,
WSPro=,,,, 1 ,,,, 0 ,,,, 0 ,,,,-1 ,-1 ,-1 , 0 , 0 , 0 , 0 , 0
BC Design=,, 0 ,, 0 ,,,,,,

Type RM Length L Ch R = 1 ,14854.35,286.76,287.04,288.64
BEGIN DESCRIPTION:
Down stream xs of Bridge 37111-0336
END DESCRIPTION:
XS GIS Cut Line= 4
  1047504.487791   680974.701022  1047530.630308   680625.363238
  1047539.186378   680558.747976  1047520.196781   680308.191496
#Sta/Elev= 30
       0  1575.2    28.4  1569.8    52.3  1566.2   119.6  1554.2   138.8  1539.9
   157.9  1539.9     191  1536.4   208.4  1533.3   223.6  1532.6   258.4  1531.5
   300.5  1531.2   324.9  1532.3   337.4  1532.1   350.3    1533  382.831529.792
   392.9  1527.1   400.9  1527.2   403.9  1527.8  406.771529.383   430.3  1535.6
     465  1540.8   475.4    1546   481.7  1552.2   495.4  1561.2   567.3  1590.1
   589.2  1597.1     626  1614.9   636.9  1618.6   651.5  1630.4   668.8  1638.5
#Mann= 3 , 0 , 0
       0      .1       0  382.83    .048       0  406.77     .12       0
#XS Ineff= 2 , 0
       0  375.15 1532.12   416.8       0  1532.7
Permanent Ineff=
       F       F
Bank Sta=382.83,406.77
Exp/Cntr=0.5,0.3

Type RM Length L Ch R = 1 ,14567.31,475.07,497.11,507.87
XS GIS Cut Line= 3
  1047736.344897   681068.557941  1047787.343133   680664.214574
  1047827.413225   680391.009589
#Sta/Elev= 30
       0 1581.41   78.75 1575.61  125.91 1569.98   186.9 1558.14  202.81 1553.68
  226.91 1548.19  245.91 1536.52  247.28 1536.27  275.56 1535.59  304.88 1531.13
  336.64 1529.78  352.14  1528.1  373.64 1527.68  385.28 1525.03  391.73 1526.13
  398.09 1528.01  417.62 1528.24  429.61 1531.42  445.97 1540.09   456.3 1549.11
  474.13 1557.85  494.86 1577.84  535.89 1597.97  574.09 1607.03  584.35 1608.77
  621.21 1626.12  629.84 1631.02  654.14 1646.64  670.55 1653.12  683.67 1651.61
#Mann= 3 , 0 , 0
       0      .1       0  373.64    .048       0  398.09     .12       0
Bank Sta=373.64,398.09
Exp/Cntr=0.3,0.1

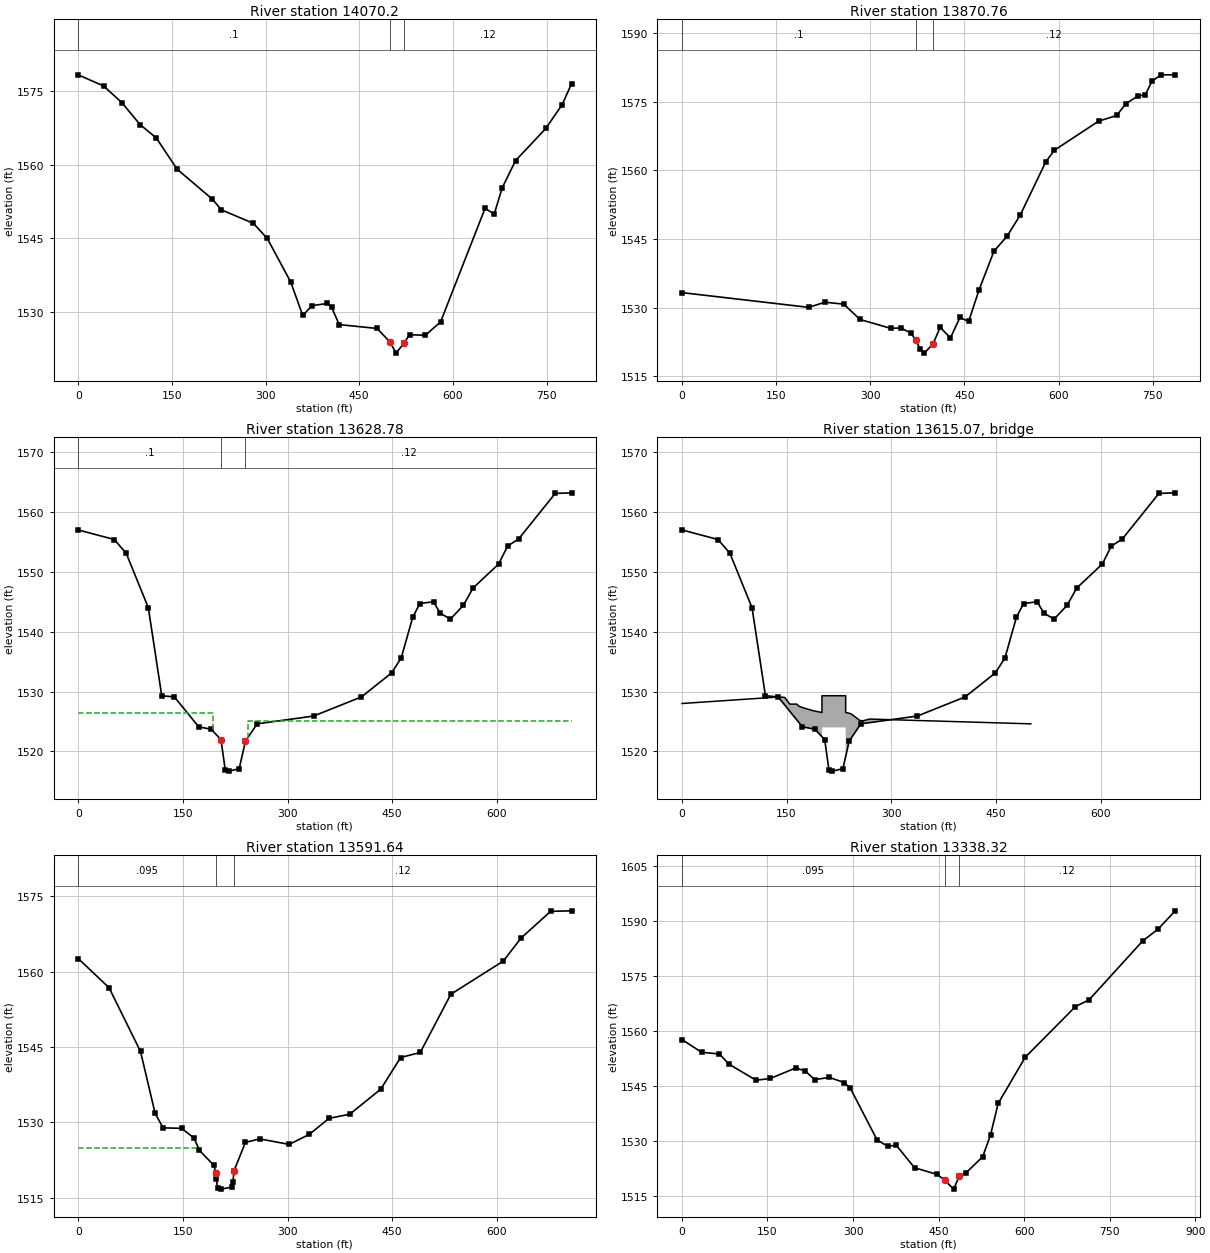
Type RM Length L Ch R = 1 ,14070.2 ,207.05,199.44,196.15
XS GIS Cut Line= 3
  1047812.842289   681079.486124  1048158.901914   680700.641913
  1048308.253985   680467.506982
#Sta/Elev= 30
       0 1578.22   40.73 1575.95   69.94 1572.57   99.04 1568.12  125.07  1565.4
  158.48 1559.05  214.73 1552.99  229.26 1550.81  280.51 1548.07  302.74 1545.01
  340.45 1536.11  359.54 1529.37  374.44 1531.36  398.94  1531.8  405.69 1531.04
  417.99 1527.51  478.63 1526.73  499.32 1523.97     509 1521.72   521.6 1523.73
  530.64 1525.45  556.03 1525.35   580.3 1528.06  651.58 1551.13  666.15 1549.93
  678.97 1555.28  700.37  1560.8  748.83 1567.34  774.96 1572.16  789.98 1576.41
#Mann= 3 , 0 , 0
       0      .1       0  499.32    .048       0   521.6     .12       0
Bank Sta=499.32,521.6
Exp/Cntr=0.3,0.1

Type RM Length L Ch R = 1 ,13870.76,238.37,241.98,244.89
XS GIS Cut Line= 2
  1048114.019906   681176.836433  1048491.185229   680487.534319
#Sta/Elev= 30
       0 1533.29  202.01 1530.07  227.79 1531.19  257.74 1530.77  283.74 1527.42
   332.6 1525.48  348.56 1525.57  364.35 1524.49  372.78 1522.92  379.01 1521.07
     386 1520.07  399.94 1522.07  411.31 1525.71  427.71  1523.4  442.87 1527.86
  456.65 1526.98   473.5 1533.97  497.03 1542.34  518.08 1545.65  538.95 1550.25
  579.45 1561.83  593.23 1564.39  663.61 1570.74  692.61 1571.99  706.93 1574.54
  726.56 1576.27  738.05 1576.48  748.94 1579.52   763.3 1580.87  785.74 1580.87
#Mann= 3 , 0 , 0
       0      .1       0  372.78    .045       0  399.94     .12       0
Bank Sta=372.78,399.94
Exp/Cntr=0.5,0.3

Type RM Length L Ch R = 1 ,13628.78,37.13,37.14,37.34
BEGIN DESCRIPTION:
Upstream xs of Bridge 37111-0335
END DESCRIPTION:
XS GIS Cut Line= 3
  1048329.599499   681197.754166  1048469.383507   680994.044532
  1048681.501906   680585.985439
#Sta/Elev= 30
       0    1557    51.7  1555.4    68.8  1553.1   100.5    1544   119.7  1529.3
   137.9  1529.1   172.7  1524.1   190.5  1523.7  204.641521.968   210.7  1516.9
   215.7  1516.7   230.7  1517.1   239.7  1521.7   256.4  1524.6   337.3  1525.9
   405.9  1529.1   449.1  1533.1   462.9  1535.6   479.4  1542.4   489.6  1544.7
   509.2    1545   518.7  1543.1   533.4  1542.1     552  1544.4   565.9  1547.3
   602.5  1551.3   615.4  1554.3   631.3  1555.5   683.6  1563.1     707  1563.2
#Mann= 3 , 0 , 0
       0      .1       0  204.64    .045       0   239.7     .12       0
#XS Ineff= 2 , 0
       0     193  1526.4  242.63       0 1525.09
Permanent Ineff=
       F       F
Bank Sta=204.64,239.7
Exp/Cntr=0.5,0.3

Type RM Length L Ch R = 3 ,13615.07,,,
BEGIN DESCRIPTION:
Bridge : 37111-0335 (gravel road)
END DESCRIPTION:
Bridge Culvert--1,0,-1,-1, 0
Deck Dist Width WeirC Skew NumUp NumDn MinLoCord MaxHiCord MaxSubmerge Is_Ogee
7.7,12,2.6,0, 19, 19, , , 0.95, 0, 0,0,,
       0   140.3   147.5   154.6   164.5   168.5   181.6   182.6   187.8   200.7
   200.7   234.7   234.7   242.1   252.4   254.1   259.1     269     500
    1528  1529.1    1529  1527.9  1527.9  1527.5    1527    1527  1526.8  1526.5
  1529.3  1529.3  1526.5  1526.3  1525.4  1525.2  1525.1  1525.4  1524.6
                                                                                
    1524    1524
   153.7   157.7   170.8   171.8     177   189.9   189.9   223.9   223.9   231.3
   241.6   243.3   248.3   258.2   264.1     273   279.8     288   295.6
  1527.9  1527.5    1527    1527  1526.8  1526.5  1529.3  1529.3  1526.5  1526.3
  1525.4  1525.2  1525.1  1525.4    1525  1526.1  1525.8  1525.6  1525.4
                                                    1524    1524
                                                                        
BR Coef=-1 , 1 , 0 ,, 0 ,,,0.8,0,1.2,0,
WSPro=,,,, 1 ,,,, 0 ,,,, 0 ,,,,-1 ,-1 ,-1 , 0 , 0 , 0 , 0 , 0
BC Design=,, 0 ,, 0 ,,,,,,

Type RM Length L Ch R = 1 ,13591.64,259.21,253.32,246.71
BEGIN DESCRIPTION:
Down stream xs of Bridge 37111-0335
END DESCRIPTION:
XS GIS Cut Line= 3
  1048364.545511   681212.243934  1048504.329519     681008.5343
  1048716.447918   680600.475207
#Sta/Elev= 30
       0  1562.6    44.2  1556.8    89.3  1544.1   110.2  1531.8   121.7  1528.9
   148.2  1528.8   165.8  1526.9   173.8  1524.4     194  1521.5   197.5    1520
   197.9  1518.7   199.9  1516.9   204.9  1516.7   219.9  1517.1   221.9  1518.2
   223.2  1520.3   239.6    1526   260.2  1526.7   302.4  1525.6   331.2  1527.6
   359.6  1530.8   389.1  1531.6   433.6  1536.6   462.1  1542.9   490.2  1543.9
   534.1  1555.5   609.3  1562.1   634.8  1566.7   677.1    1572     707  1572.1
#Mann= 3 , 0 , 0
       0    .095       0   197.5    .045       0   223.2     .12       0
#XS Ineff= 2 , 0
       0  172.47 1524.87               0
Permanent Ineff=
       F       F
Bank Sta=197.5,223.2
Exp/Cntr=0.5,0.3

Type RM Length L Ch R = 1 ,13338.32,300.95,291.74,284.99
XS GIS Cut Line= 3
  1048515.667267   681604.184666  1048714.639396    681120.34292
    1048820.3107   680795.200408
#Sta/Elev= 30
       0 1557.71   34.56 1554.23   65.78 1553.76   82.66 1550.98  130.06  1546.6
  154.95 1547.08  199.62 1549.96  215.76 1549.16  233.06 1546.77  258.43 1547.37
  284.71 1545.97  295.53 1544.36  342.38 1530.28  360.64 1528.63  376.02 1528.84
  407.99 1522.73   447.9  1520.9  460.81 1519.32  476.61  1516.9  486.29 1520.46
  498.12 1521.34  527.45 1525.74  541.13 1531.67  554.55 1540.26   601.9 1552.85
  690.13 1566.71  713.88 1568.52  808.25 1584.65  834.45 1587.76  865.04 1592.82
#Mann= 3 , 0 , 0
       0    .095       0  460.81    .045       0  486.29     .12       0
Bank Sta=460.81,486.29
Exp/Cntr=0.3,0.1

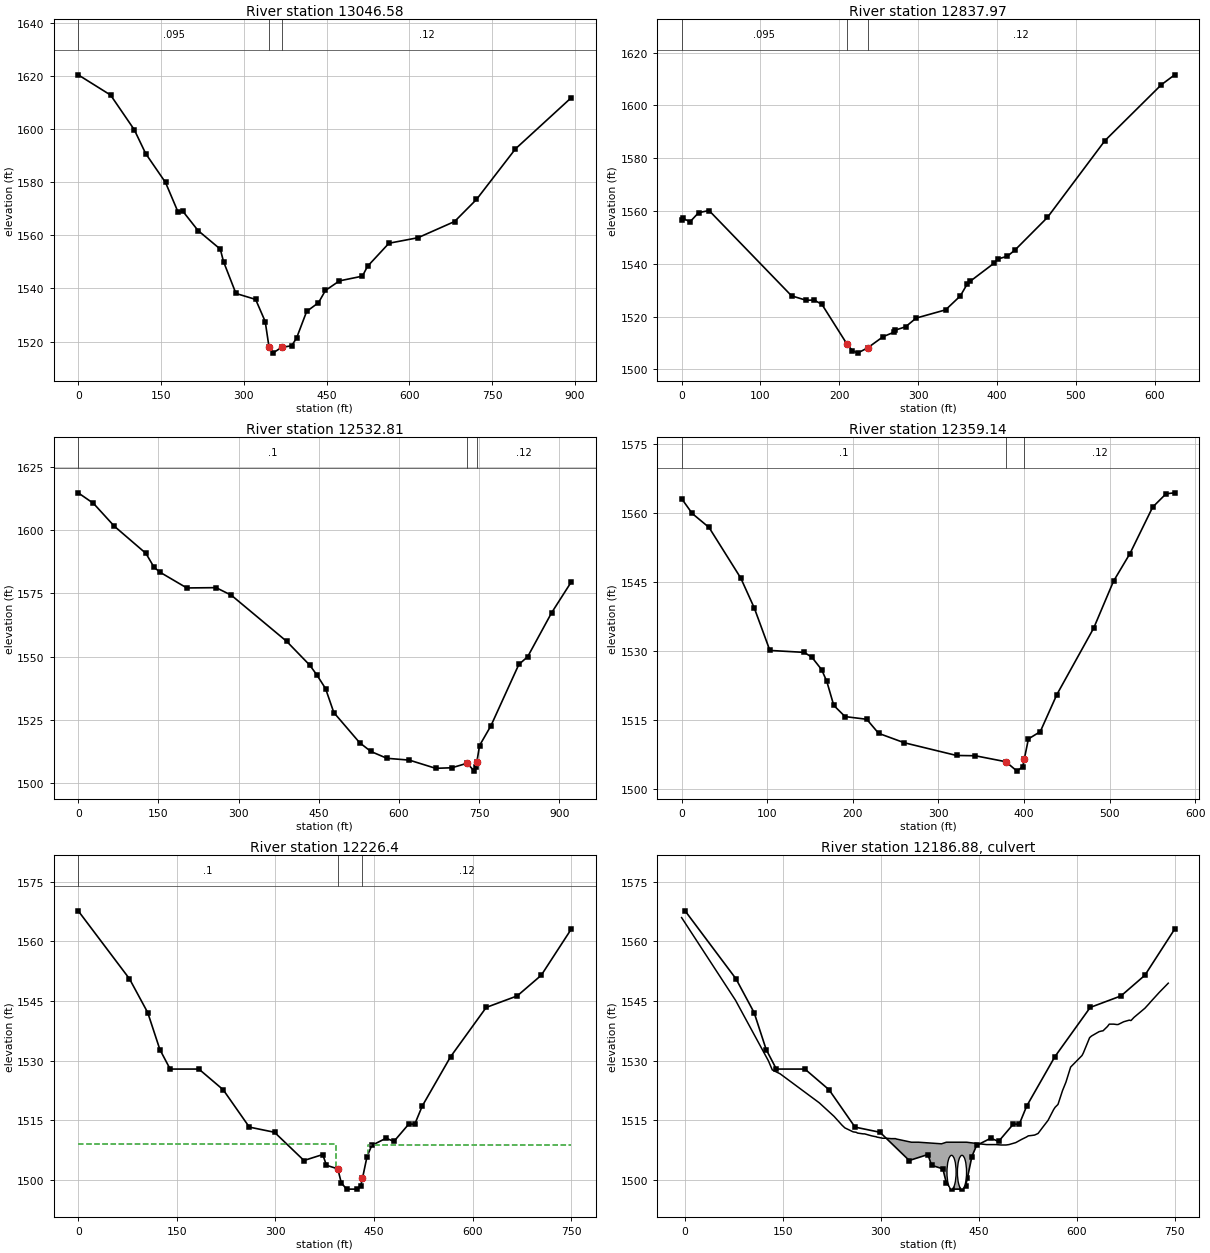
Type RM Length L Ch R = 1 ,13046.58,227.6,208.62,183.71
XS GIS Cut Line= 2
  1048901.081817   681668.637531  1048925.362917   680775.632929
#Sta/Elev= 30
       0 1620.49   58.71 1612.86  101.57 1599.82  122.35 1590.79  158.22 1579.92
  180.88  1568.8  189.64 1569.07  217.11 1561.82  257.45 1554.81   263.3 1550.11
   285.8 1538.11  321.48 1535.86  338.85 1527.52  345.59 1518.11  352.65 1515.62
  368.42 1517.78  386.71  1518.4  395.61 1521.28  413.95 1531.34  435.37 1534.62
  447.99 1539.24  473.35 1542.85   514.9 1544.62  524.19 1548.32  563.06 1557.03
  615.56  1559.1  681.91 1565.21  721.66 1573.53  792.32  1592.6  893.33 1611.86
#Mann= 3 , 0 , 0
       0    .095       0  345.59    .049       0  368.42     .12       0
Bank Sta=345.59,368.42
Exp/Cntr=0.3,0.1

Type RM Length L Ch R = 1 ,12837.97,297.86,305.15,311.31
XS GIS Cut Line= 4
  1049118.389463   681384.270453  1049084.841631   681208.144274
   1049042.90682   681147.338822  1049017.745965    680776.21586
#Sta/Elev= 30
       0 1556.77    1.44 1557.23   10.73 1555.92   21.54 1559.36    34.8 1560.17
  139.37 1527.85  157.74 1526.17  168.17 1526.22  177.88  1524.6  209.54 1509.61
  216.28 1507.11  223.03 1506.12     236 1508.14  255.56 1512.37  268.78 1513.99
  270.56 1514.81  283.95  1516.1  297.32  1519.4  334.74 1522.53  353.34 1527.79
  361.94 1532.22  365.89 1533.36  395.92 1540.16  400.66 1541.77  413.01 1542.85
  422.79 1545.23  463.82 1557.56   536.8  1586.7  608.21 1607.85  625.13 1611.62
#Mann= 3 , 0 , 0
       0    .095       0  209.54    .049       0     236     .12       0
Bank Sta=209.54,236
Exp/Cntr=0.3,0.1

Type RM Length L Ch R = 1 ,12532.81,155.85,173.68,191.15
XS GIS Cut Line= 3
  1049235.621318    681649.75221  1049224.829723   680953.694276
  1049141.194828   680743.258143
#Sta/Elev= 30
       0 1614.78   28.63  1610.6   67.47 1601.61  126.78 1590.84  141.78 1585.42
  152.99 1583.42  203.23 1577.19  257.95 1577.31  286.49 1574.33  390.03  1556.1
   433.4 1546.66  446.91 1542.72   462.9  1537.4  478.31 1527.96   526.7 1516.03
  547.68 1512.58  577.63 1509.88  619.64 1509.16   668.9 1505.92   699.2 1506.14
  727.73 1507.92  741.25 1504.81  744.57 1506.36  745.85 1508.24  750.97 1514.91
  772.31 1522.74  824.52 1546.96  841.04 1550.02     886 1567.44  922.59 1579.55
#Mann= 3 , 0 , 0
       0      .1       0  727.73    .049       0  745.85     .12       0
Bank Sta=727.73,745.85
Exp/Cntr=0.3,0.1

Type RM Length L Ch R = 1 ,12359.14,122.7,132.74,142.78
XS GIS Cut Line= 2
  1049294.515643   681302.078244  1049411.933057   680738.055186
#Sta/Elev= 30
       0 1563.17    12.4 1559.94   32.03 1556.91    69.1 1545.92   84.89 1539.43
  103.13 1530.19  143.14 1529.77  152.15 1528.73  163.61 1526.02  169.65 1523.46
  177.79 1518.25  190.98 1515.82  216.34 1515.23   230.2 1512.18  260.27 1510.13
  321.26 1507.37  343.12 1507.31  378.86 1506.01  391.92 1503.97  398.57 1504.95
  400.48 1506.64  405.24 1510.97  419.09 1512.55  438.49 1520.61  481.48 1535.03
   504.7 1545.24   523.9 1551.24  550.44 1561.33  566.11 1564.23  576.12 1564.43
#Mann= 3 , 0 , 0
       0      .1       0  378.86    .049       0  400.48     .12       0
Bank Sta=378.86,400.48
Exp/Cntr=0.5,0.3

Type RM Length L Ch R = 1 ,12226.4 ,88.66,88.64,88.63
BEGIN DESCRIPTION:
Upstream xs of Bridge 37111-0256
END DESCRIPTION:
XS GIS Cut Line= 5
  1049351.490685   681344.123388  1049446.057413   681050.818597
   1049524.29649   680918.621542  1049553.973407   680878.153068
  1049542.760245   680640.147811
#Sta/Elev= 30
       0  1567.7      78  1550.6   105.8  1542.1   124.3  1532.8   139.9  1527.9
   183.6  1527.9   220.6  1522.7   260.4  1513.3   298.7    1512   343.5  1504.9
   372.1  1506.4   377.7  1503.7     395  1502.8   400.3  1499.3   408.3  1497.7
   424.3  1497.7  429.82 1498.52  432.58 1500.46   439.5  1505.9   446.7  1508.7
   468.4  1510.5   480.4  1509.7   503.2  1514.1     512    1514   523.5  1518.6
   566.6    1531   620.8  1543.4     668  1546.3   704.6  1551.5   750.2  1563.1
#Mann= 3 , 0 , 0
       0      .1       0     395    .047       0  432.58     .12       0
#XS Ineff= 2 , 0
       0   391.8 1509.15   440.8       0  1508.9
Permanent Ineff=
       F       F
Bank Sta=395,432.58
Exp/Cntr=0.5,0.3

Type RM Length L Ch R = 2 ,12186.88,,,
BEGIN DESCRIPTION:
Culvert : 37111-0256 (SR-1104)
END DESCRIPTION:
Bridge Culvert--1,0,-1,-1, 0
Deck Dist Width WeirC Skew NumUp NumDn MinLoCord MaxHiCord MaxSubmerge Is_Ogee
9.5,60,2.6,0, 78, 42, , , 0.95, 0, 0,0,,
    -5.3    77.3   127.6   133.6   145.7   205.7   228.3   240.4   244.9   257.6
   262.1   264.3   272.7   275.1   285.8   291.8   292.6   293.6   302.9   305.5
   307.8   308.9   315.9   322.5   323.9   346.8   357.8     393   400.3   400.3
   431.3   431.3   456.1   456.5     462   464.1   476.9   484.2   491.7   496.2
   506.7   515.6     523     526   531.3   535.6   540.9   547.3   556.2   564.7
   567.1   571.4   578.4   583.6   590.8   608.2   609.8   610.4   619.9   622.7
   634.3     639   640.3   647.2     650   656.9   661.2   663.5   672.1   680.6
   683.3   687.9   704.6   711.3   712.8   725.6   726.1   740.4
    1566  1545.2    1530  1527.7  1526.7  1519.4    1516  1513.8  1513.1  1512.1
    1512  1511.8  1511.6  1511.6  1511.1  1510.9  1510.9  1510.8  1510.5  1510.5
  1510.5  1510.5  1510.4  1510.4  1510.3  1509.5  1509.5  1509.1  1509.5  1509.5
  1509.5  1509.5    1509    1509  1508.9  1508.9  1508.9  1508.8  1508.8  1508.9
  1509.4  1510.2  1510.8  1511.1  1511.2  1511.3  1511.7  1513.1    1515  1517.7
  1518.3    1519  1522.5  1524.6  1528.4  1531.3  1531.8    1532  1535.8  1536.2
  1537.3  1537.5  1537.5  1538.6  1539.2  1539.2  1539.1  1539.1  1539.8  1540.2
  1540.1  1540.9  1543.2  1544.4  1544.7    1547  1547.1  1549.5
                                                                                
                                                                                
                                                                                
                                                                                
                                                                                
                                                                                
                                                                                
                                                                
   300.3   307.3   313.9   315.4   322.7   328.5   332.3   338.2   343.2   349.2
   353.7   357.7     366   369.2   372.2   382.4   384.4   391.8   391.8   422.8
   422.8   447.6   447.9   453.5   455.5   468.3   475.7   483.2   487.6   498.1
     507   514.4   517.4   522.7     527   532.3   538.7   547.6   556.2   558.6
   562.8     660
  1510.5  1510.4  1510.4  1510.3    1510  1509.9  1509.8  1509.5  1509.6  1509.5
  1509.2  1509.4  1509.3  1509.2  1509.3  1509.2  1509.1  1509.5  1509.5  1509.5
  1509.5    1509    1509  1508.9  1508.9  1508.9  1508.8  1508.8  1508.9  1509.4
  1510.2  1510.8  1511.1  1511.2  1511.3  1511.7  1513.1    1515  1517.7  1518.3
    1519 1525.05
                                                                                
                                                                                
                                                                                
                                                                                
                
BR Coef=-1 , 0 , 0 ,, 0 ,,,0.8,-1,,0,
WSPro=,,,, 1 ,,,, 0 ,,,, 0 ,,,,-1 ,-1 ,-1 , 0 , 0 , 0 , 0 , 0
Multiple Barrel Culv=4,8.5,14,60,0.024,0.5,1,29,1,1497.7,1497.7, 2,Culvert #1  , 0 ,9.5
   408.3   399.8   424.3   415.8
Culvert Bottom n=0.024
BC Design=,, 0 ,, 0 ,,,,,,

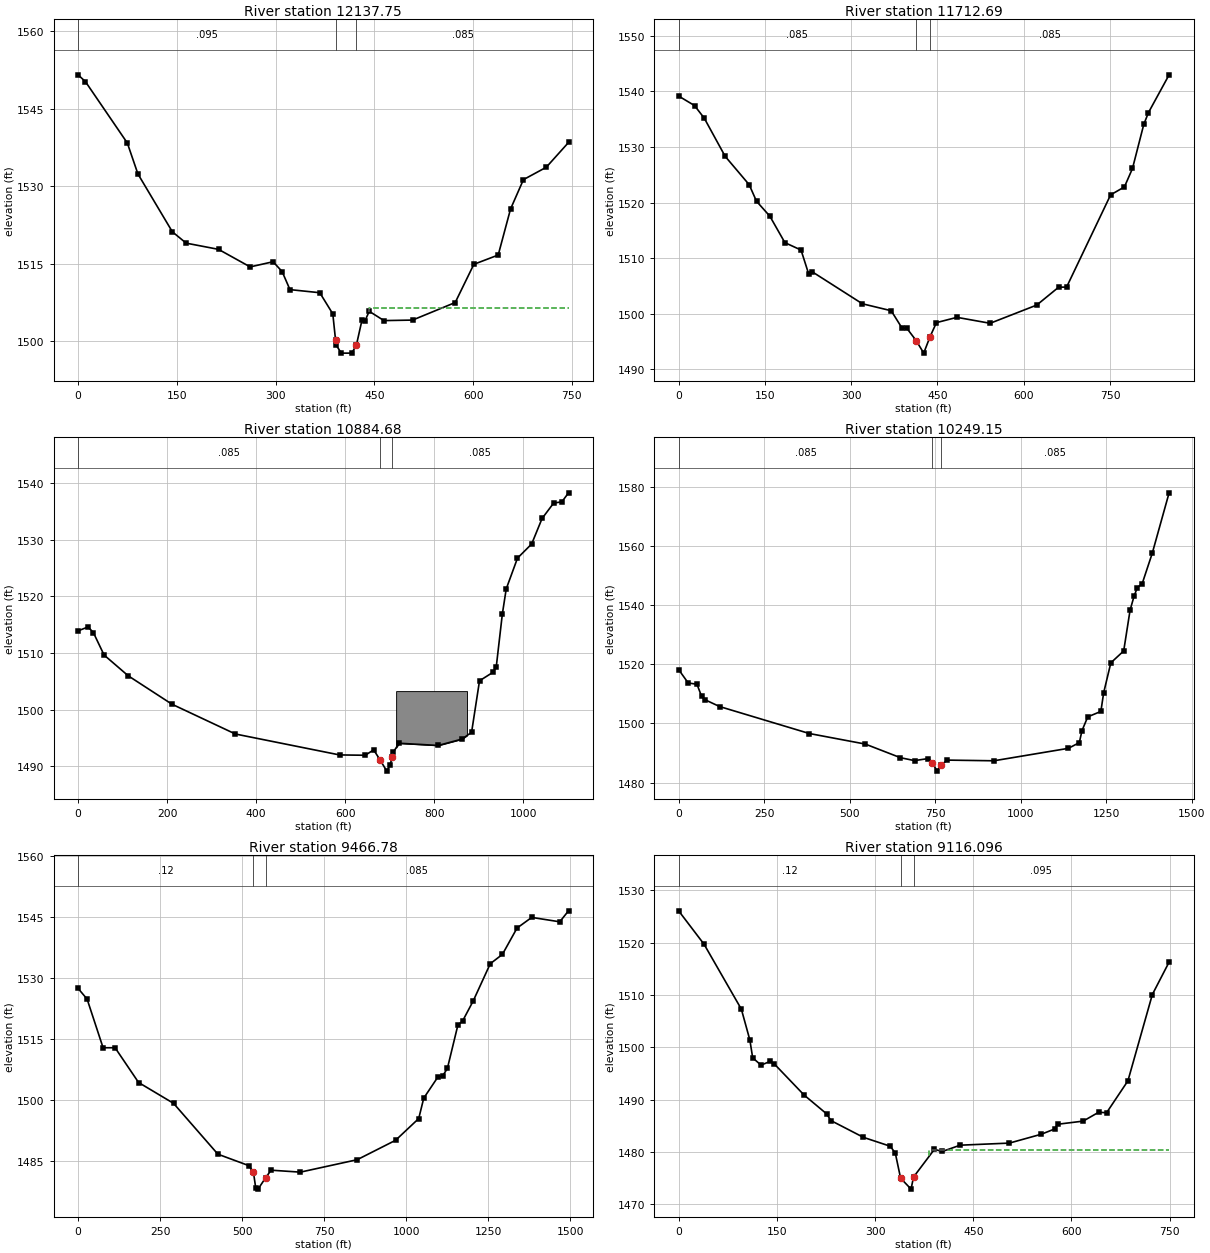
Type RM Length L Ch R = 1 ,12137.75,464.2,425.06,385.73
BEGIN DESCRIPTION:
Down stream xs of Bridge 37111-0256
END DESCRIPTION:
XS GIS Cut Line= 5
  1049440.521358   681363.008709  1049535.088086   681069.703918
  1049613.327164   680937.506863  1049643.004081   680897.038389
  1049618.638667   680665.440593
#Sta/Elev= 30
       0  1551.6    11.1  1550.3    74.8  1538.4    90.9  1532.4   143.2  1521.2
   164.2    1519   213.3  1517.8   261.4  1514.4   296.2  1515.4   309.9  1513.5
   321.8    1510   367.1  1509.4   386.9  1505.3  391.02 1500.28   391.8  1499.3
   399.8  1497.7   415.8  1497.7   422.8  1499.3   431.2  1504.1   435.9    1504
   442.2  1505.8   464.6    1504     508  1504.1   572.8  1507.5   601.1  1514.9
   638.1  1516.7   656.8  1525.6   676.4  1531.3   711.1  1533.7   744.9  1538.5
#Mann= 3 , 0 , 0
       0    .095       0  391.02     .05       0   422.8    .085       0
#XS Ineff= 2 , 0
       0                   441.9       0  1506.4
Permanent Ineff=
       F       F
Bank Sta=391.02,422.8
Exp/Cntr=0.5,0.3

Type RM Length L Ch R = 1 ,11712.69,816.88,828.01,838.23
XS GIS Cut Line= 3
  1050263.605159    681196.58947  1049939.014198   680859.352099
  1049660.793329    680593.77764
#Sta/Elev= 30
       0 1539.16   27.63 1537.45    44.6 1535.17   80.83 1528.32  122.64 1523.21
  135.38 1520.23  158.59 1517.54  184.74 1512.78   212.8 1511.45  226.32 1507.07
  232.07 1507.55  319.46 1501.78  369.55 1500.53  388.71 1497.35  396.23 1497.44
  413.01 1495.15  426.09  1492.9  437.05 1495.85  448.23 1498.39  483.87 1499.34
  541.52 1498.27  622.63 1501.55  660.72 1504.77  674.47 1504.78  751.03 1521.38
  775.02 1522.81  789.04 1526.13  808.67 1534.06  816.79 1536.18  852.69 1542.98
#Mann= 3 , 0 , 0
       0    .085       0  413.01    .049       0  437.05    .085       0
Bank Sta=413.01,437.05
Exp/Cntr=0.3,0.1

Type RM Length L Ch R = 1 ,10884.68,617.99,635.53,650.99
XS GIS Cut Line= 3
  1050680.409493   680825.101409  1050364.249472   680150.626666
  1050148.206758   679866.082612
#Sta/Elev= 30
       0 1513.89   22.57 1514.59   34.52 1513.57   58.44 1509.63  112.75 1505.96
  210.99 1500.95  353.55 1495.69   587.5    1492  645.28 1491.94  664.33 1492.89
  678.39 1491.15  693.83 1489.14  701.14  1490.2  705.96 1491.62  708.72 1492.52
  721.26 1494.06  809.43 1493.67   862.6 1494.79  884.32 1495.99  902.13 1505.08
  932.59 1506.59  939.83 1507.59  953.45 1516.87  962.15 1521.29  987.48 1526.73
  1019.3 1529.22 1042.71 1533.72 1068.67 1536.44  1087.2 1536.66 1102.17 1538.25
#Mann= 3 , 0 , 0
       0    .085       0  678.39    .049       0  705.96    .085       0
#Block Obstruct= 1 ,-1
  714.74  874.06 1503.26
Bank Sta=678.39,705.96
Exp/Cntr=0.3,0.1

Type RM Length L Ch R = 1 ,10249.15,752.06,782.37,801.83
XS GIS Cut Line= 3
  1050854.297546   680840.909432  1050954.414892   680045.239954
  1051033.387041   679418.118169
#Sta/Elev= 30
       0 1518.25   27.87 1513.71   53.58 1513.27   67.19 1509.17   78.42 1507.96
  119.96 1505.72  382.11  1496.6  545.67 1493.03  648.68 1488.41  689.79 1487.43
  730.11 1488.13  742.01  1486.7  755.46 1483.87  767.76 1486.03  785.99  1487.6
  921.73 1487.37  1139.7 1491.59 1171.56 1493.52 1179.17 1497.52  1196.2 1502.24
 1234.58 1504.08 1242.65 1510.38 1263.66 1520.52 1301.27 1524.55  1319.9 1538.33
    1332 1543.23 1341.24    1546 1355.23 1547.29 1384.83 1557.63 1434.02 1578.06
#Mann= 3 , 0 , 0
       0    .085       0  742.01    .049       0  767.76    .085       0
Bank Sta=742.01,767.76
Exp/Cntr=0.3,0.1

Type RM Length L Ch R = 1 ,9466.78 ,346.8,350.68,354.43
XS GIS Cut Line= 3
  1050961.133429   680868.351367  1051435.942857   680481.278436
   1052251.37648   680145.815256
#Sta/Elev= 30
       0 1527.36   27.53 1524.73   76.24 1512.75  112.75 1512.76  184.41  1504.2
  290.95 1499.07  426.02 1486.56  520.03 1483.75  534.21 1482.19  541.17 1478.32
  548.27 1477.96  571.82  1480.8  588.05 1482.62  677.29 1482.14   850.4  1485.2
  967.39 1489.98 1037.92 1495.33 1053.18 1500.35 1096.76 1505.61 1110.67 1505.82
 1125.18 1507.65 1157.24 1518.34 1171.52 1519.33 1204.01 1524.29 1255.84 1533.43
 1292.86 1535.73 1337.47 1542.21 1382.16 1544.83 1467.54 1543.75 1494.33 1546.45
#Mann= 3 , 0 , 0
       0     .12       0  534.21    .049       0  571.82    .085       0
Bank Sta=534.21,571.82
Exp/Cntr=0.5,0.3

Type RM Length L Ch R = 1 ,9116.096,59.69,59.97,60.71
BEGIN DESCRIPTION:
Upstream xs of Bridge 37111-0254
END DESCRIPTION:
XS GIS Cut Line= 2
  1051254.078131   681010.871305  1051887.638057   680611.125128
#Sta/Elev= 30
       0  1526.1    38.9  1519.7    95.8  1507.3   108.8  1501.4   113.1    1498
   125.9  1496.6   139.2  1497.3   145.6  1496.9   191.5  1490.9   225.9  1487.3
   232.7    1486   282.2  1482.8   323.2  1481.1   330.9  1479.8     339    1475
     355  1472.9  358.721475.203   390.6  1480.5   402.8  1480.1     430  1481.3
   505.2  1481.7   554.1  1483.4   574.3  1484.4   578.8  1485.3   617.8  1485.9
   641.6  1487.6   653.6  1487.5   686.2  1493.6   723.5  1510.1   749.1  1516.3
#Mann= 3 , 0 , 0
       0     .12       0     339    .049       0  358.72    .095       0
#XS Ineff= 2 , 0
       0                   382.7       0  1480.4
Permanent Ineff=
       F       F
Bank Sta=339,358.72
Exp/Cntr=0.5,0.3