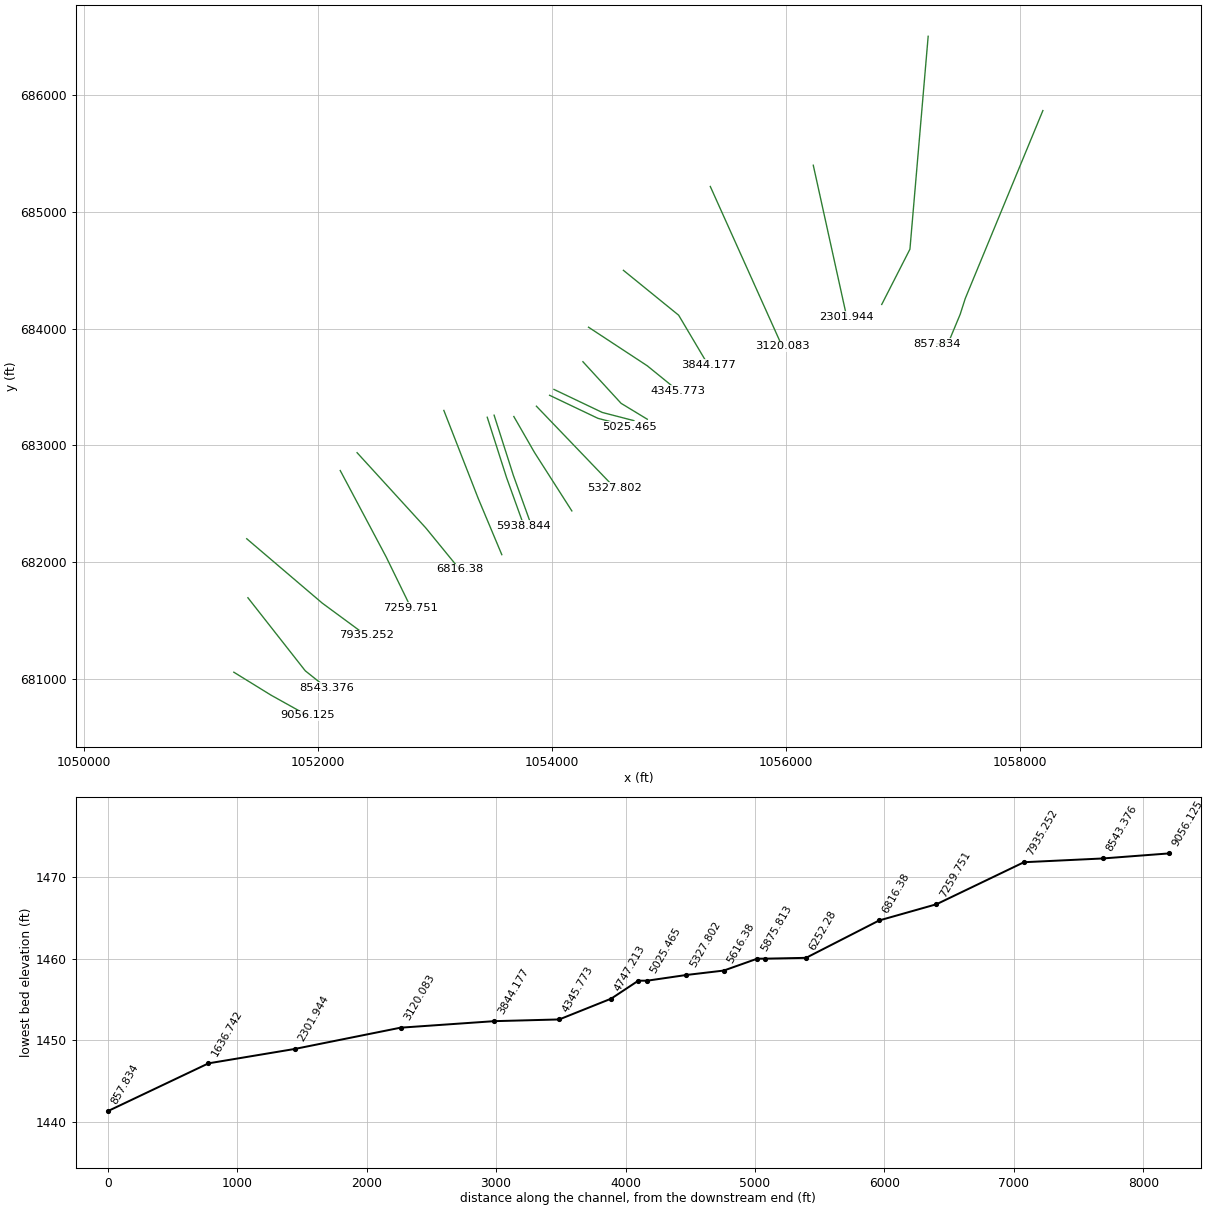
HEC-RAS study Lt_Crooked_Cr.prj: Lt_Crooked_Cr

--- Lt_Crooked_Cr.g02 (geometry) --- (continued)

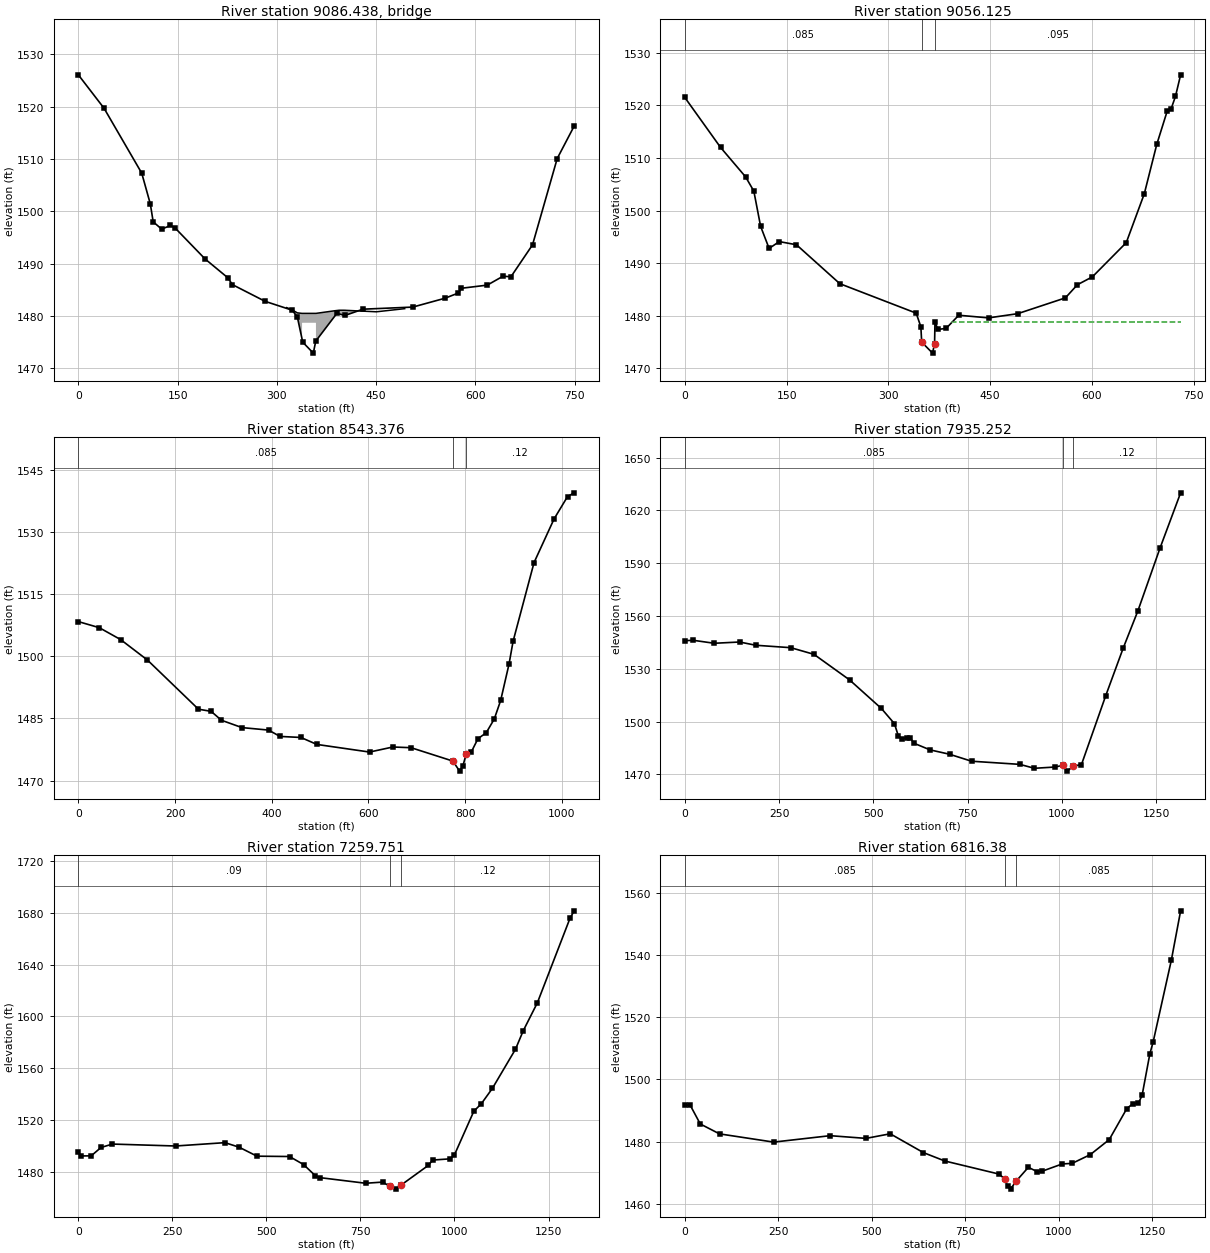
Type RM Length L Ch R = 3 ,9086.438,,,
BEGIN DESCRIPTION:
Bridge : 37111-0254 (Cherry Springs Rd.)
END DESCRIPTION:
Bridge Culvert--1,0,-1,-1, 0
Deck Dist Width WeirC Skew NumUp NumDn MinLoCord MaxHiCord MaxSubmerge Is_Ogee
23.7,12,2.6,0, 12, 41, , , 0.95, 0, 0,0,,
   314.7   321.2   330.8     338     338     359     359   387.4   394.1   401.4
   450.3   493.1
  1481.6  1481.3  1480.6  1480.5  1480.5  1480.5  1480.5    1481  1481.1  1481.1
  1480.8  1481.4
                                  1478.7  1478.7
                
   309.1   320.8   324.6   331.1   340.6     348     348     369     369   397.3
     404   454.7   536.3   546.4   550.2   560.8   564.5   575.7     579   590.3
   593.3     605   607.9   620.6   631.2   636.3     646   655.3   660.7   665.4
   666.2   681.2   682.7   692.6   698.8   704.3     711   736.2   739.7   741.1
     745
  1482.2    1482  1481.6  1481.3  1480.6  1480.5  1480.5  1480.5  1480.5    1481
  1481.1  1480.8  1482.7  1483.1  1483.2  1483.6    1484    1485  1485.1  1485.4
  1485.5  1485.7  1486.2  1487.7  1488.5  1489.4  1490.7  1491.3  1491.8  1492.7
    1493  1497.4  1498.1    1503  1505.9  1508.9  1511.1  1518.8  1520.6  1521.4
  1522.9
                                                  1478.7  1478.7
                                                                                
                                                                                
                                                                                
        
BR Coef=-1 , 1 , 0 ,, 0 ,,,0.75,-1,1.2,0,
WSPro=,,,, 1 ,,,, 0 ,,,, 0 ,,,,-1 ,-1 ,-1 , 0 , 0 , 0 , 0 , 0
BC Design=,, 0 ,, 0 ,,,,,,

Type RM Length L Ch R = 1 ,9056.125,521.35,512.75,502.37
BEGIN DESCRIPTION:
Down stream xs of Bridge 37111-0254
END DESCRIPTION:
XS GIS Cut Line= 3
  1051279.219374   681061.153829  1051597.837025   680864.630165
  1051909.008154   680691.456697
#Sta/Elev= 30
       0  1521.5    52.7    1512    89.6  1506.4   101.7  1503.7   111.7    1497
   124.2  1492.8   139.2  1494.1   164.5  1493.5   228.4  1486.1   340.9  1480.5
   347.8  1477.9     349    1475     365  1472.9     368  1474.7   368.6  1478.9
   372.7  1477.4     385  1477.6   403.6  1480.1   447.6  1479.6   490.5  1480.4
   560.7  1483.4   578.4  1485.9   600.5  1487.4   650.4  1493.9     677  1503.2
   695.4  1512.6   710.7  1518.9   716.4  1519.3   722.9  1521.7   730.5  1525.8
#Mann= 3 , 0 , 0
       0    .085       0     349    .049       0     368    .095       0
#XS Ineff= 2 , 0
       0                   393.3       0  1478.9
Permanent Ineff=
       F       F
Bank Sta=349,368
Exp/Cntr=0.5,0.3

Type RM Length L Ch R = 1 ,8543.376,597.84,608.12,607.76
XS GIS Cut Line= 3
  1051399.816071   681697.719595  1051890.108424    681073.24197
  1052070.742433   680928.734747
#Sta/Elev= 30
       0 1508.35   43.35 1506.88   87.46 1504.01  142.96 1499.07  248.35 1487.22
  274.55  1486.7  295.94 1484.55  338.38 1482.78  393.37 1482.18  417.03 1480.65
  460.24  1480.4  493.19 1478.72  602.19 1476.88  650.39  1478.1  688.12 1477.93
  774.58  1474.7  788.36 1472.28     795 1473.48  802.01 1476.34  812.09 1476.79
  826.43 1480.12  843.36 1481.52  860.11 1484.86  873.31 1489.33  890.59  1498.1
  899.04 1503.62  942.34 1522.59  983.77 1533.12 1011.67 1538.52 1025.28 1539.41
#Mann= 3 , 0 , 0
       0    .085       0  774.58    .049       0  802.01     .12       0
Bank Sta=774.58,802.01
Exp/Cntr=0.3,0.1

Type RM Length L Ch R = 1 ,7935.252,685.68,675.5,657.2
XS GIS Cut Line= 3
  1051389.494121   682202.462647  1052036.196977   681651.378241
  1052411.082735   681375.610652
#Sta/Elev= 30
       0 1545.95   22.45 1546.16   78.11 1544.47  145.41 1545.19  188.29 1543.34
  281.23 1541.96  342.55 1538.19  436.93 1523.67  521.26 1507.45  556.01 1498.78
  566.13    1492  575.44 1490.12  590.45 1490.85  598.07 1490.47  608.49  1487.6
  650.61 1483.89  702.15 1481.42  760.51 1477.45  888.71 1475.66  927.18 1473.43
  981.27 1474.14 1001.81 1475.04  1014.6 1471.82 1030.67 1474.73 1052.05 1475.53
 1116.33 1514.64 1162.67 1541.68 1201.66 1562.86 1260.28  1598.5 1315.05 1629.96
#Mann= 3 , 0 , 0
       0    .085       0 1001.81    .049       0 1030.67     .12       0
Bank Sta=1001.81,1030.67
Exp/Cntr=0.3,0.1

Type RM Length L Ch R = 1 ,7259.751,435.6,443.37,449.89
XS GIS Cut Line= 3
  1052189.444819   682785.652511  1052581.678686   682047.633513
  1052793.278544   681614.111846
#Sta/Elev= 30
       0 1495.05    6.24 1492.29   34.22 1492.36   60.21 1498.82   90.63 1501.46
  258.64 1499.97  389.81 1502.55  427.51 1499.04     475 1492.11  561.42 1491.85
  598.75 1485.65  630.41 1476.94  642.35 1475.54  763.92  1471.2  809.76 1472.12
  828.29  1468.7  843.65 1466.67  858.22 1469.84  930.59 1485.03  941.91 1489.11
  988.91 1490.07  999.82 1493.05 1051.46 1526.82 1071.51 1532.64 1100.73 1544.44
 1162.15 1574.65 1182.89    1589 1220.43 1610.58 1306.96 1675.67 1318.18 1681.54
#Mann= 3 , 0 , 0
       0     .09       0  828.29    .049       0  858.22     .12       0
Bank Sta=828.29,858.22
Exp/Cntr=0.3,0.1

Type RM Length L Ch R = 1 ,6816.38 ,571.41,564.1,550.56
XS GIS Cut Line= 3
  1052333.435909   682938.417308  1052921.052084   682294.967524
  1053209.059313   681942.526809
#Sta/Elev= 30
       0  1491.7   14.11 1491.78   41.39 1485.66   92.88 1482.47  237.73 1479.82
  388.87 1481.89  484.79 1481.02  549.57  1482.5  638.38 1476.44   695.6 1473.74
  841.53  1469.5  855.95 1467.89  863.46 1465.67  871.39 1464.68  886.86  1467.3
  919.15 1471.71  943.56 1470.25  955.11 1470.41 1009.79 1472.79 1036.19 1472.97
 1084.77 1475.78 1135.52 1480.62  1182.4 1490.58 1198.21 1492.16 1213.53 1492.37
  1223.4 1494.84  1244.3  1508.3 1252.74 1511.93 1301.55 1538.31 1326.54 1554.29
#Mann= 3 , 0 , 0
       0    .085       0  855.95    .049       0  886.86    .085       0
Bank Sta=855.95,886.86
Exp/Cntr=0.3,0.1

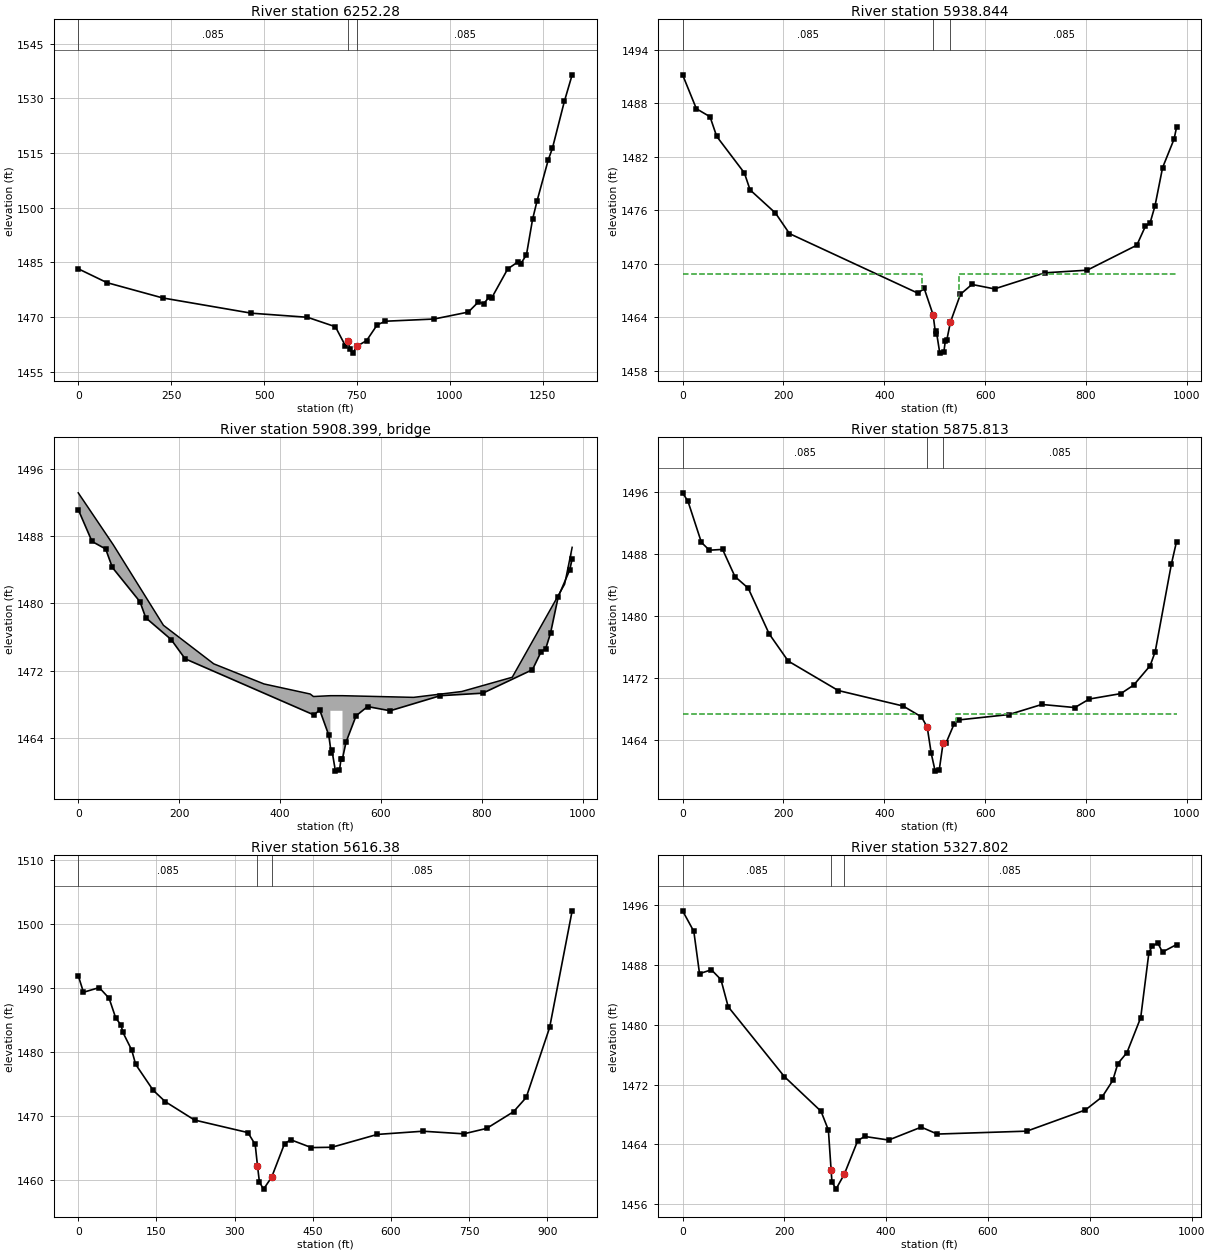
Type RM Length L Ch R = 1 ,6252.28 ,314.34,313.44,308.85
XS GIS Cut Line= 3
  1053075.583733   683299.685325  1053369.759152   682546.183403
  1053571.037061      682066.213
#Sta/Elev= 30
       0 1483.23   77.24 1479.43  227.46 1475.23  466.16 1471.05  616.94 1469.93
  692.09 1467.34  718.75 1462.17   726.2 1463.34  731.65 1461.27   738.3  1460.1
   751.6 1462.08  776.08 1463.54   804.6 1467.85  826.82 1468.85  957.75 1469.45
 1049.99 1471.36 1076.42 1474.08 1091.21 1473.67 1105.89 1475.44 1113.41 1475.35
 1155.98 1483.19 1184.02 1485.16 1191.34 1484.66 1206.39 1487.08  1222.8 1496.78
 1235.07 1501.91 1265.13 1513.13 1276.22 1516.27 1308.36 1529.13 1329.36 1536.42
#Mann= 3 , 0 , 0
       0    .085       0   726.2    .049       0   751.6    .085       0
Bank Sta=726.2,751.6
Exp/Cntr=0.5,0.3

Type RM Length L Ch R = 1 ,5938.844,61.58,63.03,64.32
BEGIN DESCRIPTION:
Upstream xs of Bridge 37111-0246
END DESCRIPTION:
XS GIS Cut Line= 3
  1053446.566535   683241.497896  1053611.717657   682725.400668
  1053760.019016   682313.785931
#Sta/Elev= 30
       0  1491.2    27.3  1487.4    54.4  1486.5    67.6  1484.3   122.5  1480.2
   133.8  1478.3   184.2  1475.7   211.9  1473.4   467.4  1466.7   478.8  1467.3
  496.681464.304   501.6  1462.2     503  1462.5     510    1460     518  1460.1
     521  1461.4     524  1461.5  531.151463.486     551  1466.6   573.7  1467.7
   618.5  1467.2     718    1469   802.3  1469.3   900.7  1472.1   917.5  1474.2
     927  1474.6   936.7  1476.5   951.8  1480.8   974.6    1484   979.4  1485.3
#Mann= 3 , 0 , 0
       0    .085       0  496.68    .049       0  531.15    .085       0
#XS Ineff= 2 , 0
       0   475.6  1468.9   548.4       0  1468.9
Permanent Ineff=
       F       F
Bank Sta=496.68,531.15
Exp/Cntr=0.5,0.3

Type RM Length L Ch R = 3 ,5908.399,,,
BEGIN DESCRIPTION:
Bridge : 37111-0246 (Gravel Road)
END DESCRIPTION:
Bridge Culvert--1,0,-1,-1, 0
Deck Dist Width WeirC Skew NumUp NumDn MinLoCord MaxHiCord MaxSubmerge Is_Ogee
24.4,12,2.6,0, 16, 16, , , 0.95, 0, 0,0,,
       0    69.5   168.9   268.7   368.4     460   466.4     500     500     524
     524     665   760.7   860.6   964.5   979.4
  1493.2    1487  1477.4  1472.8  1470.4  1469.2  1468.9    1469    1469    1469
    1469  1468.8  1469.5  1471.2  1482.3  1486.7
                                                                  1467.2  1467.2
                                                
    -6.1    63.4   162.8   262.6   360.8   424.7   460.3   490.8   490.8   514.8
   514.8   658.9   754.6   854.6   958.4   973.3
  1493.2    1487  1477.4  1472.8  1470.4  1469.2  1468.9    1469    1469    1469
    1469  1468.8  1469.5  1471.2  1482.3  1486.7
                                                                  1467.2  1467.2
                                                
BR Coef=-1 , 1 , 0 ,, 0 ,,,0.8,0,1.2,0,
WSPro=,,,, 1 ,,,, 0 ,,,, 0 ,,,,-1 ,-1 ,-1 , 0 , 0 , 0 , 0 , 0
BC Design=,, 0 ,, 0 ,,,,,,

Type RM Length L Ch R = 1 ,5875.813,252.58,259.43,267.04
BEGIN DESCRIPTION:
Down stream xs of Bridge 37111-0246
END DESCRIPTION:
XS GIS Cut Line= 3
   1053505.25996   683259.105897  1053670.411082   682743.008669
  1053818.712441   682331.393931
#Sta/Elev= 30
       0  1495.9    10.7  1494.8    37.3  1489.5    53.2  1488.5    79.3  1488.6
   103.8  1485.1   130.1  1483.6   171.7  1477.7   209.4  1474.2   308.5  1470.4
   437.2  1468.4   473.6    1467  485.041465.683     493  1462.3   500.8    1460
   508.8  1460.1  516.451463.577   522.2  1463.6   538.5  1466.1   547.2  1466.6
   647.3  1467.3   712.4  1468.6   777.7  1468.2   806.5  1469.3     869    1470
   894.5  1471.1   927.1  1473.6   937.1  1475.4   969.2  1486.7   979.4  1489.6
#Mann= 3 , 0 , 0
       0    .085       0  485.04    .049       0  516.45    .085       0
#XS Ineff= 2 , 0
       0   464.2  1467.4   541.4       0  1467.4
Permanent Ineff=
       F       F
Bank Sta=485.04,516.45
Exp/Cntr=0.5,0.3

Type RM Length L Ch R = 1 ,5616.38 ,281.27,288.58,295.15
XS GIS Cut Line= 3
  1053673.952901   683247.670825  1053851.112277   682939.422971
  1054169.912225   682440.636452
#Sta/Elev= 30
       0 1491.95   10.03 1489.34    40.3 1490.07   59.22  1488.4   71.98  1485.3
   82.27  1484.2   85.35 1483.12  102.63 1480.29  110.12 1478.06   143.7 1474.01
  167.02 1472.22  223.09 1469.35  325.39 1467.39  339.47 1465.53  343.83 1462.21
   347.6 1459.63  355.53 1458.54  371.08 1460.42  395.85 1465.67   407.8 1466.26
  447.18 1465.04  486.62 1465.09  573.79  1467.1  661.33  1467.6  739.66 1467.19
  783.48 1468.04  835.08 1470.65  859.34 1472.88  904.31 1483.83  947.49 1502.08
#Mann= 3 , 0 , 0
       0    .085       0  343.83    .049       0  371.08    .085       0
Bank Sta=343.83,371.08
Exp/Cntr=0.3,0.1

Type RM Length L Ch R = 1 ,5327.802,289.59,302.34,312.81
XS GIS Cut Line= 2
  1053867.026323   683336.068818  1054538.902461   682636.002023
#Sta/Elev= 30
       0 1495.25   22.05  1492.5   33.26 1486.84   56.54 1487.36   75.27 1486.05
   89.57 1482.41  199.94 1473.06  271.93 1468.42  286.43  1465.9  291.74 1460.54
  293.38 1458.99  301.35    1458  317.74 1460.01  344.08 1464.49  357.56 1465.05
  404.82 1464.57  468.76  1466.3   500.4 1465.37  676.22 1465.76  791.39  1468.6
  824.41 1470.36  845.03 1472.54  855.07  1474.8     873 1476.28  899.96 1480.95
   916.1 1489.67  922.56 1490.52  933.43 1490.94   942.8 1489.74  970.31 1490.73
#Mann= 3 , 0 , 0
       0    .085       0  291.74    .049       0  317.74    .085       0
Bank Sta=291.74,317.74
Exp/Cntr=0.5,0.3

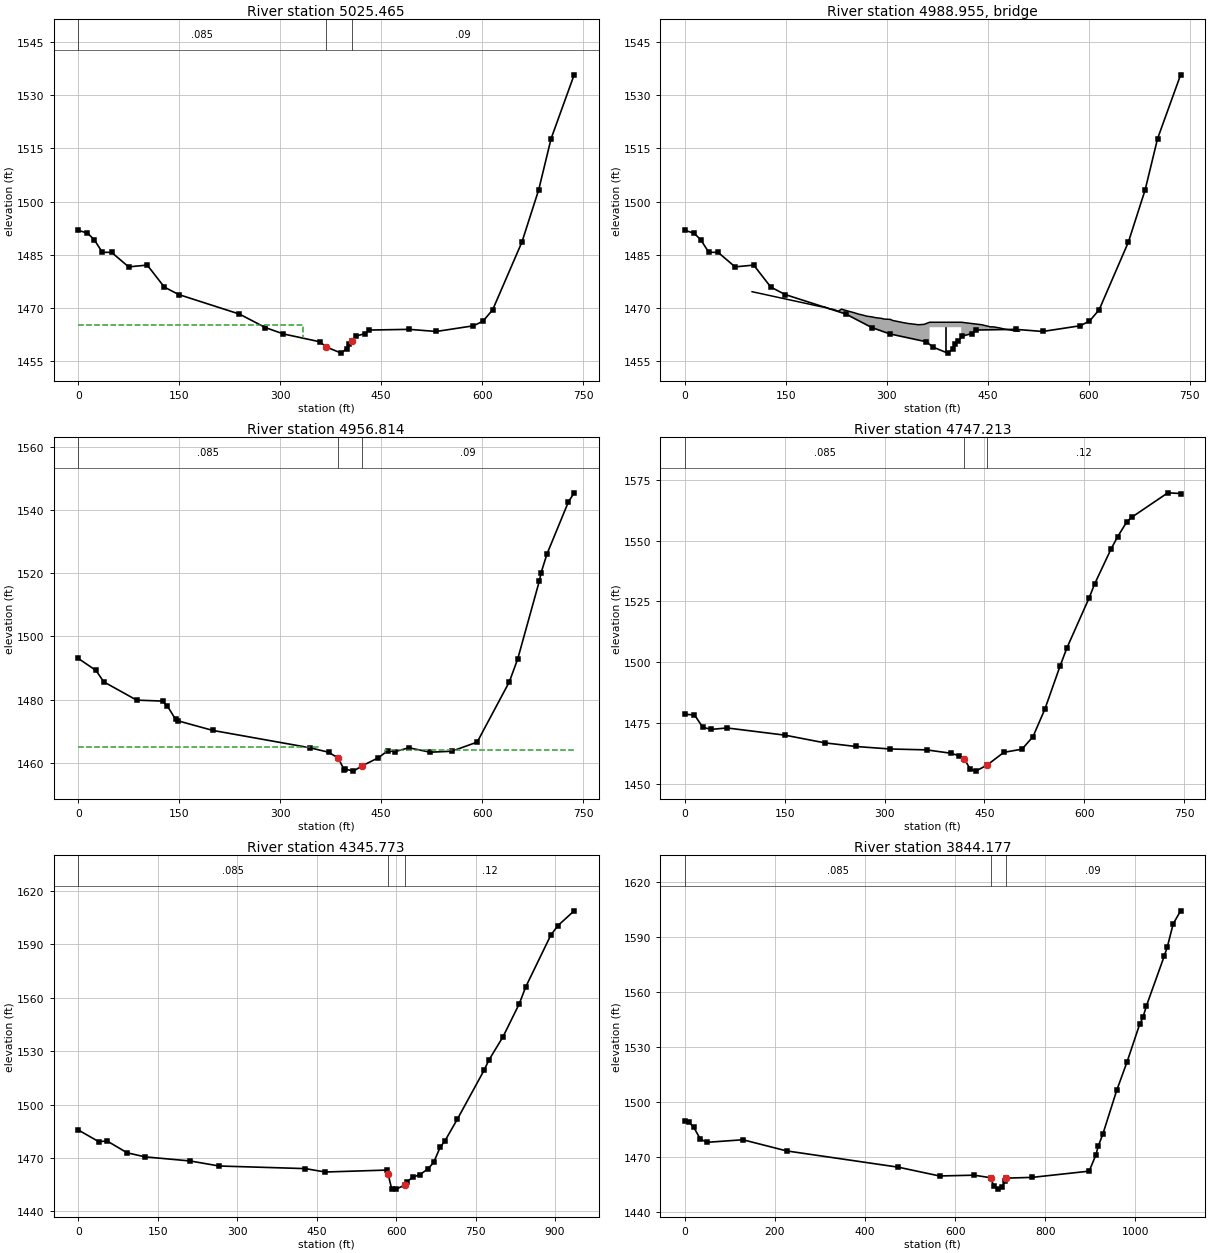
Type RM Length L Ch R = 1 ,5025.465,69.7,68.65,67.33
BEGIN DESCRIPTION:
Upstream xs of Bridge 37111-0242
END DESCRIPTION:
XS GIS Cut Line= 3
  1053979.867984   683429.301214  1054393.630943   683232.042148
  1054663.057986   683162.279759
#Sta/Elev= 30
       0  1491.9    13.5  1491.1    23.5  1489.3    35.6  1485.7    49.4  1485.7
    74.7  1481.6   102.4  1482.1   127.8  1475.9   149.2  1473.8   239.4  1468.3
   277.9  1464.5   304.8  1462.7   358.8  1460.5  368.711458.999   390.7  1457.3
   398.7  1458.6   402.1    1460     406  1460.6   412.5  1462.1   426.2  1462.8
   432.1  1463.8   491.4    1464   531.8  1463.4   587.1    1465   601.2  1466.3
   615.6  1469.5   659.1  1488.6     684  1503.3   702.4  1517.7   736.7  1535.7
#Mann= 3 , 0 , 0
       0    .085       0  368.71    .049       0     406     .09       0
#XS Ineff= 2 , 0
       0   333.2  1465.3               0
Permanent Ineff=
       F       F
Bank Sta=368.71,406
Exp/Cntr=0.5,0.3

Type RM Length L Ch R = 3 ,4988.955,,,
BEGIN DESCRIPTION:
Bridge : 37111-0242 (Gravel Rd.)
END DESCRIPTION:
Bridge Culvert--1,0,-1,-1, 0
Deck Dist Width WeirC Skew NumUp NumDn MinLoCord MaxHiCord MaxSubmerge Is_Ogee
30.5,12,2.6,0, 38, 38, , , 0.95, 0, 0,0,,
     100     202   207.5   214.9   221.1     228   232.9   237.9   245.4   251.4
     258   264.8   270.6   278.3   283.2   291.8     296   305.6   308.8   319.2
   321.5   333.2   334.7   346.7   355.6   363.7   363.7   410.7   410.7   441.2
   453.9   458.6   467.5   476.9     481   492.7   494.4   497.3
  1474.6  1470.4  1470.3  1469.8  1469.6  1469.1  1469.7  1469.4    1469  1468.7
  1468.3    1468  1467.7  1467.5  1467.3  1467.1  1466.9  1466.8  1466.5  1466.1
    1466  1465.6  1465.6  1465.3  1465.4    1466    1466    1466    1466  1465.3
  1464.7  1464.7  1464.4    1464  1463.9  1463.5  1463.5  1463.5
                                                                                
                                                                                
                                                  1464.6  1464.6
                                                                
   105.3   207.3     212     220   225.5   232.9   239.1     246   250.9   255.9
   263.4   269.4     276   282.8   288.6   296.3   301.3   309.8     314   323.6
   326.8   337.2   339.6   351.2   352.7   364.7   373.6   378.1   381.7   381.7
   428.7   428.7   459.2   471.9   476.6   485.5   494.9     499
  1474.6  1471.8  1471.4  1470.4  1470.3  1469.8  1469.6  1469.1  1469.7  1469.4
    1469  1468.7  1468.3    1468  1467.7  1467.5  1467.3  1467.1  1466.9  1466.8
  1466.5  1466.1    1466  1465.6  1465.6  1465.3  1465.4  1465.4    1466    1466
    1466    1466  1465.3  1464.7  1464.7  1464.4    1464  1463.9
                                                                                
                                                                                
                                                                          1464.6
  1464.6
Pier Skew, UpSta & Num, DnSta & Num=  ,386.9, 2 ,405.6, 2 , 0 , 0 , 0 ,,
       1       1
  1456.5  1465.1
       1       1
  1456.5  1465.1
BR Coef=-1 , 1 , 0 ,, 0 ,,,0.8,0,2,0,
WSPro=,,,, 1 ,,,, 0 ,,,, 0 ,,,,-1 ,-1 ,-1 , 0 , 0 , 0 , 0 , 0
BC Design=,, 0 ,, 0 ,,,,,,

Type RM Length L Ch R = 1 ,4956.814,221.31,209.6,197.58
BEGIN DESCRIPTION:
Down stream xs of Bridge 37111-0242
END DESCRIPTION:
XS GIS Cut Line= 3
  1054017.271198   683479.602108  1054431.034157   683282.343042
    1054700.4612   683212.580653
#Sta/Elev= 30
       0    1493    26.3  1489.2    37.7  1485.6    86.7  1479.8   125.2  1479.5
   132.4  1477.9   144.5  1473.7   148.7  1473.2   199.8  1470.2   344.2  1464.7
   371.7  1463.3  386.411461.396   395.3  1457.5   395.7    1458   408.7  1457.3
  421.871458.998   445.5  1461.5   459.4  1463.7   470.9  1463.5   491.1  1464.7
   522.8  1463.3   554.9  1463.6   592.6  1466.5   640.4  1485.6   652.9  1492.9
   684.9  1517.5   687.6  1520.2   696.3  1526.1   728.1  1542.6   736.7  1545.5
#Mann= 3 , 0 , 0
       0    .085       0  386.41    .049       0  421.87     .09       0
#XS Ineff= 2 , 0
       0   355.5    1465  455.05       0    1464
Permanent Ineff=
       F       F
Bank Sta=386.41,421.87
Exp/Cntr=0.5,0.3

Type RM Length L Ch R = 1 ,4747.213,393.62,401.44,405.07
XS GIS Cut Line= 3
  1054264.922151   683716.190971  1054591.404238    683360.36219
  1054815.172861   683224.633686
#Sta/Elev= 30
       0 1478.48   14.54 1478.25   26.92 1473.16   39.64 1472.28   63.48 1472.87
  150.32 1469.91  210.18 1466.74  256.96 1465.24  308.63 1464.21  363.15 1463.85
  399.11 1462.48  411.27  1461.5  420.05 1460.05  428.51 1455.95  436.89  1455.1
  453.88 1457.57  479.12 1462.83  506.48 1464.14  522.96 1469.31  540.71 1480.59
   563.6 1498.37   573.9 1505.85  606.93 1526.22  615.69 1532.27   639.8 1546.34
  649.87 1551.52  663.85 1557.75  671.33 1559.63  725.42 1569.66  744.63 1569.38
#Mann= 3 , 0 , 0
       0    .085       0  420.05    .049       0  453.88     .12       0
Bank Sta=420.05,453.88
Exp/Cntr=0.3,0.1

Type RM Length L Ch R = 1 ,4345.773,515.02,501.6,489.58
XS GIS Cut Line= 3
  1054313.045152   684011.358033  1054814.892115    683681.71344
  1055075.655744   683470.150515
#Sta/Elev= 30
       0 1485.75   38.32 1479.25   54.43 1479.57    92.2 1472.94  126.38 1470.66
  210.98 1468.37  265.89 1465.54  428.67 1464.07  466.36 1462.16  583.19 1463.26
  584.83 1461.04  591.62 1452.73  600.18 1452.55  616.79 1454.86  620.34  1456.7
  631.71 1459.24  645.11 1460.72   660.1  1463.9  670.92 1467.53  683.05 1475.99
  692.09 1479.57  715.65 1491.83  766.38 1519.44  774.93 1524.89  801.94 1538.14
  832.69 1556.71  844.74  1566.1  892.16 1595.21  905.66 1600.57  936.22 1608.85
#Mann= 3 , 0 , 0
       0    .085       0  584.83    .049       0  616.79     .12       0
Bank Sta=584.83,616.79
Exp/Cntr=0.3,0.1

Type RM Length L Ch R = 1 ,3844.177,725.03,724.09,704.14
XS GIS Cut Line= 3
  1054611.201316   684497.952796  1055083.527871   684114.187463
  1055334.451352   683691.061573
#Sta/Elev= 30
       0 1489.62    8.56 1489.03   19.52 1486.24   34.37 1479.71   48.79 1477.88
  129.05 1479.28  225.96  1473.2  473.63 1464.33  565.42 1459.52  642.22 1459.95
  679.01 1458.55  685.83 1453.85  695.57 1452.34  703.68 1453.39  710.88 1456.55
  712.74 1458.34   770.9 1458.75  897.52 1462.15  912.27  1470.9  917.69 1475.79
  927.62 1482.18   958.8 1506.34   981.6 1521.78 1009.52 1542.27 1016.89 1546.08
 1024.67 1552.41 1064.08 1579.46 1070.91 1584.47 1084.07 1597.16 1100.51 1604.23
#Mann= 3 , 0 , 0
       0    .085       0  679.01    .049       0  712.74     .09       0
Bank Sta=679.01,712.74
Exp/Cntr=0.3,0.1

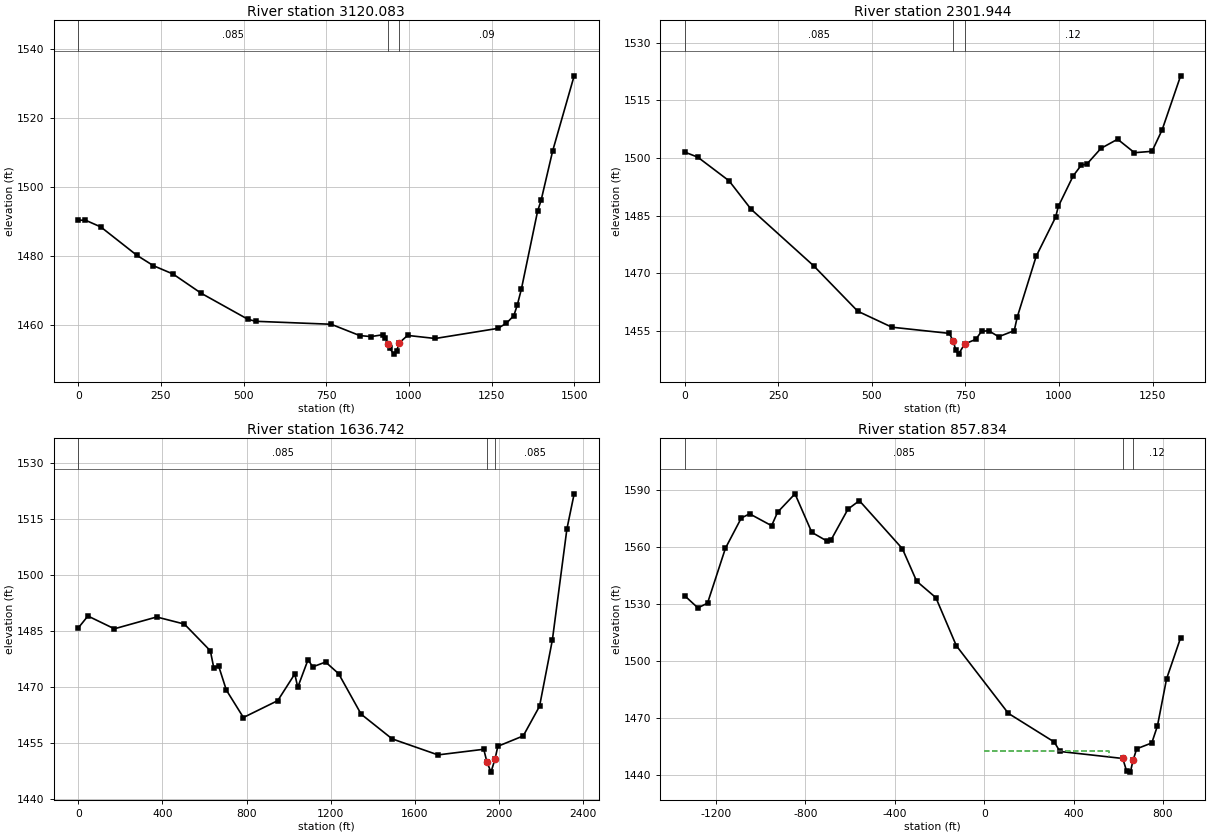
Type RM Length L Ch R = 1 ,3120.083,817.75,818.14,791
XS GIS Cut Line= 2
  1055354.131611   685215.298766  1055969.140167   683847.519767
#Sta/Elev= 30
       0 1490.41   21.41 1490.42   67.92 1488.46  176.95 1480.23  227.28  1477.2
  286.52 1474.79  371.41 1469.22   512.6 1461.67  536.11 1461.07  764.75 1460.21
  851.04 1456.93  885.03 1456.63   920.8 1457.16  928.84 1456.25  937.38 1454.44
  941.31 1453.23  954.67 1451.54  962.86 1452.56  971.22 1454.86  995.86 1456.97
 1079.46 1456.08 1268.22    1459 1294.18 1460.46 1317.13 1462.69 1327.76 1465.82
 1340.03  1470.4 1389.21 1493.08 1399.86 1496.24 1434.74 1510.55 1499.68 1532.32
#Mann= 3 , 0 , 0
       0    .085       0  937.38    .049       0  971.22     .09       0
Bank Sta=937.38,971.22
Exp/Cntr=0.3,0.1

Type RM Length L Ch R = 1 ,2301.944,684.83,665.2,635.21
XS GIS Cut Line= 2
  1056234.823871   685396.849269  1056520.187834   684102.871307
#Sta/Elev= 30
       0 1501.51   34.71  1500.2  118.41 1494.03  177.14 1486.64   344.4 1471.92
  462.23  1460.1  553.39 1455.94  706.81 1454.33  717.74 1452.27   724.3  1449.9
  731.56 1448.93  747.84 1451.57  777.52 1452.77  793.37  1454.9  812.53    1455
  838.75 1453.46   880.4 1455.03  888.28 1458.52  939.14 1474.42  990.82 1484.54
  998.25 1487.38 1037.89 1495.32 1059.39  1498.1 1074.68 1498.41 1112.17 1502.49
 1156.67 1504.87 1201.73 1501.36 1248.62 1501.72 1275.55 1507.28 1325.07 1521.37
#Mann= 3 , 0 , 0
       0    .085       0  717.74    .049       0  747.84     .12       0
Bank Sta=717.74,747.84
Exp/Cntr=0.3,0.1

Type RM Length L Ch R = 1 ,1636.742,773.82,778.91,772.68
XS GIS Cut Line= 3
  1057217.438193   686499.619265  1057061.395352   684678.519307
  1056820.311981   684206.192752
#Sta/Elev= 30
       0 1485.86   45.61 1489.04  171.43 1485.61  372.52 1488.78  504.27 1486.88
  627.81 1479.71  644.38 1475.09  666.97 1475.68   703.9 1469.17  785.05 1461.82
  948.43 1466.35 1029.42  1473.5 1043.53 1469.92 1092.57 1477.34 1114.52  1475.4
    1176 1476.69 1237.94 1473.57    1345 1462.71  1492.3 1456.09 1710.42 1451.79
 1928.16  1453.3 1942.91 1449.96 1962.52 1447.17 1981.72 1450.69  1995.1  1454.1
 2115.84 1456.88 2193.48 1464.84 2254.42  1482.6 2323.69 1512.43 2358.07 1521.81
#Mann= 3 , 0 , 0
       0    .085       0 1942.91    .049       0 1981.72    .085       0
Bank Sta=1942.91,1981.72
Exp/Cntr=0.5,0.3

Type RM Length L Ch R = 1 ,857.834 ,135.59,160.06,166.79
BEGIN DESCRIPTION:
Upstream xs of Bridge 37111-0247
END DESCRIPTION:
XS GIS Cut Line= 5
  1058198.509166   685864.421386  1057534.620149   684257.105238
   1057490.83798   684121.004799   1057392.43661   683884.841503
  1057289.945909   683869.502504
#Sta/Elev= 30
   -1340 1534.29-1281.53 1527.95-1238.37 1530.41-1157.99 1559.44-1087.23 1575.32
-1049.96 1577.56  -951.5 1571.28 -924.78  1578.4 -846.81  1588.1 -771.74 1567.79
 -704.41 1563.23 -685.93  1563.7 -609.67 1580.03 -558.89 1584.49 -366.38 1559.18
 -302.34 1541.99 -216.44 1533.34 -124.88 1507.99     108  1472.3   313.2  1457.2
   338.9  1452.2     620  1448.5     637  1441.9     654  1441.3     666  1447.5
   682.2  1453.6   749.9  1456.7   775.2  1465.7     816  1490.5   878.9  1512.2
#Mann= 3 , 0 , 0
   -1340    .085       0     620    .049       0     666     .12       0
#XS Ineff= 2 , 0
       0  558.96 1452.62               0
Permanent Ineff=
       F       F
Bank Sta=620,666
Exp/Cntr=0.5,0.3