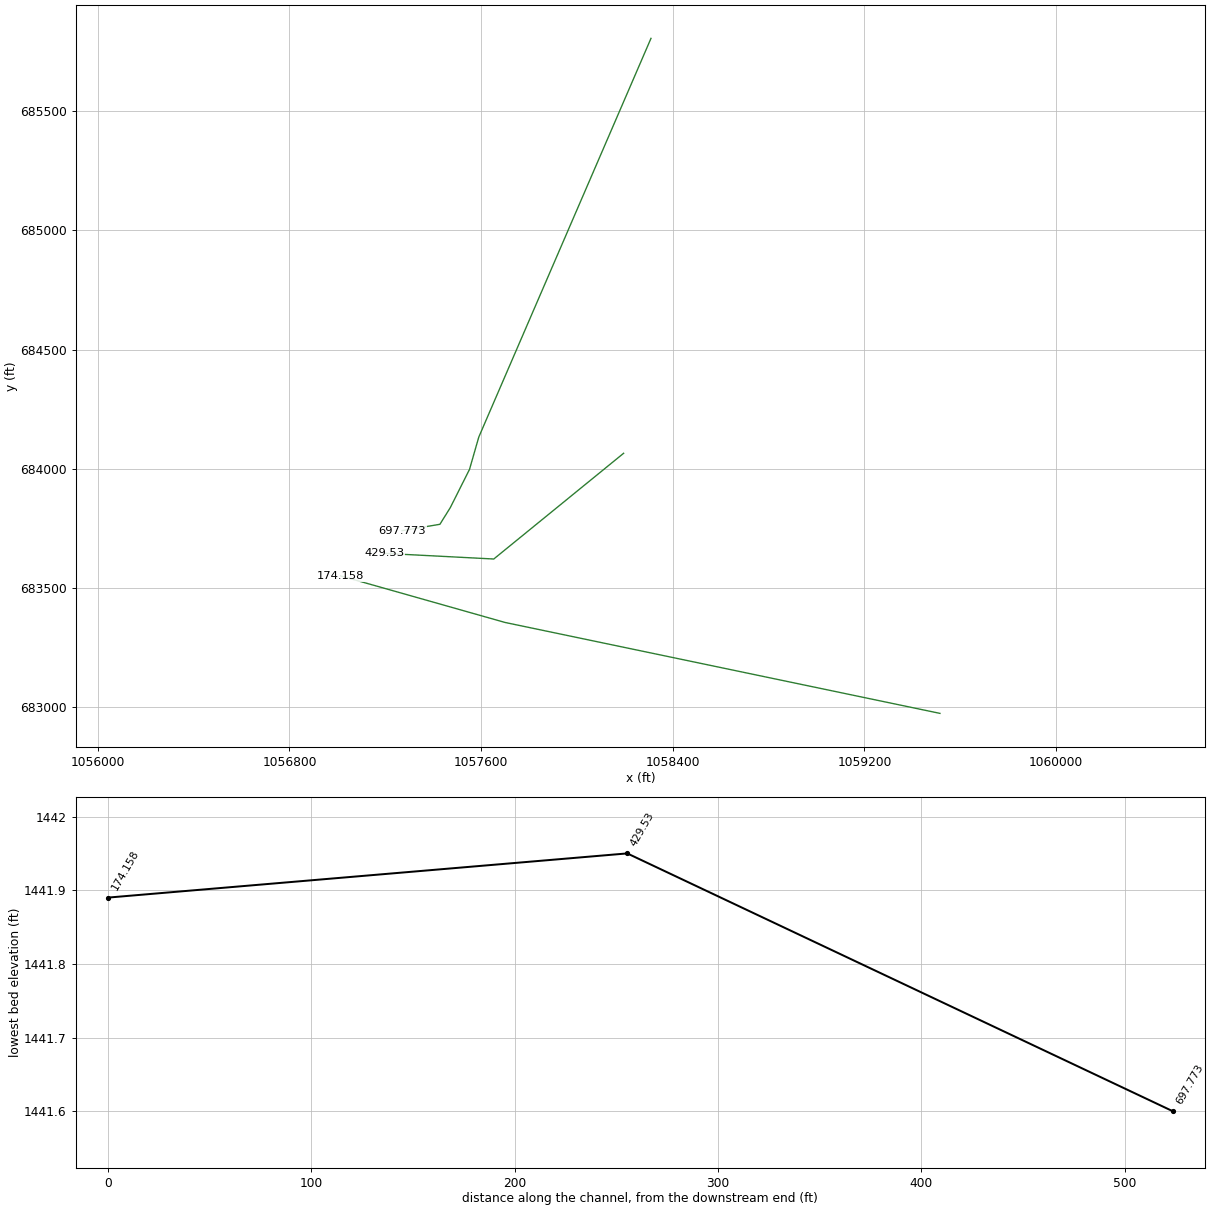
HEC-RAS study Lt_Crooked_Cr.prj: Lt_Crooked_Cr

--- Lt_Crooked_Cr.g02 (geometry) --- (continued)

Type RM Length L Ch R = 3 ,807.977 ,,,
BEGIN DESCRIPTION:
Bridge : 37111-0247 (SR-1103)
END DESCRIPTION:
Bridge Culvert--1,0,-1,-1, 0
Deck Dist Width WeirC Skew NumUp NumDn MinLoCord MaxHiCord MaxSubmerge Is_Ogee
39.9,20,2.6,0, 98, 66, , , 0.95, 0, 0,0,,
    -400       0    10.8    20.5    24.1    29.4      35    48.6    59.9    68.1
    71.9    74.9    83.7    96.4   106.3   109.8   114.9   117.1   126.4   130.9
   133.5   138.3     147   153.4   160.3   163.4   168.2   179.5   188.9   193.8
   205.1   213.2   213.3   213.4   229.3   230.2     238   251.8   253.4     256
   262.3   268.7   276.4   280.8     284   292.2   298.5     303   306.8   313.9
     320   324.3   336.5   343.5   346.2   358.3   359.2   359.2   367.2   367.5
   376.4   380.6   383.2   389.4   392.9   401.9   502.8   584.4     599     599
     679     679   770.2   775.2   778.1   785.8   788.5     796   796.1   797.3
   812.9   814.2   822.4   824.8   832.8   843.6   844.8   855.8   862.2   873.5
   877.4   882.2   887.5   896.5   897.5   898.1     905   905.9
    1510  1508.7  1507.3  1505.8  1505.6  1504.7  1503.7  1500.1  1497.8  1495.8
  1494.8  1494.1  1492.8  1489.9  1488.6  1487.8  1485.9  1485.5  1484.5    1484
  1483.6  1483.1  1482.3    1482  1481.2  1481.2  1481.3  1481.9  1481.3  1481.1
  1481.3  1481.4  1481.4  1481.4  1479.1    1479  1477.7  1475.4  1475.1  1474.8
  1473.8  1473.3  1472.1  1470.7  1470.1  1468.9  1467.8  1466.8  1465.8  1464.9
    1464  1462.6  1458.6    1456  1455.3  1452.9  1452.8  1452.7  1452.5  1452.5
  1452.5  1452.5  1452.6  1452.6  1452.5  1452.3  1453.2  1453.3  1453.5  1453.5
  1453.5  1453.5  1456.3  1456.6  1456.6  1456.1  1455.8  1455.6  1455.6  1456.3
  1465.2  1466.2  1471.8    1473  1478.2  1481.9  1482.3  1486.4  1488.3  1491.3
  1492.5  1494.1  1495.8  1498.4  1498.7  1498.9  1500.7  1500.9
                                                                                
                                                                                
                                                                                
                                                                                
                                                                                
                                                                                
                                                                          1451.5
  1451.5
                                                                                
                                                                
    23.6    34.4    44.1    47.6      53    58.6    72.2    83.5    91.7    95.5
    98.5   107.3     120   129.9   133.4   138.5   140.7     150   154.5   157.1
   161.9   170.6     177   183.9     187   191.8   203.1   212.5   217.3   228.7
   236.8   236.9   236.9   252.9   253.8   261.6   275.4     277   279.6   285.9
   292.3     300   304.4   307.6   315.8   322.1   326.6   330.4   337.5   343.6
   347.9   360.1   367.1   369.8   381.9   382.7   382.8   390.8   391.1   491.6
     618     618     698     698     748   812.1
  1508.7  1507.3  1505.8  1505.6  1504.7  1503.7  1500.1  1497.8  1495.8  1494.8
  1494.1  1492.8  1489.9  1488.6  1487.8  1485.9  1485.5  1484.5    1484  1483.6
  1483.1  1482.3    1482  1481.2  1481.2  1481.3  1481.9  1481.3  1481.1  1481.3
  1481.4  1481.4  1481.4  1479.1    1479  1477.7  1475.4  1475.1  1474.8  1473.8
  1473.3  1472.1  1470.7  1470.1  1468.9  1467.8  1466.8  1465.8  1464.9    1464
  1462.6  1458.6    1456  1455.3  1452.9  1452.8  1452.7  1452.5  1452.5  1452.7
  1453.8  1453.8  1453.8  1453.8  1454.7  1455.8
                                                                                
                                                                                
                                                                                
                                                                                
                                                                                
                                                                                
          1451.8  1451.8
Pier Skew, UpSta & Num, DnSta & Num=  ,629, 2 ,648, 2 , 0 , 0 , 0 ,,
       1       1
  1442.6    1452
       1       1
  1442.9  1452.3
Pier Skew, UpSta & Num, DnSta & Num=  ,659, 2 ,678, 2 , 0 , 0 , 0 ,,
       1       1
  1441.1    1452
       1       1
  1441.4  1452.3
BR Coef=-1 , 1 , 0 ,, 0 ,,,0.8,-1,2,0,
WSPro=,,,, 1 ,,,, 0 ,,,, 0 ,,,,-1 ,-1 ,-1 , 0 , 0 , 0 , 0 , 0
BC Design=,, 0 ,, 0 ,,,,,,

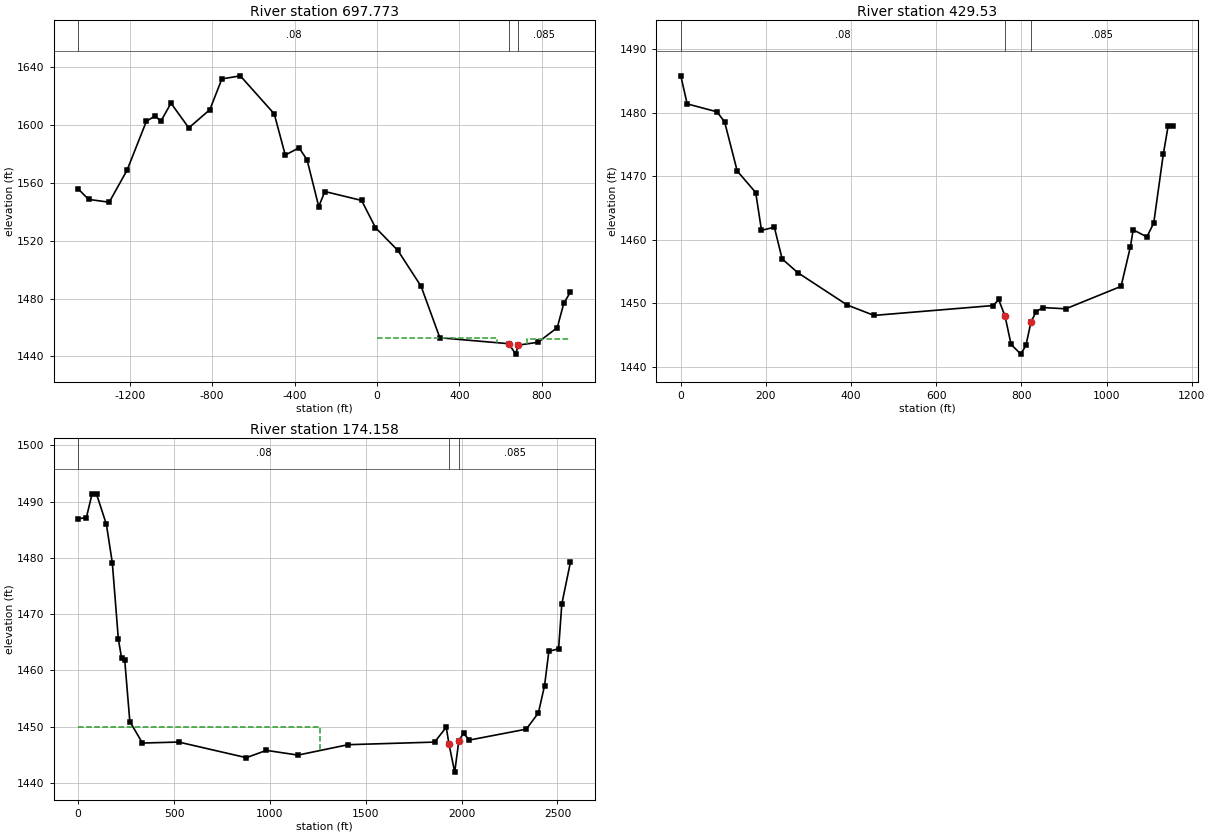
Type RM Length L Ch R = 1 ,697.773 ,332.68,268.24,198.43
BEGIN DESCRIPTION:
Down stream xs of Bridge 37111-0247
END DESCRIPTION:
XS GIS Cut Line= 6
  1058309.199965   685805.820352  1057590.338064   684133.556877
  1057551.577799   683997.895908  1057471.634707   683838.009764
  1057428.029399   683767.756759  1057270.565776   683741.109061
#Sta/Elev= 30
-1449.88 1555.73-1399.26 1548.46-1299.25 1546.52-1212.42  1568.7-1119.01 1602.38
-1076.07 1606.16-1048.82 1602.36 -999.61 1614.93 -913.09 1597.85 -811.04 1610.44
 -752.64 1631.66 -663.31 1633.81 -498.63 1607.54 -445.07  1579.1 -378.27 1584.09
 -339.46 1575.85  -282.7 1543.55 -253.06 1553.91  -74.88 1547.75   -7.52 1528.99
   101.2  1513.2     214  1488.4   304.8  1452.9     639  1448.8     673  1441.6
     685  1447.8   781.8  1449.8   874.4  1459.9   906.6  1476.9   938.7  1484.5
#Mann= 3 , 0 , 0
-1449.88     .08       0     639    .049       0     685    .085       0
#XS Ineff= 2 , 0
       0  583.71 1452.51     730       0    1452
Permanent Ineff=
       F       F
Bank Sta=639,685
Exp/Cntr=0.5,0.3

Type RM Length L Ch R = 1 ,429.53  ,260.39,255.37,241.98
XS GIS Cut Line= 3
  1058194.922143   684065.581572  1057652.864579   683622.173891
  1057197.459712   683645.831283
#Sta/Elev= 30
       0  1485.8   14.99 1481.38   85.04 1480.13  102.93 1478.54  132.53  1470.8
  175.98 1467.41  189.54 1461.45  219.76 1461.95  237.99 1456.96  274.44  1454.8
  390.83 1449.69  453.79 1448.05  734.26 1449.61  746.49 1450.56  761.48 1447.95
  775.79 1443.47  798.74 1441.95  810.75 1443.37  822.55 1447.03  834.83 1448.66
  850.63 1449.29  904.13 1449.09 1034.03 1452.63 1055.94 1458.85 1062.43 1461.54
  1094.7 1460.42 1110.79 1462.61 1133.29 1473.47 1144.81 1477.97 1156.33 1477.84
#Mann= 3 , 0 , 0
       0     .08       0  761.48    .049       0  822.55    .085       0
Bank Sta=761.48,822.55
Exp/Cntr=0.3,0.1

Type RM Length L Ch R = 1 ,174.158 ,248.36,174.16,138.95
XS GIS Cut Line= 3
  1059515.381428   682974.767364  1057700.179361   683356.028192
  1057014.114862   683551.201679
#Sta/Elev= 30
       0 1486.95   42.94 1487.15    72.5 1491.38   96.35 1491.29  147.13 1485.96
  178.11 1479.14  209.68 1465.53  226.36 1462.22  242.91 1461.82  269.47 1450.89
  335.31 1447.06  524.21 1447.24  877.27 1444.46  981.67 1445.76 1146.55 1444.92
 1408.36 1446.77 1859.21 1447.23 1920.07 1449.87    1934 1446.92 1964.11 1441.89
 1985.87  1447.5 2010.01 1448.78 2040.42 1447.59  2337.3 1449.53 2400.56 1452.41
 2432.87 1457.29 2455.14 1463.36 2506.07 1463.83 2522.84  1471.8  2568.1 1479.28
#Mann= 3 , 0 , 0
       0     .08       0    1934    .049       0 1985.87    .085       0
#XS Ineff= 2 , 0
         1261.79  1449.9
Permanent Ineff=
       F       F
Bank Sta=1934,1985.87
Exp/Cntr=0.3,0.1

Chan Stop Cuts=-1
Use User Specified Reach Order=0
User Specified Reach Order=Lt_Crooked_Cr   ,Main