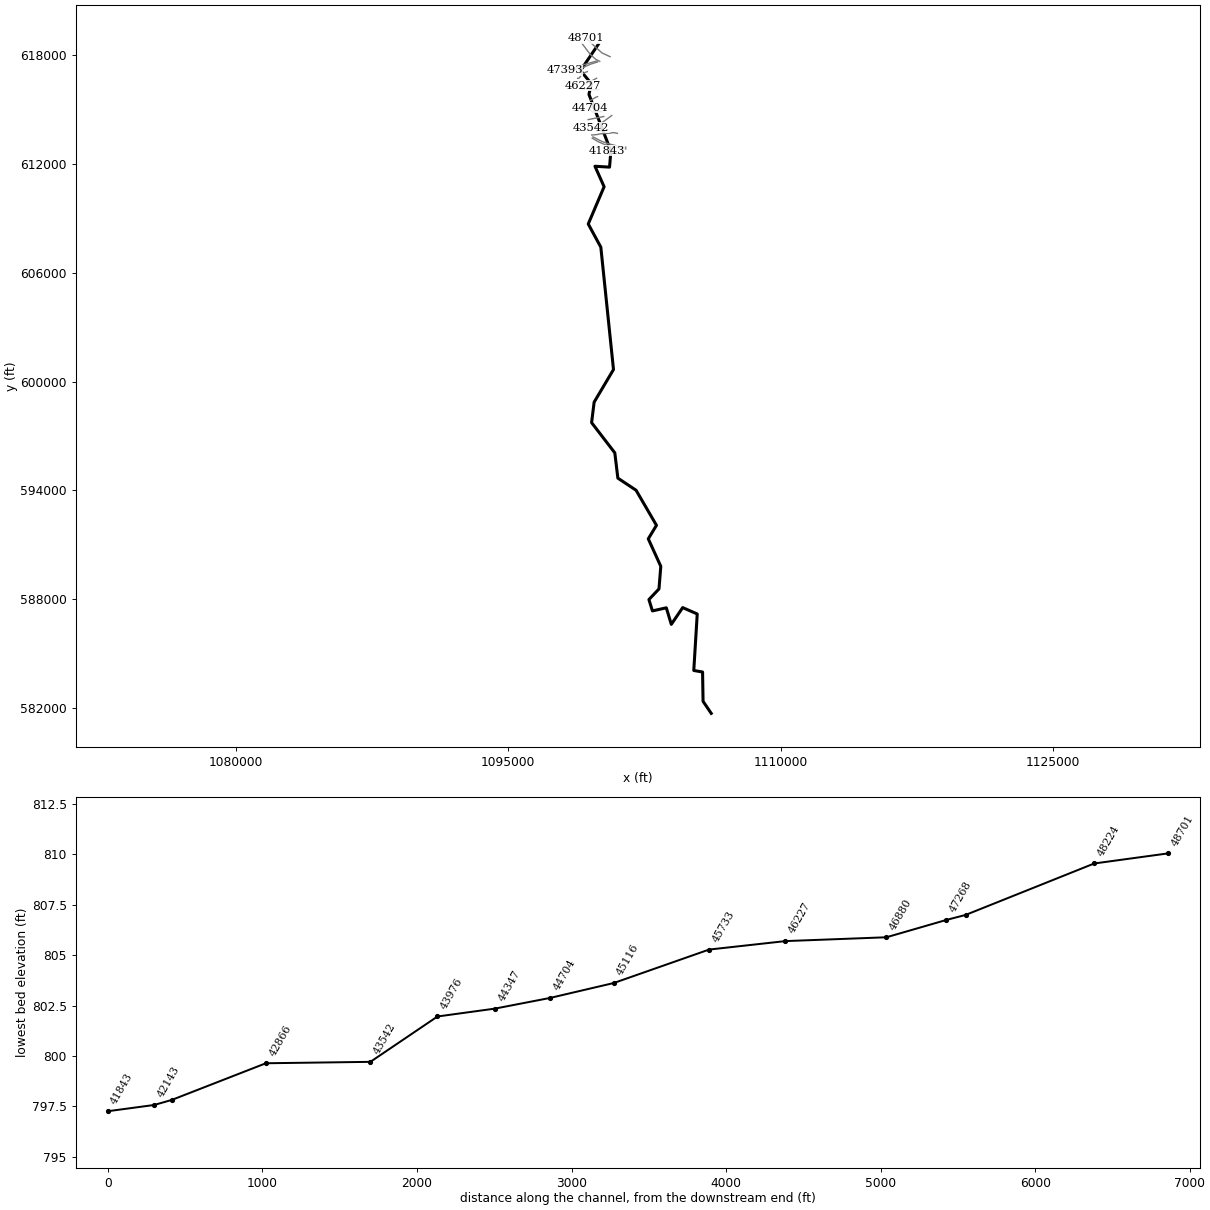
--- lds_mountain_crk.prj (project) ---

Proj Title=Mountain Creek Limited Detail Study
Current Plan=p02
Default Exp/Contr=0.3,0.1
English Units
Geom File=g01
Flow File=f02
Flow File=f01
Flow File=f03
Plan File=p02
Y Axis Title=Elevation
X Axis Title(PF)=Main Channel Distance
X Axis Title(XS)=Station
BEGIN DESCRIPTION:
Mountain Creek
END DESCRIPTION:
DSS Export Rating Curves= 0
DSS Export Rating Curve Sorted= 0
DSS Export Volume Flow Curves= 0
DXF OffsetX= 0
DXF OffsetY= 0
DXF ScaleX= 1
DXF ScaleY= 10

--- lds_mountain_crk.p02 (plan) ---

Plan Title=Floodway Run
Program Version=3.13
Short Identifier=Floodway
Geom File=g01
Flow File=f02
Subcritical Flow
K Sum by GR= 0
Std Step Tol= 0.01
Critical Tol= 0.01
Num of Std Step Trials= 20
Max Error Tol= 0.3
Flow Tol Ratio= 0.001
Split Flow NTrial= 30
Split Flow Tol= 0.02
Split Flow Ratio= 0.02
Log Output Level= 0
Friction Slope Method= 0
Unsteady Friction Slope Method= 2
Unsteady Bridges Friction Slope Method= 1
Parabolic Critical Depth
Global Vel Dist= 0 , 0 , 0
Global Log Level= 0
CheckData=True
Encroach Param=-1 ,10,10, 2
Encroach River=Mountain Creek
Encroach Reach=Reach-1
Encroach Node=48701
       4      .7
Encroach Node=48224
       1    4820  5168.2
Encroach Node=47393
       1    4910  5132.5
Encroach Node=47268
       1  4898.5  5101.5
Encroach Node=46880
       1 4882.96 5215.16
Encroach Node=46227
       1 4922.05  5034.1
Encroach Node=45733
       1  4939.9 5066.35
Encroach Node=45116
       1 4941.61 5058.24
Encroach Node=44704
       1    4964 5077.09
Encroach Node=44347
       1 4940.99 5032.63
Encroach Node=43976
       1 4848.36 5241.08
Encroach Node=43542
       1 4798.88 5381.61
Encroach Node=42866
       1    4967 5376.66
Encroach Node=42257
       1    4899    5101
Encroach Node=42143
       1    4897    5103
Encroach Node=41843
       1    4847 5090.31
Encroach Node=41526
       1 4938.71 5075.29
Encroach Node=40952
       1  4965.4 5067.64
Encroach Node=40442
       1  4968.8 5061.45
Encroach Node=39960
       1  4880.4  5039.4
Encroach Node=39514
       1 4944.49  5036.2
Encroach Node=39020
       1 4962.75 5061.99
Encroach Node=38511
       1 4652.18  5046.6
Encroach Node=37930
       1 4453.48 5091.22
Encroach Node=37306
       1 4899.95 5422.81
Encroach Node=36732
       1 4957.09 5085.21
Encroach Node=36079
       1  4965.3  5229.1
Encroach Node=35638
       1  4962.4 5044.73
Encroach Node=35187
       1 4921.87  5045.3
Encroach Node=34668
       1  4957.7 5074.24
Encroach Node=34378
       1    4930  5031.3
Encroach Node=34302
       1 4945.96    5030
Encroach Node=34255
       1  4946.8  5037.5
Encroach Node=33984
       1 4958.66 5066.25
Encroach Node=33678
       1  4963.2 5124.15
Encroach Node=33182
       1 4952.79  5037.4
Encroach Node=32731
       1 4959.87    5044
Encroach Node=32271
       1 4892.72    5032
Encroach Node=31834
       1  4964.7 5158.69
Encroach Node=31484
       1  4963.2 5322.27
Encroach Node=30724
       1 4937.63 5170.71
Encroach Node=30317
       1 4821.99 5194.61
Encroach Node=29963
       1 4764.66 5300.85
Encroach Node=29425
       1 4860.24 5454.57
Encroach Node=28452
       1 4926.37 5238.89
Encroach Node=27958
       1 4956.26 5675.16
Encroach Node=27349
       1  4931.5  5211.3
Encroach Node=27127
       1  4941.4 5079.67
Encroach Node=27054
       1    4965 5040.68
Encroach Node=26697
       1 4858.94  5032.9
Encroach Node=26005
       1 4671.48  5039.3
Encroach Node=25410
       1  4823.3  5039.8
Encroach Node=24503
       1 4884.58 5606.19
Encroach Node=23687
       1 4253.69 5334.54
Encroach Node=23050
       1 4477.99 5250.42
Encroach Node=22484
       1 4802.41 5269.86
Encroach Node=21896
       1 4754.53 5075.38
Encroach Node=21103
       1 4656.82 5143.61
Encroach Node=20794
       1 4596.73  5061.1
Encroach Node=20082
       1 4526.11 5078.92
Encroach Node=19383
       1 4321.16  5037.8
Encroach Node=18673
       1  4374.2 5077.53
Encroach Node=18267
       1    4583 5285.38
Encroach Node=18266
       1    4650 5287.27
Encroach Node=17740
       1    4914    5086
Encroach Node=17631
       1    4903    5097
Encroach Node=17322
       1 4532.22 5211.64
Encroach Node=16843
       1 4619.64 5292.32
Encroach Node=16395
       1 4565.74 5140.88
Encroach Node=15510
       1  4952.6  5038.4
Encroach Node=14986
       1  4937.5 5223.66
Encroach Node=14292
       1 4661.35 5261.19
Encroach Node=13722
       1 4453.91  5042.2
Encroach Node=13316
       1 4446.77 5103.39
Encroach Node=12918
       1 4574.03  5052.4
Encroach Node=12325
       1 4952.91 5204.73
Encroach Node=11671
       1 4909.73 5176.46
Encroach Node=11170
       1  4959.4 5198.14
Encroach Node=10762
       1  4827.9 5200.02
Encroach Node=10334
       1 4940.95  5041.7
Encroach Node=9959
       1  4958.9 5078.73
Encroach Node=9687
       1  4961.4 5096.18
Encroach Node=9164
       1  4957.5  5053.6
Encroach Node=8825
       1    4924  5032.1
Encroach Node=8355
       1  4960.3  5046.7
Encroach Node=7932
       1  4959.3 5069.12
Encroach Node=7447
       1 4959.31    5039
Encroach Node=6847
       1 4775.56 5214.49
Encroach Node=6358
       1 4754.65    5040
Encroach Node=6173
       1  4935.6  5049.3
Encroach Node=5483
       1 4822.89 5383.71
Encroach Node=5079
       1  4951.1  5701.8
Encroach Node=4620
       1  4953.6 5842.33
Encroach Node=4110
       1  4946.9  5695.2
Encroach Node=3654
       1    4961 5556.09
Encroach Node=3149
       1    4853 5304.45
Encroach Node=2573
       1 4885.24  5110.5
Encroach Node=2354
       1  4948.2 5051.74
Encroach Node=2297
       1 4945.37  5055.2
Encroach Node=2005
       1 4950.36  5039.8
Encroach Node=1533
       1 4937.27 5043.51
Encroach Node=1132
       1 4912.34 5131.93
Encroach Node=686
       1 4859.48 5430.11
BEGIN DESCRIPTION:
Floodway Run
END DESCRIPTION:
Computation Interval=1HOUR
Output Interval=1HOUR
Run HTab= 0
Run UNet= 0
Run PostProcess= 0
UNET Theta= 1
UNET Theta Warmup= 1
UNET ZTol= 0.02
UNET ZSATol= 0.05
UNET MxIter= 20
UNET MaxInSteps= 0
UNET DtIC= 0
UNET DtMin= 0
UNET MaxCRTS= 20
UNET WFStab= 2
UNET SFStab= 1
UNET WFX= 1
UNET SFX= 1
UNET DSS MLevel= 4
UNET DZMax Abort= 100
UNET Convert EG Bridges=-1
UNET Use Existing IB Tables=-1
UNET Froude Reduction=False
UNET Froude Limit= 1
UNET Froude Power= 10
Instantaneous Interval=1HOUR
Write IC File= 0
Echo Input=False
Echo Output=False
Write Detailed= 0
Detailed Automatic Start=False, 10

--- lds_mountain_crk.p01 (plan) ---

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Plan Title=Multiple Run
Short Identifier=Multiple
Geom File=g01
Flow File=f01
Friction Slope Method= 1
Encroach Param=-1 ,0,0, 0
Multiple Run

--- lds_mountain_crk.f02 (steady flow) ---

Flow Title=Floodway
Program Version=3.13
Number of Profiles= 2
Profile Names=100-year,100-FW
River Rch & RM=Mountain Creek,Reach-1         ,48701
    3680    3680
River Rch & RM=Mountain Creek,Reach-1         ,47393
    6790    6790
River Rch & RM=Mountain Creek,Reach-1         ,46227
    6797    6797
River Rch & RM=Mountain Creek,Reach-1         ,42866
    6879    6879
River Rch & RM=Mountain Creek,Reach-1         ,41843
    6891    6891
River Rch & RM=Mountain Creek,Reach-1         ,40442
    6907    6907
River Rch & RM=Mountain Creek,Reach-1         ,37930
    6913    6913
River Rch & RM=Mountain Creek,Reach-1         ,36732
    6930    6930
River Rch & RM=Mountain Creek,Reach-1         ,33984
    7030    7030
River Rch & RM=Mountain Creek,Reach-1         ,28452
    7130    7130
River Rch & RM=Mountain Creek,Reach-1         ,26005
    8240    8240
River Rch & RM=Mountain Creek,Reach-1         ,25410
    8820    8820
River Rch & RM=Mountain Creek,Reach-1         ,23687
    8910    8910
River Rch & RM=Mountain Creek,Reach-1         ,21103
    9040    9040
River Rch & RM=Mountain Creek,Reach-1         ,16843
    9250    9250
River Rch & RM=Mountain Creek,Reach-1         ,15510
    9370    9370
River Rch & RM=Mountain Creek,Reach-1         ,10334
    9490    9490
River Rch & RM=Mountain Creek,Reach-1         ,2005
    9510    9510
Boundary for River Rch & Prof#=Mountain Creek,Reach-1         , 1
Up Type= 0
Dn Type= 3
Dn Slope=0.0002
Boundary for River Rch & Prof#=Mountain Creek,Reach-1         , 2
Up Type= 0
Dn Type= 3
Dn Slope=0.0002
DSS Import GetInterval= 0
DSS Import GetPeak= 0
DSS Import FillOption= 0

--- lds_mountain_crk.f01 (steady flow) ---

Flow Title=Multiple
Number of Profiles=4
Profile Names=10-year,50-year,100-year,500-year
River Rch & RM= Mountain Creek,Reach-1,48688
    1547    2620    3168    4709
River Rch & RM= Mountain Creek,Reach-1,47393
    2421    4025    4834    7090
River Rch & RM= Mountain Creek,Reach-1,45808
    2453    4076    4895    7176
River Rch & RM= Mountain Creek,Reach-1,42866
    2812    4646    5567    8128
River Rch & RM= Mountain Creek,Reach-1,41843
    2866    4732    5669    8272
River Rch & RM= Mountain Creek,Reach-1,40442
    2933    4838    5794    8448
River Rch & RM= Mountain Creek,Reach-1,37907
    2958    4878    5841    8515
River Rch & RM= Mountain Creek,Reach-1,36732
    3026    4986    5968    8694
River Rch & RM= Mountain Creek,Reach-1,33984
    3075    5062    6058    8821
River Rch & RM= Mountain Creek,Reach-1,28452
    3123    5139    6148    8948
River Rch & RM= Mountain Creek,Reach-1,26005
    3635    5944    7096   10280
River Rch & RM= Mountain Creek,Reach-1,25329
    3908    6371    7597   10982
River Rch & RM= Mountain Creek,Reach-1,23687
    3951    6439    7677   11094
River Rch & RM= Mountain Creek,Reach-1,21103
    4013    6535    7789   11250
River Rch & RM= Mountain Creek,Reach-1,16676
    4111    6688    7969   11501
River Rch & RM= Mountain Creek,Reach-1,15510
    4170    6780    8077   11652
River Rch & RM= Mountain Creek,Reach-1,10654
    4226    6868    8180   11796
River Rch & RM= Mountain Creek,Reach-1,1796
    4240    6889    8205   11831
Boundary for River Rch & Prof#=Mountain Creek,Reach-1,1
Up Type=0
Dn Type=3
Dn Slope=0.005
Boundary for River Rch & Prof#=Mountain Creek,Reach-1,2
Up Type=0
Dn Type=3
Dn Slope=0.005
Boundary for River Rch & Prof#=Mountain Creek,Reach-1,3
Up Type=0
Dn Type=3
Dn Slope=0.005
Boundary for River Rch & Prof#=Mountain Creek,Reach-1,4
Up Type=0
Dn Type=3
Dn Slope=0.005

--- lds_mountain_crk.f03 (steady flow) ---

Flow Title=100-year Single
Number of Profiles=1
Profile Names=100-year
River Rch & RM= Mountain Creek,Reach-1,48688
    3168
River Rch & RM= Mountain Creek,Reach-1,47393
    4834
River Rch & RM= Mountain Creek,Reach-1,45808
    4895
River Rch & RM= Mountain Creek,Reach-1,42866
    5567
River Rch & RM= Mountain Creek,Reach-1,41843
    5669
River Rch & RM= Mountain Creek,Reach-1,40442
    5794
River Rch & RM= Mountain Creek,Reach-1,37907
    5841
River Rch & RM= Mountain Creek,Reach-1,36732
    5968
River Rch & RM= Mountain Creek,Reach-1,33984
    6058
River Rch & RM= Mountain Creek,Reach-1,28452
    6148
River Rch & RM= Mountain Creek,Reach-1,26005
    7096
River Rch & RM= Mountain Creek,Reach-1,25329
    7597
River Rch & RM= Mountain Creek,Reach-1,23687
    7677
River Rch & RM= Mountain Creek,Reach-1,21103
    7789
River Rch & RM= Mountain Creek,Reach-1,16676
    7969
River Rch & RM= Mountain Creek,Reach-1,15510
    8077
River Rch & RM= Mountain Creek,Reach-1,10654
    8180
River Rch & RM= Mountain Creek,Reach-1,1796
    8205
Boundary for River Rch & Prof#=Mountain Creek,Reach-1,1
Up Type=0
Dn Type=3
Dn Slope=0.005

--- lds_mountain_crk.g01 (geometry) ---

Geom Title=Existing Conditions
Program Version=3.13

River Reach=Mountain Creek  ,Reach-1
Reach XY= 30
      1099951.87       618598.41      1098979.63       617162.56
      1099576.63       616438.69      1099444.25       615848.31
      1100653.88       612718.88       1100578.5       611835.56
        1099776.       611884.56      1100279.63       610754.94
      1099406.25       608699.69      1100098.88       607421.56
      1100796.88       600671.56      1099730.25       598872.25
      1099590.63       597742.25      1100869.13       596076.31
      1101036.75        594680.5      1102040.75       594012.38
      1103164.13       592078.38      1102712.75       591332.63
      1103402.25       589816.19      1103302.13       588568.88
      1102748.25       587982.75      1102941.25       587356.13
      1103706.25       587528.06      1103980.63       586614.69
      1104608.25         587540.      1105409.25       587187.44
      1105219.13       584070.88      1105703.13       583986.25
      1105730.63       582368.31       1106180.5       581704.44

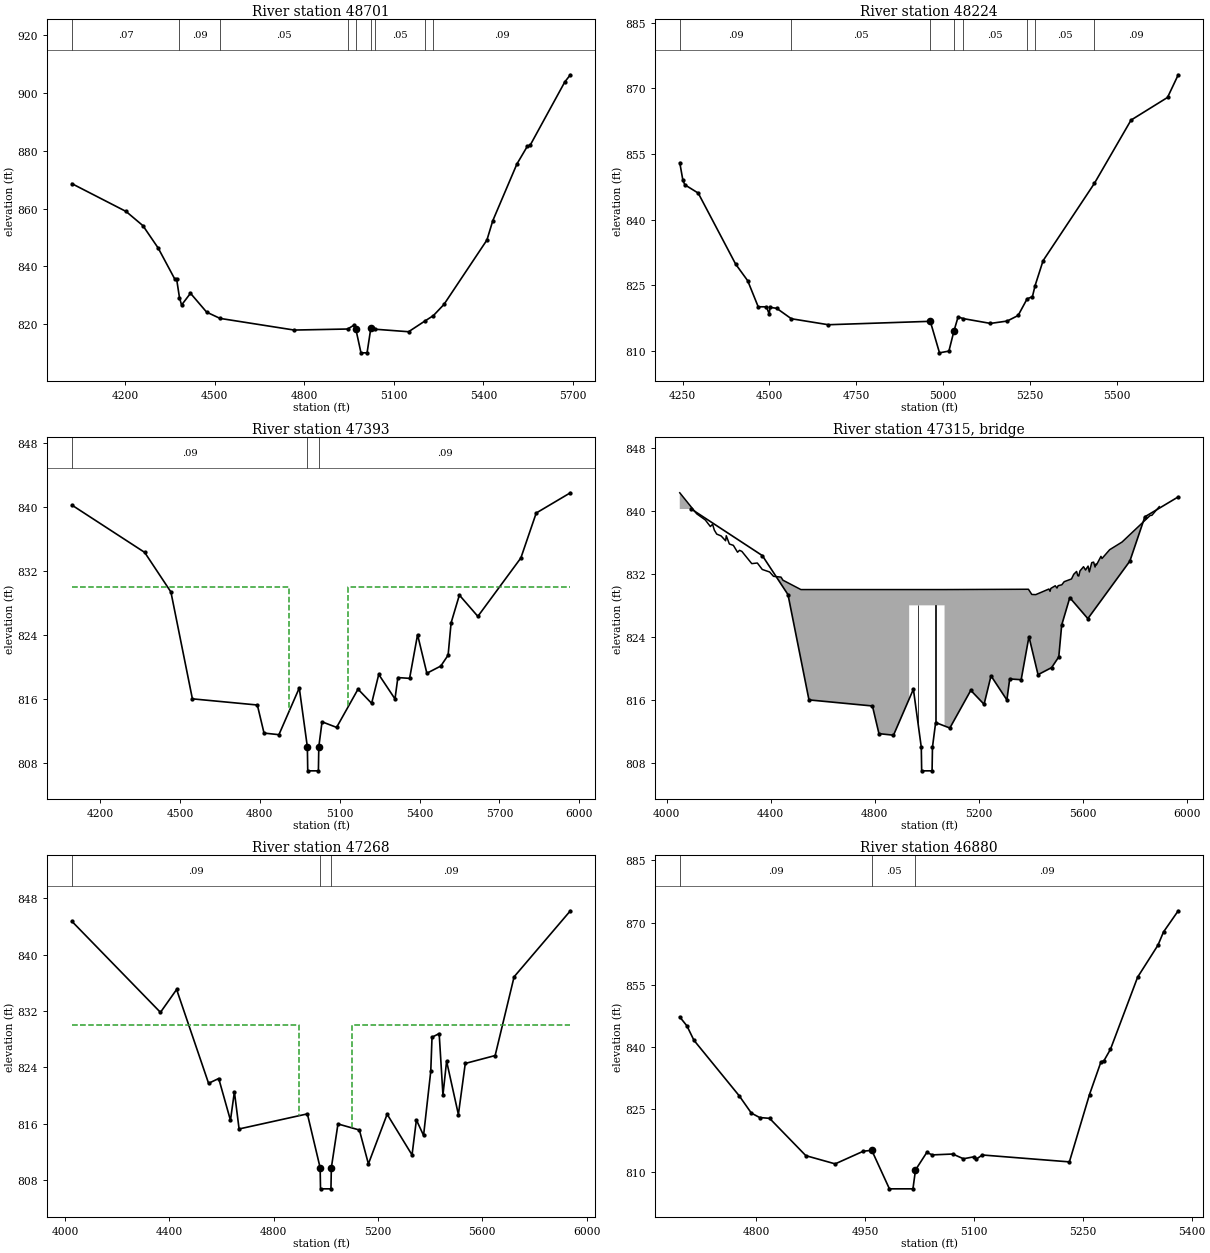
Type RM Length L Ch R = 1 ,48701   ,477,477,477
BEGIN DESCRIPTION:
Mtn. Crk 500
END DESCRIPTION:
XS GIS Cut Line= 4
      1100610.82       617927.04      1100160.38       618135.58
      1099626.52       618623.55      1099305.37       618940.53
#Sta/Elev= 30
  4020.8  868.64  4202.4  859.01  4258.9  854.09    4310  846.34  4364.8  835.76
  4371.9  835.54  4381.4  829.16  4388.4  826.61  4418.3  830.68  4472.4  824.15
  4517.2  821.98  4765.8  817.94  4945.1   818.3  4966.9  819.68  4972.4  818.32
  4989.8  810.05  5010.2  810.05  5023.1  818.81  5037.1  818.23  5149.4  817.36
  5203.6  821.04  5232.4  822.94  5267.9  826.81  5411.9  849.11  5431.6  855.82
  5512.4  875.44    5547  881.52  5557.1  881.99  5673.2  903.91  5691.7  906.35
#Mann= 9 ,-1 , 0
  4020.8     .07       0  4381.4     .09       0  4517.2     .05       0
  4945.1     .09       0  4972.4     .05       0  5023.1     .09       0
  5037.1     .05       0  5203.6     .03       0  5232.4     .09       0
Bank Sta=4972.4,5023.1
Exp/Cntr=0.3,0.1

Type RM Length L Ch R = 1 ,48224   ,831,831,831
BEGIN DESCRIPTION:
Mtn_Crk-89.0
END DESCRIPTION:
XS GIS Cut Line= 4
      1100039.42       617668.45      1099799.07       617799.01
      1099518.08       618052.16      1099046.78       618677.77
#Sta/Elev= 30
  4242.1  852.98  4251.2  848.92  4256.9  847.92  4295.2  846.04    4403  829.81
  4437.7  826.02  4467.9  820.07  4491.6  820.06  4499.7  818.39  4501.9  819.95
  4521.3  819.71  4563.3  817.34  4669.8  815.97  4963.3  816.75  4989.8  809.55
  5016.9  809.95  5031.3  814.51  5043.3  817.75  5058.8  817.36  5136.5  816.27
  5184.7  816.81  5216.1  818.08  5242.1  821.89  5257.3  822.38  5265.1  824.93
    5288   830.6  5435.5  848.23  5541.2  862.71  5646.2  867.88  5677.1  873.06
#Mann= 8 ,-1 , 0
  4242.1     .09       0  4563.3     .05       0  4963.3     .05       0
  5031.3     .09       0  5058.8     .05       0  5242.1     .03       0
  5265.1     .05       0  5435.5     .09       0
Bank Sta=4963.3,5031.3
Exp/Cntr=0.5,0.3

Type RM Length L Ch R = 1 ,47393   ,125,125,125
BEGIN DESCRIPTION:
SR-1355-US
END DESCRIPTION:
XS GIS Cut Line= 6
      1099898.26       617699.32      1099438.01       617568.71
      1099073.12       617452.61      1098905.19       617382.12
      1098384.81       617220.41      1098104.93       617189.31
#Sta/Elev= 30
  4094.3  840.22  4367.5  834.31  4466.1  829.36  4546.8     816  4790.7  815.23
  4815.8  811.72  4871.7  811.52  4948.2  817.36  4978.5     810    4980     807
    5020     807  5021.5     810  5033.7  813.13  5088.3  812.43  5168.8  817.21
  5219.9  815.44  5246.6  819.05  5307.6  815.99  5318.4  818.66  5362.5  818.56
  5392.4  824.02  5427.3   819.2  5479.6   820.1  5507.1  821.46  5518.3   825.5
  5549.4  828.97  5618.8  826.31  5780.3  833.61    5838  839.23  5966.3  841.76
#Mann= 3 ,-1 , 0
  4094.3     .09       0  4978.5     .05       0  5021.5     .09       0
#XS Ineff= 2 , 0
       0    4910     830  5132.5       0     830
Permanent Ineff=
       F       F
Bank Sta=4978.5,5021.5
Exp/Cntr=0.5,0.3

Type RM Length L Ch R = 3 ,47315   ,,,
BEGIN DESCRIPTION:
SR-1355
Structure ID: SR-1355
Approximate Survey Structure
END DESCRIPTION:
Bridge Culvert--1,0,-1,-1, 0
Deck Dist Width WeirC Skew NumUp NumDn MinLoCord MaxHiCord MaxSubmerge Is_Ogee
64.5,27,3,0, 60, 60, , , , 0, 1,1,,
  4050.1    4115  4148.3  4167.7  4176.3  4182.9  4192.1  4209.2  4226.3  4228.9
  4240.8  4256.1  4272.2  4279.9  4288.9  4326.9  4348.3  4367.3  4395.5  4410.5
  4439.3  4446.7  4515.7    4932    4932    5068    5068  5390.4  5403.4  5418.6
  5469.1  5473.5  5476.6  5493.5  5500.2  5504.6  5518.8  5527.8    5556  5564.6
  5575.5  5580.1  5583.9  5588.6  5602.2  5609.9  5619.7  5624.5  5633.8  5641.1
  5646.5  5649.3  5651.9  5669.2  5673.1  5702.7  5750.2  5858.6  5864.9  5893.4
  842.28  839.62  838.83     838  838.28  837.55  837.04   836.8  836.19  836.83
  835.78  835.61  834.74  834.98  834.84  833.29  833.37  832.55  832.23  831.68
  831.58  831.19     830     830     830     830     830  830.04  829.38  829.36
  830.07  829.78  830.15  830.48  830.19  830.49  830.61     831  831.35  831.94
   832.3  831.76  831.72  832.37   832.9  832.48  832.98  832.24  833.42  833.48
  832.86  833.23  833.13  834.21  833.94  835.06  836.03  839.41  839.42  840.52
     787     787     787     787     787     787     787     787     787     787
     787     787     787     787     787     787     787     787     787     787
     787     787     787     787     828     828     787     787     787     787
     787     787     787     787     787     787     787     787     787     787
     787     787     787     787     787     787     787     787     787     787
     787     787     787     787     787     787     787     787     787     787
  4050.1    4115  4148.3  4167.7  4176.3  4182.9  4192.1  4209.2  4226.3  4228.9
  4240.8  4256.1  4272.2  4279.9  4288.9  4326.9  4348.3  4367.3  4395.5  4410.5
  4439.3  4446.7  4515.7    4932    4932    5068    5068  5390.4  5403.4  5418.6
  5469.1  5473.5  5476.6  5493.5  5500.2  5504.6  5518.8  5527.8    5556  5564.6
  5575.5  5580.1  5583.9  5588.6  5602.2  5609.9  5619.7  5624.5  5633.8  5641.1
  5646.5  5649.3  5651.9  5669.2  5673.1  5702.7  5750.2  5858.6  5864.9  5893.4
  842.28  839.62  838.83     838  838.28  837.55  837.04   836.8  836.19  836.83
  835.78  835.61  834.74  834.98  834.84  833.29  833.37  832.55  832.23  831.68
  831.58  831.19     830     830     830     830     830  830.04  829.38  829.36
  830.07  829.78  830.15  830.48  830.19  830.49  830.61     831  831.35  831.94
   832.3  831.76  831.72  832.37   832.9  832.48  832.98  832.24  833.42  833.48
  832.86  833.23  833.13  834.21  833.94  835.06  836.03  839.41  839.42  840.52
     787     787     787     787     787     787     787     787     787     787
     787     787     787     787     787     787     787     787     787     787
     787     787     787     787     828     828     787     787     787     787
     787     787     787     787     787     787     787     787     787     787
     787     787     787     787     787     787     787     787     787     787
     787     787     787     787     787     787     787     787     787     787
Pier Skew, UpSta & Num, DnSta & Num=  ,4966, 2 ,4966, 2 , 0 , 0 , 0 ,0,0
       2       2
  813.92     828
       2       2
  813.46     828
Pier Skew, UpSta & Num, DnSta & Num=  ,5034, 2 ,5034, 2 , 0 , 0 , 0 ,0,0
       2       2
   813.1     828
       2       2
  812.42     828
Abutment Skew #Up #Dn= , 2 , 2
    4932  4933.5
     828   816.9
    4932  4933.5
     828  816.16
Abutment Skew #Up #Dn= , 2 , 2
  5066.5    5068
  813.16     828
  5066.5    5068
   813.1     828
BR Coef= 1 , 1 , 0 ,1.25, 0 ,,,0.8,0,2,0,
WSPro=,,,, 1 ,,,, 0 ,,,, 0 ,,,,-1 ,-1 ,-1 , 0 , 0 , 0 , 0 , 0
BC Design=,, 0 ,, 0 ,,,,,,
BC HTab HWMax=841.8

Type RM Length L Ch R = 1 ,47268   ,388,388,388
BEGIN DESCRIPTION:
SR-1355-DS
END DESCRIPTION:
XS GIS Cut Line= 6
      1099921.07       617635.05      1099535.45       617516.88
      1099205.81       617369.68      1098923.85       617288.82
      1098239.69       617120.89      1098094.56       617131.26
#Sta/Elev= 30
  4026.8  844.72  4366.3   831.8  4428.3  835.05  4550.8  821.73  4589.7  822.41
  4634.7  816.48  4649.8  820.52  4667.8  815.25  4929.6  817.39  4978.5  809.75
    4980  806.75    5020  806.75  5021.5  809.75  5046.9  815.96    5129   815.1
  5163.6  810.29  5235.4  817.34  5330.9  811.56  5347.6  816.53  5375.1  814.33
  5402.7  823.45  5407.5  828.27  5434.9  828.79  5449.4  820.08  5463.4  824.87
  5508.6   817.3    5535  824.55  5649.5  825.67  5722.2  836.85    5938  846.22
#Mann= 3 ,-1 , 0
  4026.8     .09       0  4978.5     .05       0  5021.5     .09       0
#XS Ineff= 2 , 0
       0  4898.5     830  5101.5       0     830
Permanent Ineff=
       F       F
Bank Sta=4978.5,5021.5
Exp/Cntr=0.5,0.3

Type RM Length L Ch R = 1 ,46880   ,653,653,653
BEGIN DESCRIPTION:
Mtn_Crk-88.0
END DESCRIPTION:
XS GIS Cut Line= 6
      1099357.15       617106.38      1099238.98       617060.77
      1099054.46       616971.62      1098940.44       616789.18
      1098878.24        616733.2      1098822.26        616733.2
#Sta/Elev= 30
  4695.1  847.27    4705  845.11  4714.6  841.66  4776.9   828.3  4793.7  824.12
  4805.1  823.06  4818.8  822.86  4868.7  813.88  4909.1   811.9  4947.9  814.95
  4959.5  815.16  4983.8  805.89  5016.2  805.89  5019.7  810.44  5035.2  814.64
  5042.9  814.06    5071  814.27  5085.7  813.13  5099.8  813.59  5103.6  813.08
  5111.8  814.04  5231.6  812.38  5259.3   828.6    5275  836.42  5279.3  836.77
  5288.2   839.5  5325.6  856.86  5353.6  864.56  5361.2  867.73  5381.5  872.83
#Mann= 3 ,-1 , 0
  4695.1     .09       0  4959.5     .05       0  5019.7     .09       0
Bank Sta=4959.5,5019.7
Exp/Cntr=0.3,0.1

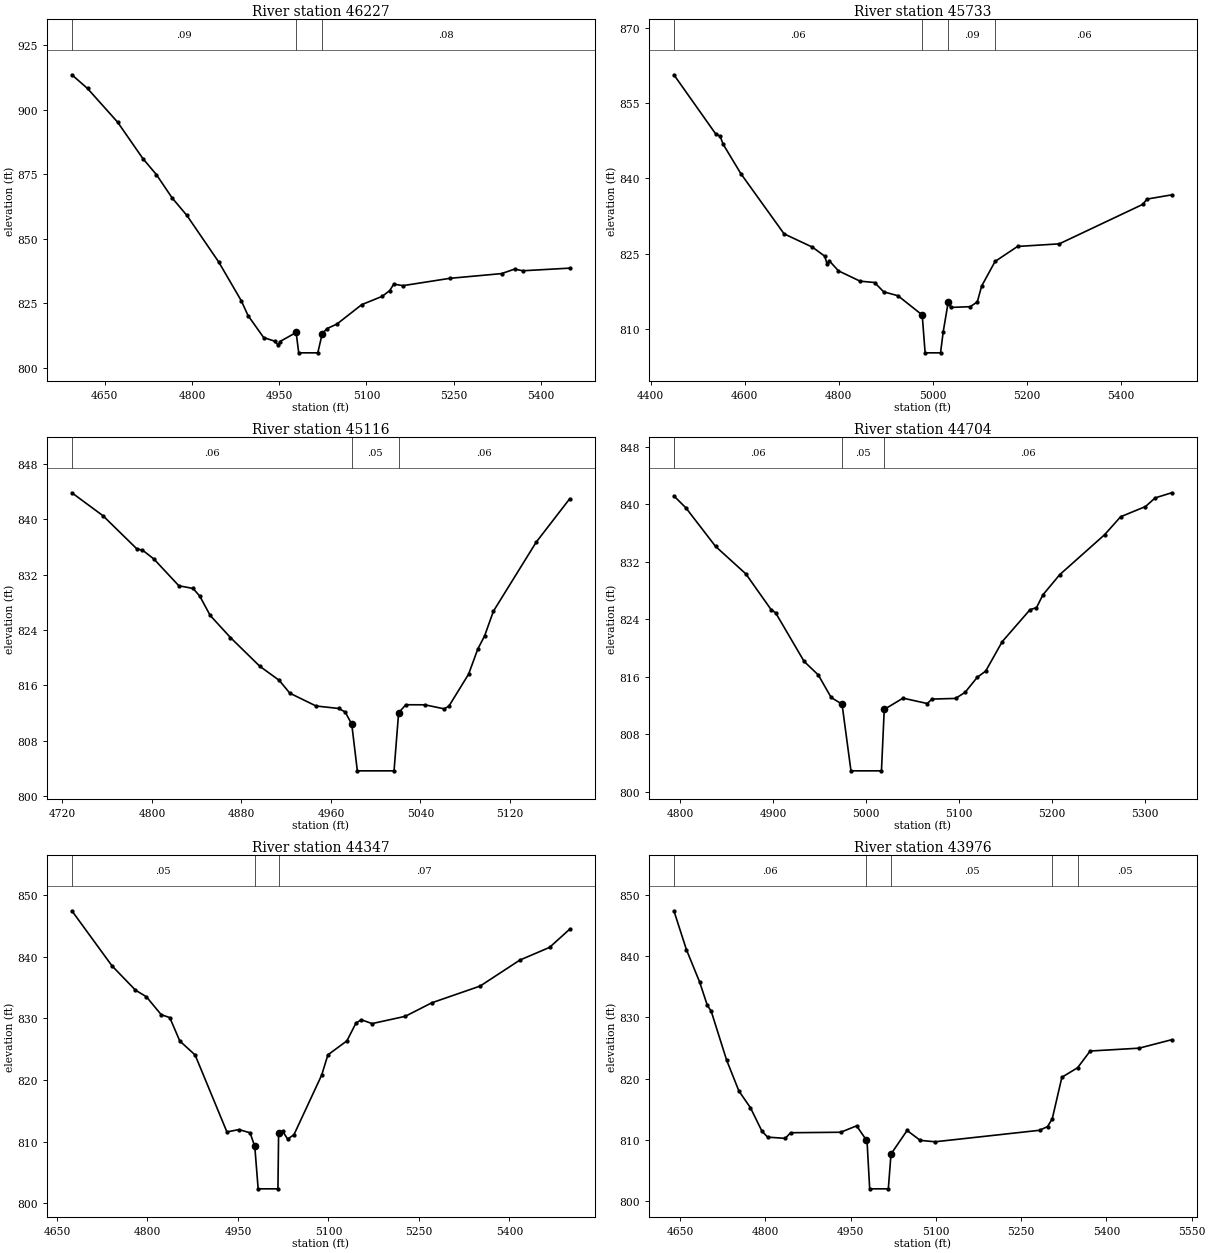
Type RM Length L Ch R = 1 ,46227   ,494,494,494
BEGIN DESCRIPTION:
Mtn_Crk-87.0
END DESCRIPTION:
XS GIS Cut Line= 2
      1099866.39       616739.15      1099110.55       616337.31
#Sta/Elev= 30
  4593.5  913.54  4620.4  908.23  4672.1  895.19  4715.8  880.99    4739  874.79
  4765.9  865.79  4791.3  858.99  4846.1  840.91  4884.9  825.88  4896.5  820.14
  4923.4  811.61  4942.4  810.22  4948.8  808.58    4951  810.04  4979.2  813.59
  4983.6   805.7  5016.4   805.7  5024.1  813.17  5032.3  815.11  5049.2  816.84
    5092  824.39  5127.4  827.63  5140.1  829.86  5147.1  832.35    5163  831.76
  5243.6   834.6  5332.5  836.43  5354.9  838.18    5369  837.53  5449.5  838.55
#Mann= 3 ,-1 , 0
  4593.5     .09       0  4979.2     .05       0  5024.1     .08       0
Bank Sta=4979.2,5024.1
Exp/Cntr=0.3,0.1

Type RM Length L Ch R = 1 ,45733   ,617,617,617
BEGIN DESCRIPTION:
mtn crk a
END DESCRIPTION:
XS GIS Cut Line= 2
      1099980.71       616089.34      1098924.26       616153.36
#Sta/Elev= 30
  4449.4  860.64  4538.1  848.89  4547.7  848.41  4553.9  846.84  4592.1  840.91
  4683.7  828.97    4744  826.32  4770.2  824.52  4774.8  823.06  4780.1  823.57
  4799.4   821.6  4845.3  819.55  4876.2  819.28  4895.4  817.43  4925.8  816.65
  4977.4  812.82  4983.6  805.28  5016.4  805.28    5022  809.44  5032.8  815.43
  5037.9  814.32  5079.5  814.47  5094.5  815.41  5103.8  818.58  5132.4  823.48
  5180.1  826.46  5268.9  826.98  5446.6  834.85  5455.3  835.89  5507.8  836.73
#Mann= 4 ,-1 , 0
  4449.4     .06       0  4977.4     .05       0  5032.8     .09       0
  5132.4     .06       0
Bank Sta=4977.4,5032.8
Exp/Cntr=0.3,0.1

Type RM Length L Ch R = 1 ,45116   ,412,412,412
BEGIN DESCRIPTION:
Mtn_Crk-86.0
END DESCRIPTION:
XS GIS Cut Line= 6
      1099921.07       615723.54      1099846.43       615702.81
      1099792.53       615669.64      1099670.21        615603.3
      1099552.04       615524.52      1099529.23       615524.52
#Sta/Elev= 30
  4728.5  843.84  4756.3  840.52  4786.8  835.69  4791.5  835.56  4801.8  834.26
  4824.1  830.39  4836.8     830  4842.8  828.89  4852.1   826.1  4870.2   822.9
  4896.4  818.75  4913.8  816.71  4923.3  814.85  4946.7     813    4967  812.64
  4972.7  812.13  4978.6  810.38  4983.6  803.62  5016.4  803.62  5020.5  812.02
  5026.9  813.18    5044  813.17  5061.1  812.59  5065.4  812.97    5083   817.6
  5091.3  821.26  5097.3  823.13  5105.2  826.71  5143.4  836.69  5173.3  842.96
#Mann= 3 ,-1 , 0
  4728.5     .06       0  4978.6     .05       0  5020.5     .06       0
Bank Sta=4978.6,5020.5
Exp/Cntr=0.3,0.1

Type RM Length L Ch R = 1 ,44704   ,357,357,357
BEGIN DESCRIPTION:
Mtn_Crk-85.0
END DESCRIPTION:
XS GIS Cut Line= 6
      1100012.29       615275.73      1099871.31       615230.12
      1099800.82       615238.41       1099709.6       615219.75
      1099574.84       615134.75      1099512.64       615120.24
#Sta/Elev= 30
  4793.1  841.15  4805.9  839.51  4837.9  834.13  4870.5   830.3  4897.7  825.32
  4902.6  824.87  4933.2  818.11  4948.5  816.22  4962.3  813.09    4974  812.16
  4983.6  802.88  5016.4  802.88  5019.4  811.43  5039.6     813  5065.7  812.25
  5070.7  812.87  5096.1  812.96  5106.4  813.81  5119.5  815.91  5128.5  816.76
  5146.3  820.86  5176.2  825.31  5183.2   825.6  5190.1  827.38  5208.2  830.19
  5256.6  835.77  5273.7  838.25  5300.4  839.67  5310.9  840.88  5328.6  841.59
#Mann= 3 ,-1 , 0
  4793.1     .06       0    4974     .05       0  5019.4     .06       0
Bank Sta=4974,5019.4
Exp/Cntr=0.3,0.1

Type RM Length L Ch R = 1 ,44347   ,371,371,371
BEGIN DESCRIPTION:
Mtn_Crk-84.0
END DESCRIPTION:
XS GIS Cut Line= 6
      1100153.27       614894.26      1099923.14       614927.43
      1099778.02       614910.84       1099709.6       614859.01
      1099639.11       614883.89      1099425.57       615070.48
#Sta/Elev= 30
  4674.8  847.45  4741.2  838.53  4780.2  834.58  4798.3  833.51  4822.8  830.61
  4837.1  830.12  4853.7  826.33  4879.1  824.06  4931.8  811.58  4951.8  811.96
  4970.2  811.44    4978  809.22  4983.6  802.35  5016.4  802.35  5017.5  811.39
  5024.2  811.69  5032.5  810.42  5042.9  811.12  5088.9   820.8  5099.2  824.08
  5130.7  826.35  5145.8  829.25  5154.7  829.77  5172.4  829.15  5227.4  830.33
  5271.3  832.52  5351.6  835.24  5417.5  839.46  5466.6  841.51  5499.9  844.45
#Mann= 3 ,-1 , 0
  4674.8     .05       0    4978     .05       0  5017.5     .07       0
Bank Sta=4978,5017.5
Exp/Cntr=0.3,0.1

Type RM Length L Ch R = 1 ,43976   ,434,434,434
BEGIN DESCRIPTION:
mtn crk b
END DESCRIPTION:
XS GIS Cut Line= 2
       1100260.1       614628.35      1099401.55       614456.64
#Sta/Elev= 30
  4639.2  847.46  4661.2  841.11  4684.6  835.77  4697.9  832.01  4704.8  831.03
    4732  823.01  4753.6  817.96  4773.9  815.23  4794.1  811.39  4804.1  810.42
  4835.1  810.22  4844.5  811.14  4932.7  811.22  4960.6  812.27  4977.6  809.97
  4978.9  809.88  4983.6  801.96  5016.4  801.96  5021.1  807.65  5049.4  811.51
  5072.6  809.89  5098.7  809.66  5282.4  811.54  5296.5  812.15  5304.8  813.43
  5321.7  820.22  5349.4  821.78  5371.4  824.51  5457.6  824.98  5514.8  826.36
#Mann= 5 ,-1 , 0
  4639.2     .06       0  4977.6     .05       0  5021.1     .05       0
  5304.8     .09       0  5349.4     .05       0
Bank Sta=4977.6,5021.1
Exp/Cntr=0.3,0.1

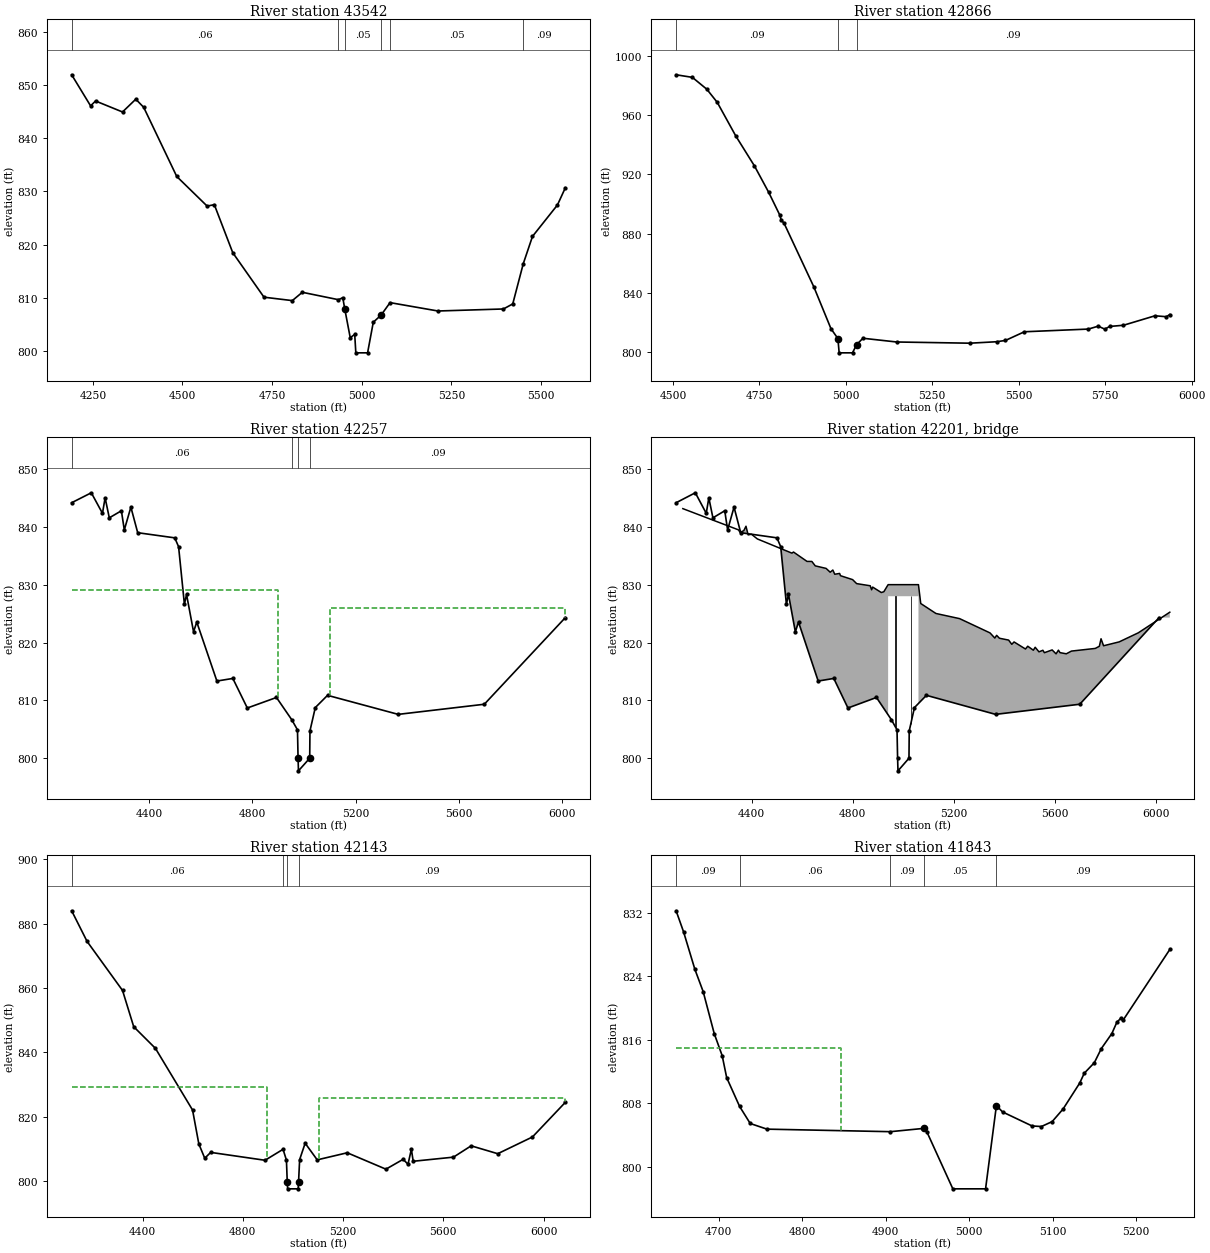
Type RM Length L Ch R = 1 ,43542   ,676,676,676
BEGIN DESCRIPTION:
Mtn_Crk-83.0
END DESCRIPTION:
XS GIS Cut Line= 6
      1100703.55       614684.51      1100178.15       614299.24
      1099948.02       614048.38      1099769.72       614017.29
      1099626.67       614015.21      1099568.62       613998.63
#Sta/Elev= 30
  4190.8  851.88  4243.6  846.05  4257.5  846.96  4332.7   844.9  4369.7   847.3
  4391.8  845.77    4484   832.8  4568.8  827.24  4588.8  827.51  4640.3  818.49
  4727.4  810.15  4806.4  809.51  4834.3  811.07  4935.2  809.68  4947.2  810.06
  4952.6  807.99    4968  802.55  4980.5  803.17  4983.6  799.71  5016.4  799.71
  5032.3  805.45  5054.2   806.8  5079.1  809.13  5212.8  807.56  5395.4  807.94
  5421.4  808.89  5450.7  816.42  5476.5  821.56  5546.1  827.45  5568.2  830.69
#Mann= 6 ,-1 , 0
  4190.8     .06       0  4935.2     .09       0  4952.6     .05       0
  5054.2     .09       0  5079.1     .05       0  5450.7     .09       0
Bank Sta=4952.6,5054.2
Exp/Cntr=0.3,0.1

Type RM Length L Ch R = 1 ,42866   ,609,609,609
BEGIN DESCRIPTION:
Mtn_Crk-81.0
END DESCRIPTION:
XS GIS Cut Line= 6
      1101007.95       613699.66      1100795.22       613742.21
      1100582.48       613706.04      1100062.79       613672.31
      1099880.45       613629.76      1099596.29       613608.49
#Sta/Elev= 30
  4509.2  987.29  4556.2  985.55    4598  977.54  4628.2  968.67  4682.2  945.82
  4735.8  925.75  4776.8  908.02  4808.8  892.71    4813  889.32  4821.5  887.04
  4907.3  844.24    4957  815.94    4977  809.28  4980.7  799.64  5019.3  799.64
  5031.2  805.19  5049.5  809.48  5146.9  806.96  5358.9  806.15  5435.7  807.13
  5461.5     808  5516.3  813.86  5701.3  815.68  5729.9  817.64  5748.8  815.62
  5762.8  817.45  5802.8  818.25  5893.9  824.64  5927.1  824.02  5936.8   825.5
#Mann= 3 ,-1 , 0
  4509.2     .09       0    4977     .05       0  5031.2     .09       0
Bank Sta=4977,5031.2
Exp/Cntr=0.5,0.3

Type RM Length L Ch R = 1 ,42257   ,114,114,114
BEGIN DESCRIPTION:
US-64&ALT-74-US
END DESCRIPTION:
XS GIS Cut Line= 6
      1101471.84       612932.99      1101177.44       612957.87
      1100503.64       613132.02        1100174.        613250.2
      1100072.41       613295.81      1099666.06        613505.2
#Sta/Elev= 30
  4101.5  844.16  4177.5  845.88  4220.7  842.33  4230.9  845.01  4247.1  841.55
  4293.9  842.77  4305.2  839.46  4330.6   843.4    4357  838.98  4500.3  838.09
  4515.2  836.56  4537.7  826.62    4546   828.3  4573.1  821.85  4585.6  823.53
  4663.4  813.34  4725.1  813.79  4781.1  808.68  4893.9   810.5  4952.8  806.67
  4975.2  804.91  4977.5     800    4979  797.82  5022.5     800  5023.5  804.73
  5044.1  808.75  5091.5  810.87    5365  807.58  5698.1  809.33  6011.7  824.31
#Mann= 4 ,-1 , 0
  4101.5     .06       0  4952.8     .09       0  4977.5     .05       0
  5022.5     .09       0
#XS Ineff= 2 , 0
       0    4899  829.12    5101       0  825.92
Permanent Ineff=
       F       F
Bank Sta=4977.5,5022.5
Exp/Cntr=0.5,0.3

Type RM Length L Ch R = 3 ,42201   ,,,
BEGIN DESCRIPTION:
US-64&ALT-74
Structure ID: US-64&ALT-74
Approximate Survey Structure
END DESCRIPTION:
Bridge Culvert--1,0,-1,-1, 0
Deck Dist Width WeirC Skew NumUp NumDn MinLoCord MaxHiCord MaxSubmerge Is_Ogee
41,30,3,0, 60, 60, , , , 0, 1,1,,
  4128.1  4348.2  4354.4  4369.1  4377.9  4386.4  4399.6  4422.9  4559.4  4565.8
  4619.2  4638.4  4651.8  4694.7  4710.9  4721.4  4728.9  4748.2  4751.6  4799.6
  4815.5  4869.2  4874.7  4878.9  4913.1  4923.1    4940    4940    5060    5060
  5069.1  5129.1  5222.7  5343.1    5362  5369.2  5380.2  5416.6  5429.1  5438.1
  5483.2  5492.2  5514.4  5521.6  5536.6  5552.1  5558.1  5588.7  5604.2  5613.6
  5619.9  5644.7    5665  5759.3  5775.4  5782.1  5792.1  5853.9  5929.6  6054.1
  843.14  839.47  839.04  839.33   840.1   838.6  838.71   837.9  835.45  835.64
  834.02  834.01  833.25  832.81  832.15  832.53   831.8  831.94  831.55  830.87
  830.18  829.81  829.11  829.58  828.64  828.78     830     830     830     830
  826.74  825.02  824.13  821.66  820.77  821.24  820.74  820.42  819.69   820.1
  818.88  819.36  818.67  819.18  818.39  818.66  818.24  818.72  818.04  818.68
  818.25  818.05  818.52  818.98  819.35  820.65  819.44  820.11  821.68  825.24
  777.82  777.82  777.82  777.82  777.82  777.82  777.82  777.82  777.82  777.82
  777.82  777.82  777.82  777.82  777.82  777.82  777.82  777.82  777.82  777.82
  777.82  777.82  777.82  777.82  777.82  777.82  777.82     828     828  777.82
  777.82  777.82  777.82  777.82  777.82  777.82  777.82  777.82  777.82  777.82
  777.82  777.82  777.82  777.82  777.82  777.82  777.82  777.82  777.82  777.82
  777.82  777.82  777.82  777.82  777.82  777.82  777.82  777.82  777.82  777.82
  4128.1  4348.2  4354.4  4369.1  4377.9  4386.4  4399.6  4422.9  4559.4  4565.8
  4619.2  4638.4  4651.8  4694.7  4710.9  4721.4  4728.9  4748.2  4751.6  4799.6
  4815.5  4869.2  4874.7  4878.9  4913.1  4923.1    4940    4940    5060    5060
  5069.1  5129.1  5222.7  5343.1    5362  5369.2  5380.2  5416.6  5429.1  5438.1
  5483.2  5492.2  5514.4  5521.6  5536.6  5552.1  5558.1  5588.7  5604.2  5613.6
  5619.9  5644.7    5665  5759.3  5775.4  5782.1  5792.1  5853.9  5929.6  6054.1
  843.14  839.47  839.04  839.33   840.1   838.6  838.71   837.9  835.45  835.64
  834.02  834.01  833.25  832.81  832.15  832.53   831.8  831.94  831.55  830.87
  830.18  829.81  829.11  829.58  828.64  828.78     830     830     830     830
  826.74  825.02  824.13  821.66  820.77  821.24  820.74  820.42  819.69   820.1
  818.88  819.36  818.67  819.18  818.39  818.66  818.24  818.72  818.04  818.68
  818.25  818.05  818.52  818.98  819.35  820.65  819.44  820.11  821.68  825.24
  777.82  777.82  777.82  777.82  777.82  777.82  777.82  777.82  777.82  777.82
  777.82  777.82  777.82  777.82  777.82  777.82  777.82  777.82  777.82  777.82
  777.82  777.82  777.82  777.82  777.82  777.82  777.82     828     828  777.82
  777.82  777.82  777.82  777.82  777.82  777.82  777.82  777.82  777.82  777.82
  777.82  777.82  777.82  777.82  777.82  777.82  777.82  777.82  777.82  777.82
  777.82  777.82  777.82  777.82  777.82  777.82  777.82  777.82  777.82  777.82
Pier Skew, UpSta & Num, DnSta & Num=  ,4970, 2 ,4970, 2 , 0 , 0 , 0 ,0,0
       2       2
  805.25     828
       2       2
  808.18     828
Pier Skew, UpSta & Num, DnSta & Num=  ,5030, 2 ,5030, 2 , 0 , 0 , 0 ,0,0
       2       2
  805.94     828
       2       2
  807.25     828
Abutment Skew #Up #Dn= , 2 , 2
    4940  4941.5
     828  807.38
    4940  4941.5
     828  807.64
Abutment Skew #Up #Dn= , 2 , 2
  5058.5    5060
   808.7     828
  5058.5    5060
  809.92     828
BR Coef= 1 , 1 , 0 ,1.25, 0 ,,,0.8,0,2,0,
WSPro=,,,, 1 ,,,, 0 ,,,, 0 ,,,,-1 ,-1 ,-1 , 0 , 0 , 0 , 0 , 0
BC Design=,, 0 ,, 0 ,,,,,,
BC HTab HWMax=846.25

Type RM Length L Ch R = 1 ,42143   ,300,300,300
BEGIN DESCRIPTION:
US-64&ALT-74-DS
END DESCRIPTION:
XS GIS Cut Line= 6
      1101475.98        612839.7      1101177.44        612893.6
      1100945.24       612903.97      1100339.86        613071.9
      1099964.61       613233.61       1099624.6       613434.71
#Sta/Elev= 30
  4117.2     884  4178.6  874.49  4320.2  859.23  4364.8  847.96  4451.5  841.23
  4599.6  822.07  4624.7   811.5  4648.3  807.08  4671.9   808.9  4888.8  806.45
  4960.7  809.86  4974.2  806.49  4977.5  799.57    4979  797.57    5021  797.57
  5022.5  799.57  5026.9  806.67  5048.9  811.75    5097  806.58  5216.8  808.78
  5371.2  803.68    5440  806.75  5459.3   805.2  5472.7  809.87    5480  806.14
  5640.6  807.42  5711.3  810.94  5817.4  808.49  5955.8  813.69  6087.2  824.47
#Mann= 4 ,-1 , 0
  4117.2     .06       0  4960.7     .09       0  4977.5     .05       0
  5022.5     .09       0
#XS Ineff= 2 , 0
       0    4897   829.1    5103       0  825.82
Permanent Ineff=
       F       F
Bank Sta=4977.5,5022.5
Exp/Cntr=0.5,0.3

Type RM Length L Ch R = 1 ,41843   ,317,317,317
BEGIN DESCRIPTION:
Mtn_Crk-80.0
END DESCRIPTION:
XS GIS Cut Line= 6
      1100978.41       612582.62      1100704.74       612707.01
      1100636.33       612713.23      1100588.64       612709.09
      1100538.89       612709.09      1100416.57       612731.89
#Sta/Elev= 30
  4648.9  832.24  4657.9  829.57  4671.4  824.87  4681.3  822.08  4694.6  816.78
  4704.1  814.01  4709.5  811.24    4725  807.62  4737.7  805.48  4757.7  804.77
  4905.6  804.45    4946  804.87  4949.5  804.38  4980.4  797.26  5019.6  797.26
  5032.6  807.74    5040  806.93  5075.3  805.17  5086.5   805.1  5099.4  805.72
  5112.5  807.31  5132.4  810.57  5137.8   811.8  5149.9  813.13  5158.3  814.91
  5170.9   816.8  5176.9  818.22  5182.1  818.77  5184.6  818.52  5240.3  827.37
#Mann= 5 ,-1 , 0
  4648.9     .09       0    4725     .06       0  4905.6     .09       0
    4946     .05       0  5032.6     .09       0
#XS Ineff= 2 , 0
       0    4847     815               0
Permanent Ineff=
       F       F
Bank Sta=4946,5032.6
Exp/Cntr=0.3,0.1