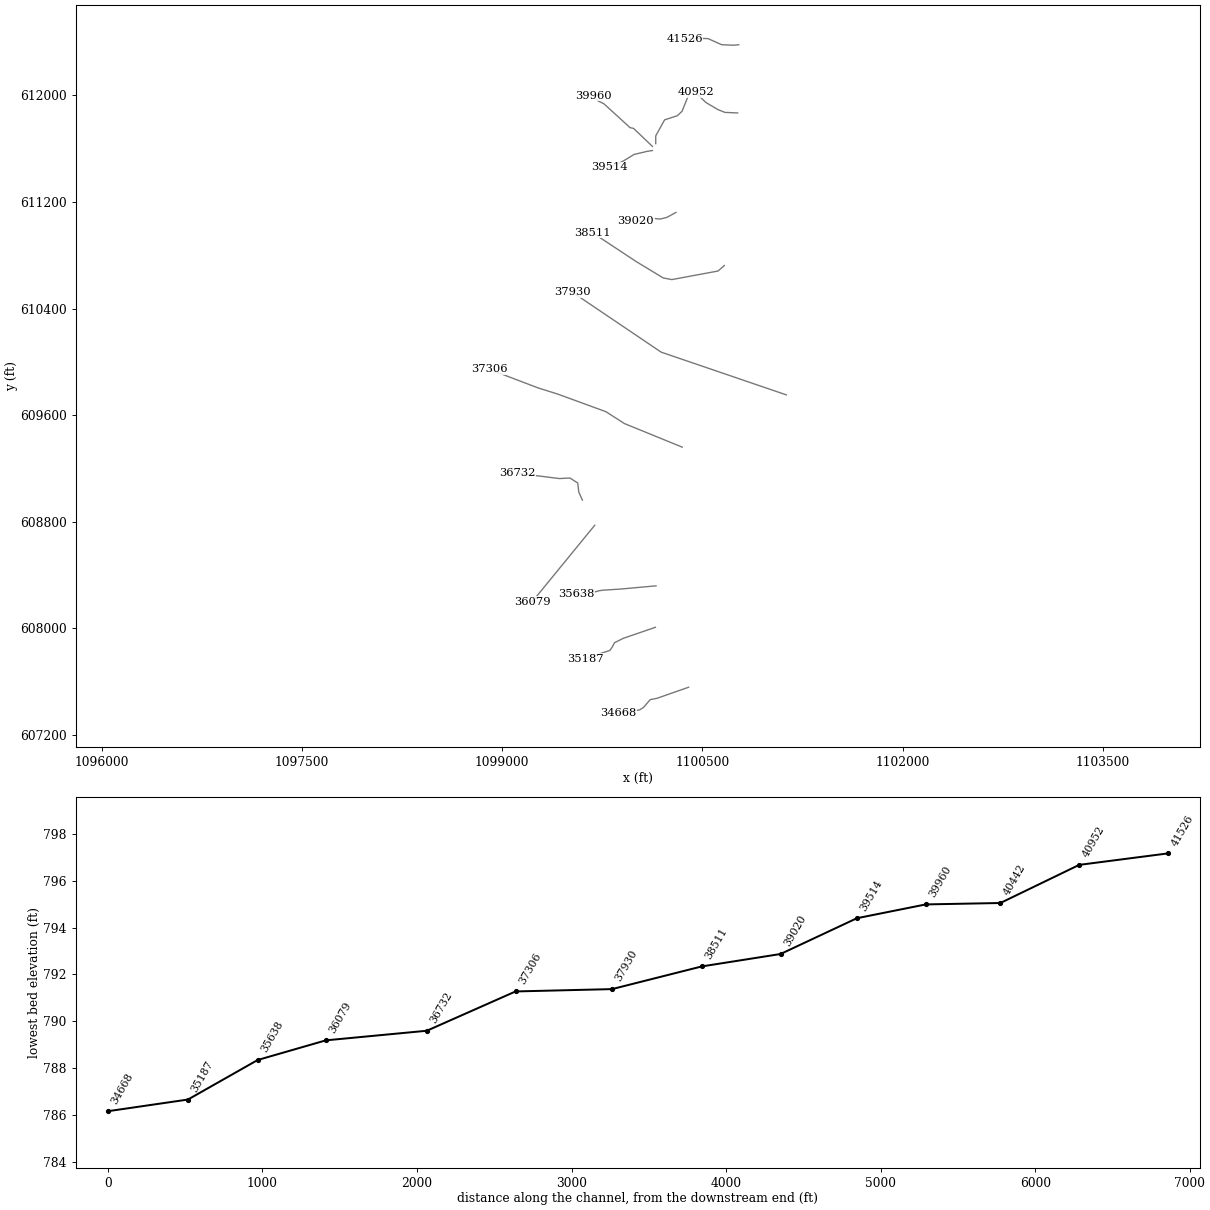
HEC-RAS study lds_mountain_crk.prj: Mountain Creek Limited Detail Study

--- lds_mountain_crk.g01 (geometry) --- (continued)

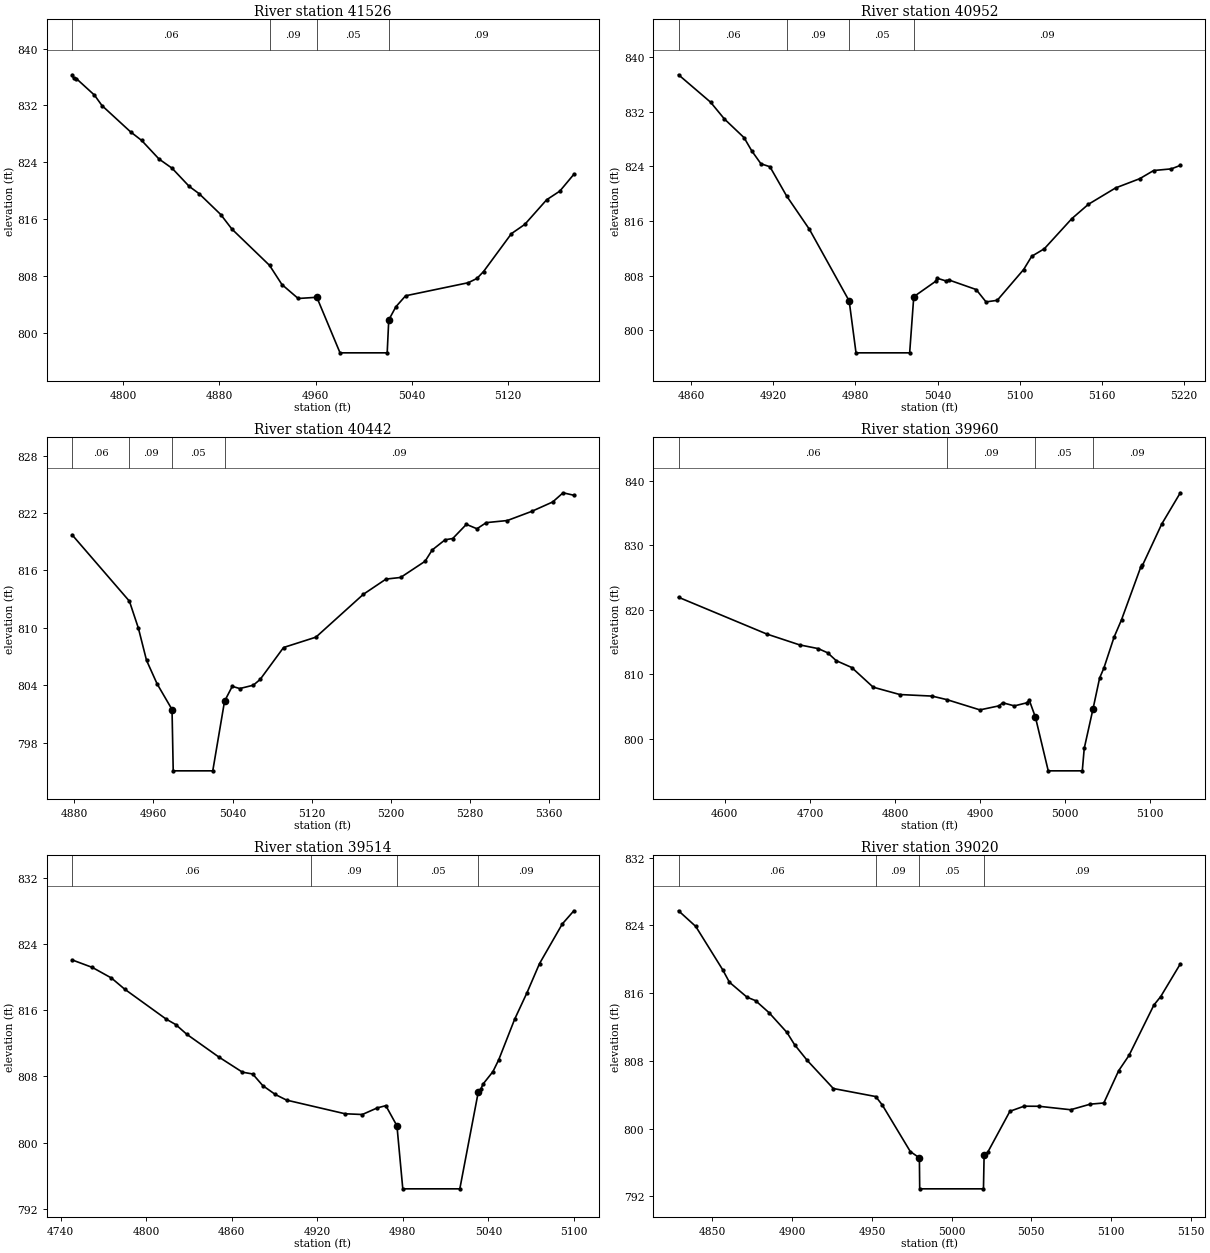
Type RM Length L Ch R = 1 ,41526   ,574,574,574
BEGIN DESCRIPTION:
Mtn_Crk-79.0
END DESCRIPTION:
XS GIS Cut Line= 6
      1100773.16       612379.45      1100735.84        612375.3
      1100644.62       612379.45      1100543.03       612425.06
      1100472.54       612427.13      1100366.81       612420.91
#Sta/Elev= 30
  4757.6  836.31  4758.8  835.88  4761.1  835.78  4776.2  833.45  4782.5  831.97
  4806.2  828.28  4815.5  827.06  4829.9  824.45  4840.8  823.15    4855   820.6
  4863.2  819.58  4881.2  816.64  4890.5  814.59  4921.8  809.48  4932.1  806.78
  4945.6  804.82  4961.1  804.99  4980.4  797.17  5019.6  797.17  5020.9   801.8
  5026.8  803.65  5034.9   805.2    5087  807.04  5094.2  807.64  5099.7  808.61
  5122.9  813.95    5134  815.25  5152.2  818.72  5163.1  819.93  5174.8   822.3
#Mann= 4 ,-1 , 0
  4757.6     .06       0  4921.8     .09       0  4961.1     .05       0
  5020.9     .09       0
Bank Sta=4961.1,5020.9
Exp/Cntr=0.3,0.1

Type RM Length L Ch R = 1 ,40952   ,510,510,510
BEGIN DESCRIPTION:
Mtn_Crk-78.0
END DESCRIPTION:
XS GIS Cut Line= 6
      1100764.87       611867.36       1100669.5       611871.51
      1100617.67       611892.24      1100526.45       611946.14
       1100468.4       612002.12      1100451.81       612024.92
#Sta/Elev= 30
  4850.7   837.4  4874.1  833.39  4884.2  830.93  4898.6  828.19  4904.2  826.26
  4910.9  824.37  4917.5  823.93  4929.6  819.68  4946.4  814.75  4975.4  804.28
  4980.4  796.68  5019.6  796.68  5022.6   804.9  5038.5  807.14  5039.8   807.6
  5045.8  807.23  5048.3  807.35  5068.2  805.95  5075.4  804.14  5083.6  804.37
  5102.9  808.88  5108.8  810.82    5118  811.92  5138.1  816.33  5150.2  818.43
  5170.1  820.83  5187.7  822.18  5197.9  823.38  5210.8  823.62  5217.4  824.13
#Mann= 4 ,-1 , 0
  4850.7     .06       0  4929.6     .09       0  4975.4     .05       0
  5022.6     .09       0
Bank Sta=4975.4,5022.6
Exp/Cntr=0.3,0.1

Type RM Length L Ch R = 1 ,40442   ,482,482,482
BEGIN DESCRIPTION:
Mtn_Crk-77.0
END DESCRIPTION:
XS GIS Cut Line= 6
       1100151.2       611637.23       1100151.2       611695.28
      1100217.54       611815.53      1100312.91       611846.63
      1100348.15        611879.8      1100408.27       612029.07
#Sta/Elev= 30
  4877.7  819.72  4935.7  812.78  4944.8  809.95    4953   806.6  4963.7  804.14
  4978.8  801.46    4980  795.05    5020  795.05  5031.9  802.32  5039.7  803.88
  5047.3  803.65    5061     804  5067.9   804.6  5091.6  807.94  5124.3  809.02
  5172.3   813.5  5195.2  815.09    5210  815.26  5234.7  816.95  5241.9  818.13
    5255   819.2  5262.7  819.33  5276.5  820.81  5287.2  820.35  5296.6  820.99
  5317.9  821.21  5342.4  822.16  5363.8  823.15  5374.3  824.11  5385.2  823.85
#Mann= 4 ,-1 , 0
  4877.7     .06       0  4935.7     .09       0  4978.8     .05       0
  5031.9     .09       0
Bank Sta=4978.8,5031.9
Exp/Cntr=0.3,0.1

Type RM Length L Ch R = 1 ,39960   ,446,446,446
BEGIN DESCRIPTION:
Mtn_Crk-76.0
END DESCRIPTION:
XS GIS Cut Line= 6
      1100126.32        611616.5      1099985.34       611751.26
      1099958.39       611757.48       1099763.5       611935.78
      1099717.89       611958.58      1099684.72       611997.97
#Sta/Elev= 30
  4545.6   821.9  4649.3   816.2  4687.8  814.52  4709.8  813.94  4720.8  813.29
  4730.9  812.07  4749.1  811.01  4774.3  807.96  4805.6  806.82  4843.4  806.58
  4860.9  806.03  4899.7  804.44  4922.3  805.07  4926.4  805.55  4940.2  805.06
  4954.6  805.53  4957.7  805.95    4965  803.28    4980  794.99    5020  794.99
  5022.3  798.48  5032.7  804.65  5040.4   809.4  5045.3  810.89  5057.3   815.7
  5066.1  818.41  5088.8  826.62  5090.7  826.84  5113.3  833.24  5135.2   838.1
#Mann= 4 ,-1 , 0
  4545.6     .06       0  4860.9     .09       0    4965     .05       0
  5032.7     .09       0
Bank Sta=4965,5032.7
Exp/Cntr=0.3,0.1

Type RM Length L Ch R = 1 ,39514   ,494,494,494
BEGIN DESCRIPTION:
Mtn_Crk-75.0
END DESCRIPTION:
XS GIS Cut Line= 6
      1100126.32        611585.4      1100086.93       611579.18
      1099989.48       611556.38      1099914.85       611510.77
       1099879.6       611492.11      1099800.82       611461.01
#Sta/Elev= 30
    4748  822.09  4762.2  821.18  4775.6   819.9  4784.9  818.55    4814  814.93
  4820.7  814.27  4828.5  813.09  4850.9  810.35  4867.5  808.51  4874.7  808.29
  4881.8  806.88  4890.6  805.81  4898.5  805.13  4939.5  803.48  4951.6  803.39
  4962.1  804.19  4968.1  804.46  4975.9  802.02    4980   794.4    5020   794.4
  5032.9  806.07  5034.8  806.47  5036.2  807.05  5043.2  808.57  5047.3  810.01
  5058.5  814.93  5067.1  818.11  5075.9  821.64  5091.9  826.44    5100  828.03
#Mann= 4 ,-1 , 0
    4748     .06       0  4915.6     .09       0  4975.9     .05       0
  5032.9     .09       0
Bank Sta=4975.9,5032.9
Exp/Cntr=0.3,0.1

Type RM Length L Ch R = 1 ,39020   ,509,509,509
BEGIN DESCRIPTION:
Mtn_Crk-74.0
END DESCRIPTION:
XS GIS Cut Line= 6
      1100302.54         611121.      1100234.12       611083.68
      1100184.37       611071.25      1100122.17       611077.46
      1100047.53       611056.73      1100001.92       611056.73
#Sta/Elev= 30
  4828.7  825.74  4839.5  823.89  4856.4  818.77  4860.6   817.3  4871.7  815.52
    4877  815.12  4885.5  813.69  4896.7  811.36  4901.5  809.91  4909.4  808.06
  4925.8  804.73  4952.4  803.78  4956.5  802.79  4974.1  797.28  4979.8  796.53
    4980  792.87    5020  792.87  5020.4  796.82  5022.6  797.17  5036.6  802.04
  5045.5  802.64  5054.8  802.63  5074.7  802.22    5087  802.88  5095.5  803.02
  5104.8  806.83  5111.3  808.64  5126.9  814.59  5131.2   815.6  5143.5  819.46
#Mann= 4 ,-1 , 0
  4828.7     .06       0  4952.4     .09       0  4979.8     .05       0
  5020.4     .09       0
Bank Sta=4979.8,5020.4
Exp/Cntr=0.3,0.1

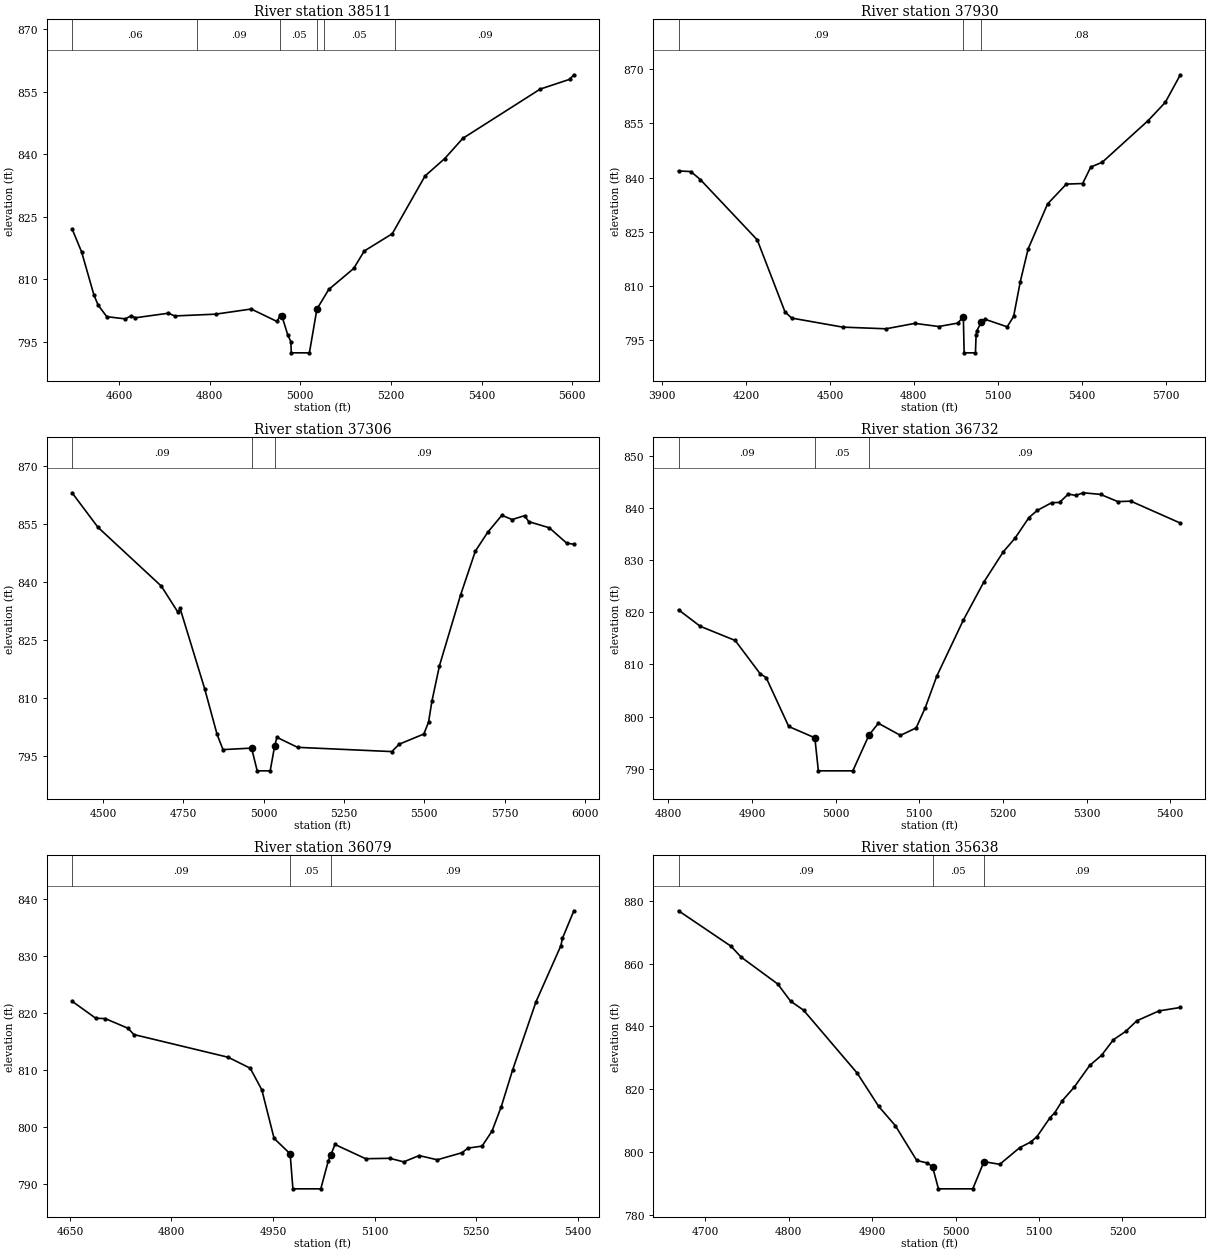
Type RM Length L Ch R = 1 ,38511   ,581,581,581
BEGIN DESCRIPTION:
Mtn_Crk-73.0
END DESCRIPTION:
XS GIS Cut Line= 6
      1100665.35       610722.94      1100617.67       610681.48
      1100271.44       610617.21      1100207.17       610629.65
      1100005.12       610752.23      1099679.82        610967.5
#Sta/Elev= 30
  4496.1  822.09  4517.2  816.54  4544.2  806.28  4553.4  803.83  4572.7  801.02
  4613.4  800.49  4626.7  801.23  4635.8  800.75  4708.8  801.85  4722.5  801.19
  4812.9  801.62  4891.5  802.85  4948.6  799.86  4955.9  801.43  4959.5  801.12
  4972.4  796.58    4979  795.04    4980  792.34    5020  792.34  5036.6  802.84
  5062.7  807.54  5117.8  812.58  5141.1  816.77  5202.9  820.91  5275.3  834.78
  5318.8  838.95  5358.7   843.8  5529.6  855.62  5594.3  857.95  5603.8  859.05
#Mann= 6 ,-1 , 0
  4496.1     .06       0  4771.7     .09       0  4955.9     .05       0
  5036.6     .09       0  5051.2     .05       0  5209.1     .09       0
Bank Sta=4959.5,5036.6
Exp/Cntr=0.3,0.1

Type RM Length L Ch R = 1 ,37930   ,624,624,624
BEGIN DESCRIPTION:
Mtn_Crk-72.0
END DESCRIPTION:
XS GIS Cut Line= 3
      1101129.31       609752.42      1100191.69       610072.94
      1099526.74       610522.61
#Sta/Elev= 30
  3958.9  841.83    4003  841.64  4036.7  839.44  4240.2  822.71  4339.4  802.74
  4363.4  801.01  4545.9   798.5  4700.2  798.04  4803.5  799.54  4888.9  798.67
  4956.4  799.61  4976.9   801.3  4979.8  791.37  5020.2  791.37  5022.5  796.35
  5025.3  797.51  5041.5  799.92  5053.3  800.71  5133.6  798.59  5156.6  801.46
  5180.5  811.12  5208.4  820.17    5278  832.67    5345  838.17  5403.4  838.33
  5432.3   842.9  5473.3  844.22  5637.4  855.78  5698.7  860.83  5752.5  868.49
#Mann= 3 ,-1 , 0
  3958.9     .09       0  4976.9     .05       0  5041.5     .08       0
Bank Sta=4976.9,5041.5
Exp/Cntr=0.3,0.1

Type RM Length L Ch R = 1 ,37306   ,574,574,574
BEGIN DESCRIPTION:
Mtn_Crk-71.0
END DESCRIPTION:
XS GIS Cut Line= 6
      1100349.55       609360.15      1099916.92       609537.06
      1099778.02       609626.21       1099415.2        609758.9
      1099270.08       609804.51      1098904.85       609943.77
#Sta/Elev= 30
  4403.6  863.07  4484.3  854.15  4681.5  838.96  4733.6  832.16  4739.6  833.27
  4816.2  812.49  4854.9  800.69  4873.3  796.75  4962.3  797.14  4979.8  791.27
  5020.2  791.27  5033.9  797.59  5041.1  799.92  5105.4  797.34  5398.8  796.24
  5421.5  798.14  5498.4  800.78  5513.1  803.87  5523.5  809.24  5547.1  818.44
  5612.7  836.66  5658.7     848  5697.2  852.87  5741.2  857.26  5773.3  856.15
  5811.9  857.17    5825  855.61  5888.7  854.04  5942.9  850.07  5965.3  849.78
#Mann= 3 ,-1 , 0
  4403.6     .09       0  4962.3     .05       0  5033.9     .09       0
Bank Sta=4962.3,5033.9
Exp/Cntr=0.3,0.1

Type RM Length L Ch R = 1 ,36732   ,653,653,653
BEGIN DESCRIPTION:
Mtn_Crk-70.0
END DESCRIPTION:
XS GIS Cut Line= 6
      1099601.79       608962.78      1099574.84       609022.91
      1099566.55       609091.32       1099508.5       609128.64
      1099429.72       609124.49      1099115.33       609164.02
#Sta/Elev= 30
  4812.3  820.46  4838.2   817.3    4880  814.58  4909.8  808.21    4917  807.46
    4944  798.09  4975.2  795.92  4979.4  789.59  5020.6  789.59  5039.9  796.44
  5051.1  798.71  5077.5  796.39  5096.3  797.82  5107.2  801.71    5121  807.77
  5152.6  818.46  5176.9   825.7  5200.3  831.55  5214.5   834.2  5231.1  838.14
    5241  839.51  5258.3  840.99  5267.6  841.04  5278.1  842.64  5287.2  842.38
  5295.9  842.89  5316.6  842.58  5337.3   841.2  5352.9  841.28    5412  837.08
#Mann= 3 ,-1 , 0
  4812.3     .09       0  4975.2     .05       0  5039.9     .09       0
Bank Sta=4975.2,5039.9
Exp/Cntr=0.3,0.1

Type RM Length L Ch R = 1 ,36079   ,441,441,441
BEGIN DESCRIPTION:
Mtn_Crk-69.0
END DESCRIPTION:
XS GIS Cut Line= 2
      1099694.17       608774.14      1099225.36       608200.08
#Sta/Elev= 30
  4653.2  822.12  4688.2  819.13  4702.2  819.07  4735.7  817.38  4744.5  816.27
  4883.9  812.28  4916.4  810.35  4933.5  806.56  4951.6  798.04  4975.3  795.33
  4979.4  789.18  5020.6  789.18  5031.7   794.1  5035.6  795.18  5041.5  796.97
  5086.8  794.47  5122.3  794.54  5143.1  793.92  5165.9  795.02  5192.6  794.28
  5229.1  795.52  5237.9  796.33  5258.8  796.68  5273.5  799.31  5287.2  803.62
    5304  810.07  5338.5  822.03  5375.2  831.86  5377.5  833.15  5394.4     838
#Mann= 3 , 0 , 0
  4653.2     .09       0  4975.3     .05       0  5035.6     .09       0
Bank Sta=4975.3,5035.6
Exp/Cntr=0.3,0.1

Type RM Length L Ch R = 1 ,35638   ,451,451,451
BEGIN DESCRIPTION:
Mtn_Crk-67.0
END DESCRIPTION:
XS GIS Cut Line= 6
      1100153.41       608319.68      1099883.75       608295.21
      1099753.14       608286.91      1099726.19       608282.77
      1099697.16       608274.48      1099555.44       608257.49
#Sta/Elev= 30
  4667.7   876.8  4730.7  865.51  4742.6   862.1  4786.7   853.5  4802.1  848.04
  4817.6  845.19    4882  825.15  4907.7  814.58  4927.7  808.44  4953.4  797.37
  4966.2  796.55  4972.4  795.32  4979.4  788.34  5020.6  788.34    5034  796.99
  5052.9  796.14  5076.9  801.45  5090.1  803.23  5097.6  804.96  5113.1  810.93
  5118.8  812.51  5128.1  816.43  5141.9  820.58  5160.8  827.59    5175  830.82
  5189.2  835.76    5204  838.44  5217.4  841.82    5244  844.95  5269.5  846.04
#Mann= 3 ,-1 , 0
  4667.7     .09       0  4972.4     .05       0    5034     .09       0
Bank Sta=4972.4,5034
Exp/Cntr=0.3,0.1

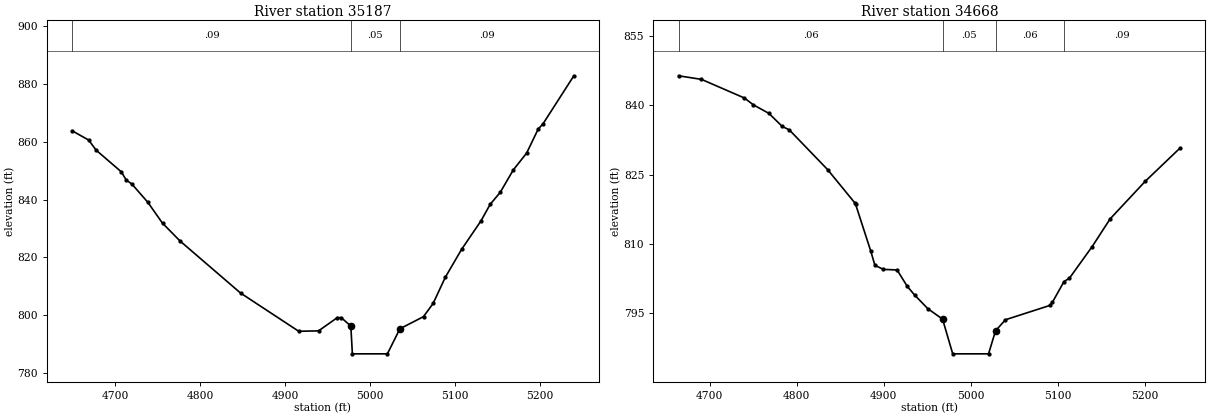
Type RM Length L Ch R = 1 ,35187   ,519,519,519
BEGIN DESCRIPTION:
Mtn_Crk-66.0
END DESCRIPTION:
XS GIS Cut Line= 6
      1100148.63       608008.73      1099908.63       607926.17
      1099842.29         607893.      1099823.63       607857.76
      1099807.04       607834.95      1099622.41       607774.32
#Sta/Elev= 30
  4649.6  863.87  4669.2  860.64  4677.9  857.15  4707.4  849.69  4713.4  846.79
  4719.9  845.45  4738.6  839.16    4756  831.88  4776.5  825.75  4847.9  807.68
  4916.3  794.46  4939.6   794.6  4961.5  799.15  4966.3  799.19  4977.6  796.25
  4979.4  786.65  5020.6  786.65  5035.3  795.32  5063.1  799.53  5074.4  804.09
  5088.8  813.18  5107.9  822.81  5130.8   832.7  5141.5  838.39  5153.3  842.52
  5168.7  850.29  5184.5  856.17  5197.9  864.38  5203.8  866.31    5240   882.9
#Mann= 3 ,-1 , 0
  4649.6     .09       0  4977.6     .05       0  5035.3     .09       0
Bank Sta=4977.6,5035.3
Exp/Cntr=0.3,0.1

Type RM Length L Ch R = 1 ,34668   ,290,290,290
BEGIN DESCRIPTION:
Mtn_Crk-65.0
END DESCRIPTION:
XS GIS Cut Line= 6
      1100397.39       607559.05      1100161.56       607476.29
      1100109.73       607465.92      1100059.97       607407.87
      1100030.95       607389.21      1099871.17       607362.92
#Sta/Elev= 30
    4664  846.39  4690.4  845.61  4739.7  841.58  4750.1  840.09    4768  838.24
  4783.2  835.43  4791.4  834.67  4835.5  826.06  4866.7  818.87  4867.7  818.54
  4885.2  808.35  4889.9  805.32  4899.6  804.45  4915.4  804.32    4927   800.8
  4935.5   798.9  4950.8  795.93  4967.7  793.67  4979.4  786.15  5020.6  786.15
  5028.6  791.12    5040  793.53    5091  796.63  5094.1  797.34  5107.4  801.81
  5113.7  802.55  5139.8  809.39  5160.5   815.4  5200.9  823.54  5241.2  830.79
#Mann= 4 ,-1 , 0
    4664     .06       0  4967.7     .05       0  5028.6     .06       0
  5107.4     .09       0
Bank Sta=4967.7,5028.6
Exp/Cntr=0.3,0.1