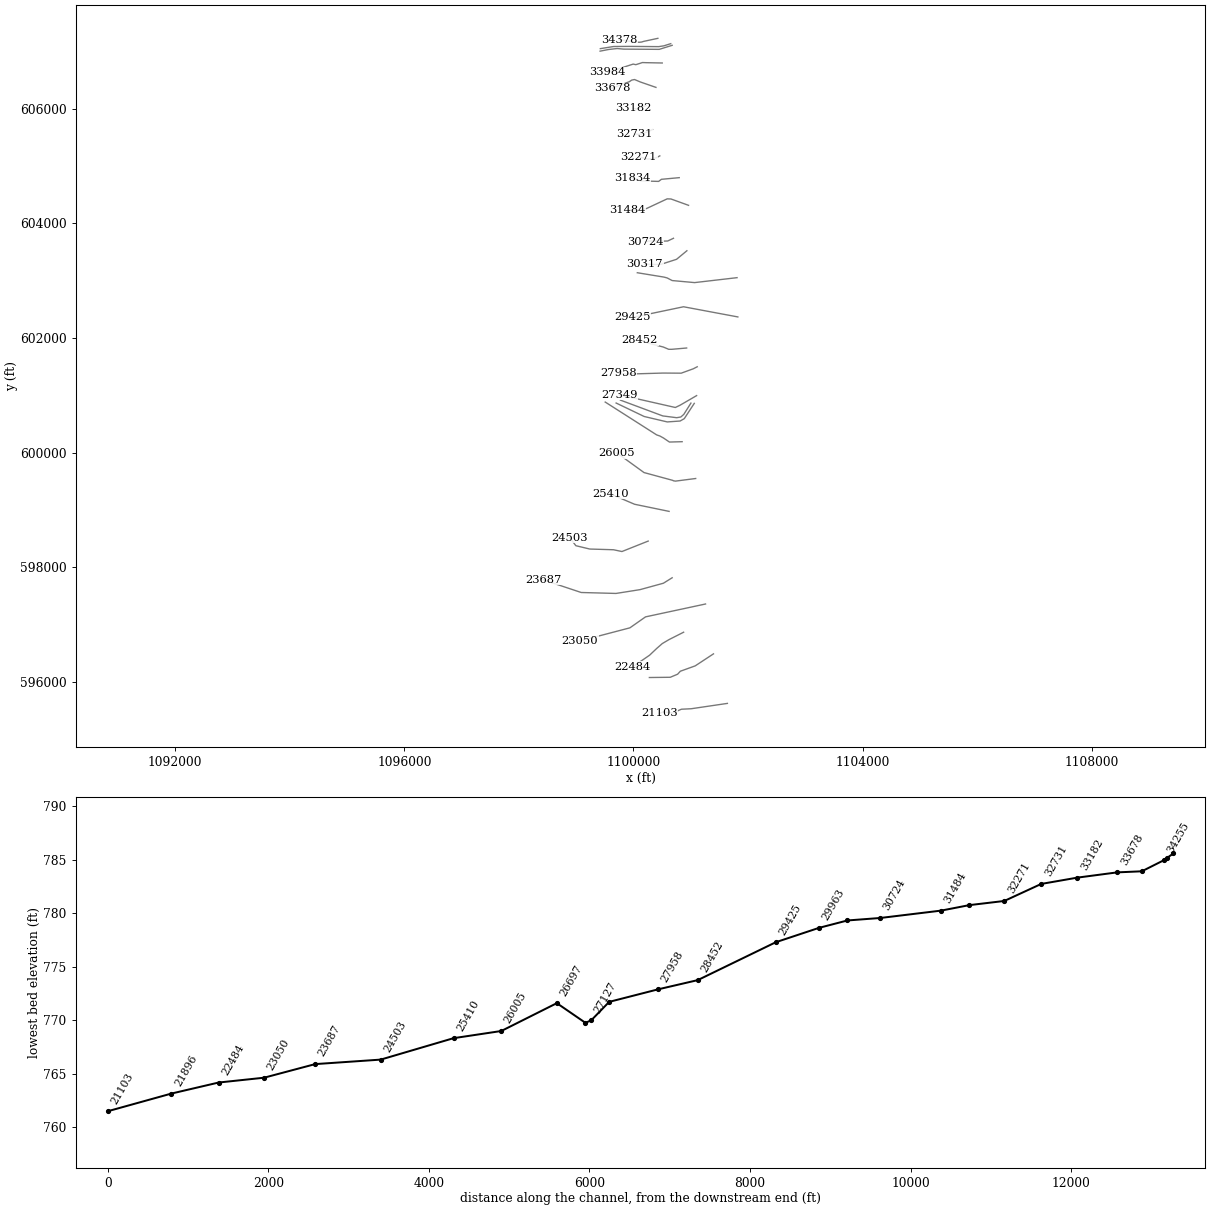
HEC-RAS study lds_mountain_crk.prj: Mountain Creek Limited Detail Study

--- lds_mountain_crk.g01 (geometry) --- (continued)

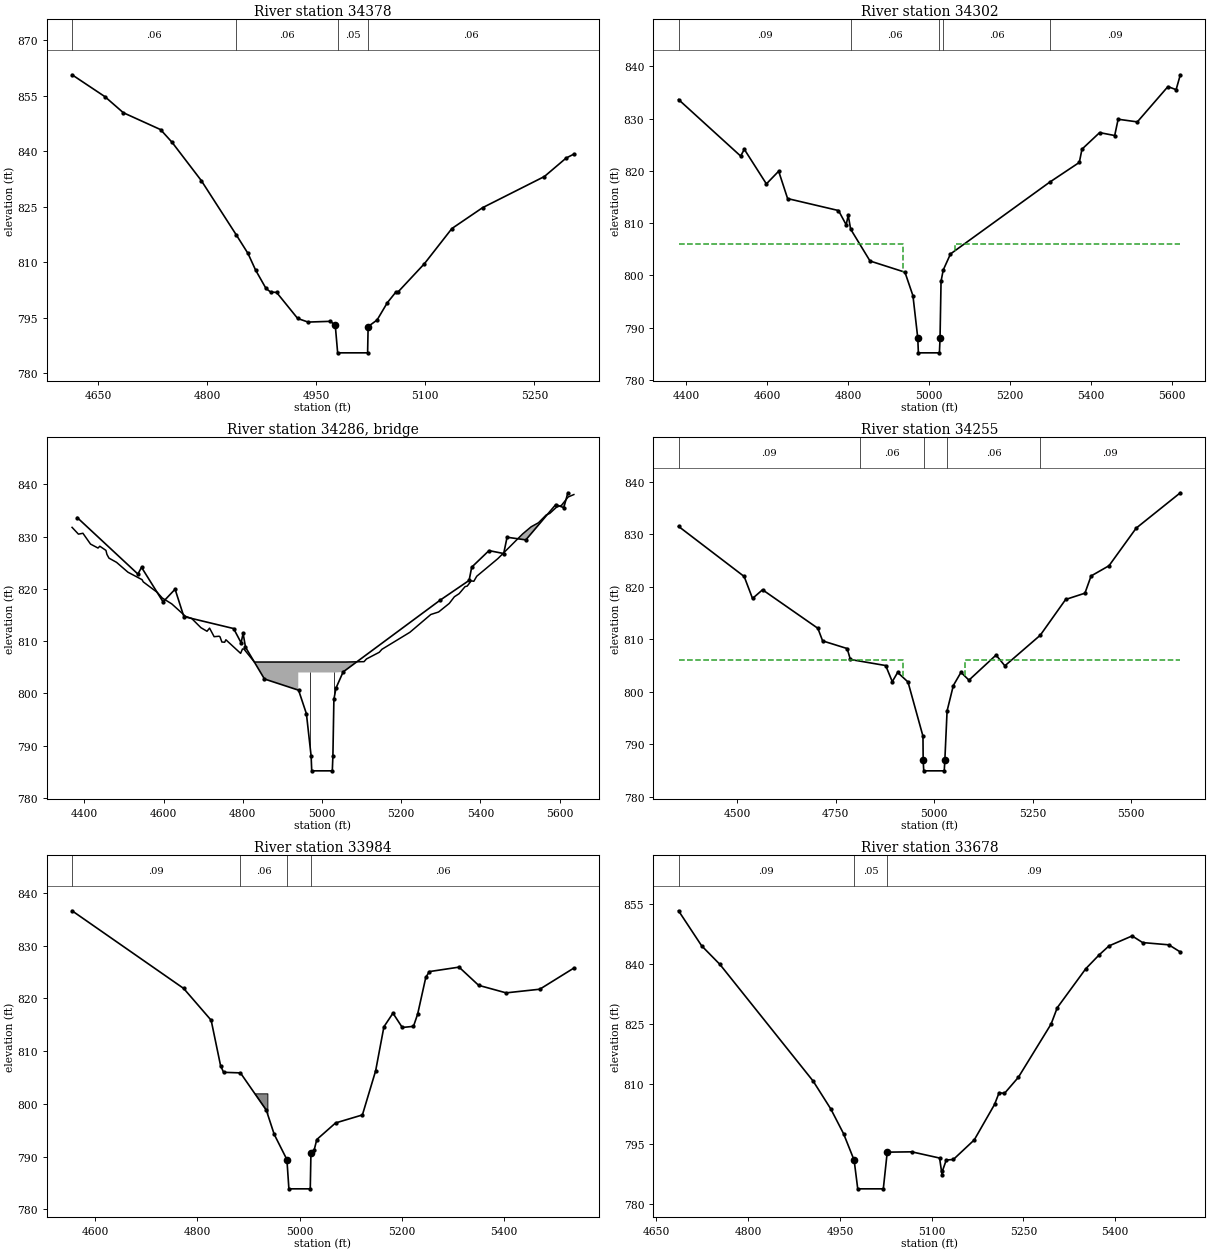
Type RM Length L Ch R = 1 ,34378   ,76,76,76
BEGIN DESCRIPTION:
Mtn_Crk-64.0
END DESCRIPTION:
XS GIS Cut Line= 6
      1100426.09       607231.36      1100176.07       607177.74
      1100144.98       607167.38      1100109.73       607163.23
      1100047.53       607163.23      1099746.79       607207.45
#Sta/Elev= 30
  4614.2  860.68  4659.3  854.78  4684.7  850.43  4735.9  845.87  4751.7  842.44
  4791.9   832.1  4840.2  817.37  4856.1  812.42  4866.5  807.95  4880.9  802.95
  4887.1  802.02  4895.5  801.88  4924.4  794.86  4938.7  793.88  4969.5  794.08
  4975.3  793.13  4976.1  793.04  4979.4  785.57  5020.6  785.57  5021.3  792.67
  5033.6  794.43  5047.6  799.08  5059.5     802  5062.8  802.09  5098.7  809.65
  5136.5  819.15  5178.7  824.78  5263.7   833.2  5293.6  838.19  5304.2  839.25
#Mann= 4 ,-1 , 0
  4614.2     .06       0  4840.2     .06       0  4979.4     .05       0
  5021.3     .06       0
Bank Sta=4975.3,5021.3
Exp/Cntr=0.5,0.3

Type RM Length L Ch R = 1 ,34302   ,47,47,47
BEGIN DESCRIPTION:
Coopers Gap Rd. SR-1172-US
END DESCRIPTION:
XS GIS Cut Line= 6
      1100650.84       607138.35      1100532.67       607101.03
      1100441.45       607086.52      1099929.36       607090.67
      1099653.62        607088.6      1099421.42       607051.28
#Sta/Elev= 30
  4381.6  833.66    4535  822.84  4544.1  824.13  4598.6  817.51  4628.9  819.94
    4651   814.7  4776.7  812.41  4795.7  809.68  4800.7  811.49  4806.7  808.85
  4854.6  802.75  4940.8  800.61  4960.6   796.1  4972.5     788    4974  785.17
    5026  785.17  5027.5     788    5030  798.87  5035.4  801.03  5053.3   804.1
  5298.3  817.84  5371.5  821.62  5378.1  824.16  5421.7  827.33  5458.9  826.77
  5467.4  829.89  5514.8  829.38  5590.4  836.14  5610.6  835.55    5621   838.4
#Mann= 5 ,-1 , 0
  4381.6     .09       0  4806.7     .06       0    5026     .05       0
  5035.4     .06       0  5298.3     .09       0
#XS Ineff= 2 , 0
       0    4936     806    5064       0     806
Permanent Ineff=
       F       F
Bank Sta=4972.5,5027.5
Exp/Cntr=0.5,0.3

Type RM Length L Ch R = 3 ,34286   ,,,
BEGIN DESCRIPTION:
Coopers Gap Rd. SR-1172
Structure ID: Coopers Gap Rd. SR-1172
Approximate Survey Structure
END DESCRIPTION:
Bridge Culvert--1,0,-1,-1, 0
Deck Dist Width WeirC Skew NumUp NumDn MinLoCord MaxHiCord MaxSubmerge Is_Ogee
4,24,3,0, 60, 60, , , , 0, 1,1,,
  4368.7  4384.8  4396.1  4415.3  4434.2  4438.8  4454.3  4456.7  4461.9  4481.1
  4509.9  4545.4  4548.5  4583.7  4596.6  4620.5  4655.2  4670.8  4694.2  4709.5
    4716  4727.5  4740.2  4742.3  4747.1  4754.1  4757.2  4794.4  4799.1  4802.8
  4829.2    4940    4940    5060    5060  5106.1  5112.3  5144.7  5151.2  5221.9
  5274.8  5294.5  5321.4  5334.3  5346.4  5361.4  5366.7  5376.8  5383.4  5390.8
  5444.4  5506.7    5528  5546.8  5566.3  5575.2  5592.3  5604.7  5621.8  5636.1
  831.78  830.48  830.65  828.58  827.82  828.17  827.37  826.61  825.89  825.08
  823.19  821.77  821.34  819.34  818.25  817.13  814.75  814.34  812.57  811.89
  812.49  810.85  810.94  810.83  809.83  809.79  810.26  807.66   808.5  808.48
     806     806     806     806     806  806.07  806.59  807.87  808.43  811.69
   815.1  815.58  817.22  818.49  819.09  820.44  820.53  821.54  821.46  822.42
  825.81  830.52  831.88  832.67  834.16  834.45  835.64  835.99   837.6  838.06
  765.17  765.17  765.17  765.17  765.17  765.17  765.17  765.17  765.17  765.17
  765.17  765.17  765.17  765.17  765.17  765.17  765.17  765.17  765.17  765.17
  765.17  765.17  765.17  765.17  765.17  765.17  765.17  765.17  765.17  765.17
  765.17  765.17     804     804  765.17  765.17  765.17  765.17  765.17  765.17
  765.17  765.17  765.17  765.17  765.17  765.17  765.17  765.17  765.17  765.17
  765.17  765.17  765.17  765.17  765.17  765.17  765.17  765.17  765.17  765.17
  4368.7  4384.8  4396.1  4415.3  4434.2  4438.8  4454.3  4456.7  4461.9  4481.1
  4509.9  4545.4  4548.5  4583.7  4596.6  4620.5  4655.2  4670.8  4694.2  4709.5
    4716  4727.5  4740.2  4742.3  4747.1  4754.1  4757.2  4794.4  4799.1  4802.8
  4829.2    4940    4940    5060    5060  5106.1  5112.3  5144.7  5151.2  5221.9
  5274.8  5294.5  5321.4  5334.3  5346.4  5361.4  5366.7  5376.8  5383.4  5390.8
  5444.4  5506.7    5528  5546.8  5566.3  5575.2  5592.3  5604.7  5621.8  5636.1
  831.78  830.48  830.65  828.58  827.82  828.17  827.37  826.61  825.89  825.08
  823.19  821.77  821.34  819.34  818.25  817.13  814.75  814.34  812.57  811.89
  812.49  810.85  810.94  810.83  809.83  809.79  810.26  807.66   808.5  808.48
     806     806     806     806     806  806.07  806.59  807.87  808.43  811.69
   815.1  815.58  817.22  818.49  819.09  820.44  820.53  821.54  821.46  822.42
  825.81  830.52  831.88  832.67  834.16  834.45  835.64  835.99   837.6  838.06
  765.17  765.17  765.17  765.17  765.17  765.17  765.17  765.17  765.17  765.17
  765.17  765.17  765.17  765.17  765.17  765.17  765.17  765.17  765.17  765.17
  765.17  765.17  765.17  765.17  765.17  765.17  765.17  765.17  765.17  765.17
  765.17  765.17     804     804  765.17  765.17  765.17  765.17  765.17  765.17
  765.17  765.17  765.17  765.17  765.17  765.17  765.17  765.17  765.17  765.17
  765.17  765.17  765.17  765.17  765.17  765.17  765.17  765.17  765.17  765.17
Pier Skew, UpSta & Num, DnSta & Num=  ,4970, 2 ,4970, 2 , 0 , 0 , 0 ,0,0
       1       1
   789.7     804
       1       1
  792.01     804
Pier Skew, UpSta & Num, DnSta & Num=  ,5030, 2 ,5030, 2 , 0 , 0 , 0 ,0,0
       1       1
  798.87     804
       1       1
  791.51     804
Abutment Skew #Up #Dn= , 2 , 2
    4940  4941.5
     804  800.45
    4940  4941.5
     804   800.1
Abutment Skew #Up #Dn= , 2 , 2
  5058.5    5060
     804     804
  5058.5    5060
  802.86     804
BR Coef= 1 , 1 , 0 ,1.25, 0 ,,,0.8,0,2,0,
WSPro=,,,, 1 ,,,, 0 ,,,, 0 ,,,,-1 ,-1 ,-1 , 0 , 0 , 0 , 0 , 0
BC Design=,, 0 ,, 0 ,,,,,,
BC HTab HWMax=838.65

Type RM Length L Ch R = 1 ,34255   ,271,271,271
BEGIN DESCRIPTION:
Coopers Gap Rd. SR-1172-DS
END DESCRIPTION:
XS GIS Cut Line= 6
      1100675.72       607109.33      1100449.74       607038.84
      1099827.77       607042.98      1099715.82       607053.35
      1099566.55       607036.76      1099417.28       607007.74
#Sta/Elev= 30
  4351.6   831.5  4518.2  821.95  4539.4  817.76  4564.8  819.42  4705.2  812.08
  4717.3  809.68  4779.6  808.22  4787.7  806.14  4877.4  804.98  4894.1  801.91
  4907.7  803.67    4934  801.85    4972  791.52  4972.5  786.92    4974  784.92
    5026  784.92  5027.5  786.92  5033.2  796.33  5049.1  801.18  5068.5  803.69
  5088.7   802.2  5157.5  806.98  5179.9  804.93  5269.7  810.76  5334.1  817.57
  5383.1  818.77  5398.7  822.05  5444.2     824  5513.1  831.16  5625.2   837.9
#Mann= 5 ,-1 , 0
  4351.6     .09       0  4812.5     .06       0    4974     .05       0
  5033.2     .06       0  5269.7     .09       0
#XS Ineff= 2 , 0
       0    4921     806    5079       0     806
Permanent Ineff=
       F       F
Bank Sta=4972.5,5027.5
Exp/Cntr=0.5,0.3

Type RM Length L Ch R = 1 ,33984   ,306,306,306
BEGIN DESCRIPTION:
Mtn_Crk-63.0
END DESCRIPTION:
XS GIS Cut Line= 6
      1100502.63       606800.82      1100211.32       606806.64
      1100157.42       606808.71      1100041.32       606771.39
       1099995.7       606781.76      1099550.66       606638.17
#Sta/Elev= 30
  4554.9  836.61  4773.2  821.89    4827  815.86  4845.4  807.27  4851.3  805.99
  4884.3  805.88  4934.9  798.81  4950.4  794.22  4975.2  789.45  4979.1   783.9
  5020.9   783.9  5022.2  790.56  5022.7  790.66  5028.3  791.17  5033.7  793.25
  5070.4  796.39  5122.9  797.91  5148.8  806.27    5165  814.62  5182.7   817.2
  5200.9  814.49  5222.8   814.7    5231  817.03  5246.9  823.97  5253.8  825.08
    5312  825.93  5350.3  822.48    5404  821.05  5469.9  821.74  5536.6  825.75
#Mann= 4 ,-1 , 0
  4554.9     .09       0  4884.3     .06       0  4975.2     .05       0
  5022.7     .06       0
#Block Obstruct= 2 , 0
       0    4937     802               0
Bank Sta=4975.2,5022.7
Exp/Cntr=0.3,0.1

Type RM Length L Ch R = 1 ,33678   ,496,496,496
BEGIN DESCRIPTION:
Mtn_Crk-62.0
END DESCRIPTION:
XS GIS Cut Line= 6
       1100392.6       606375.07      1100122.17        606468.7
      1100018.51       606512.24      1099968.75       606501.87
      1099929.36       606474.92       1099627.2       606360.72
#Sta/Elev= 30
  4686.1  853.23  4723.9  844.48  4753.8  839.83  4906.2   810.7  4935.1  803.73
  4955.9  797.57  4973.2  790.95  4979.1   783.8  5020.9   783.8  5027.3  792.96
  5067.4  793.04  5112.9  791.49    5117  787.18  5117.6  788.28  5123.8  790.99
  5135.4  791.13  5169.6  796.02  5202.8  804.88  5210.2   807.8    5219  807.63
  5241.7  811.65  5295.2  824.94  5305.3  829.03  5351.9  838.76  5373.6  842.19
  5389.9  844.46  5427.7  846.95  5444.9  845.29  5487.7  844.73  5506.5  842.94
#Mann= 3 , 0 , 0
  4686.1     .09       0  4973.2     .05       0  5027.3     .09       0
Bank Sta=4973.2,5027.3
Exp/Cntr=0.3,0.1

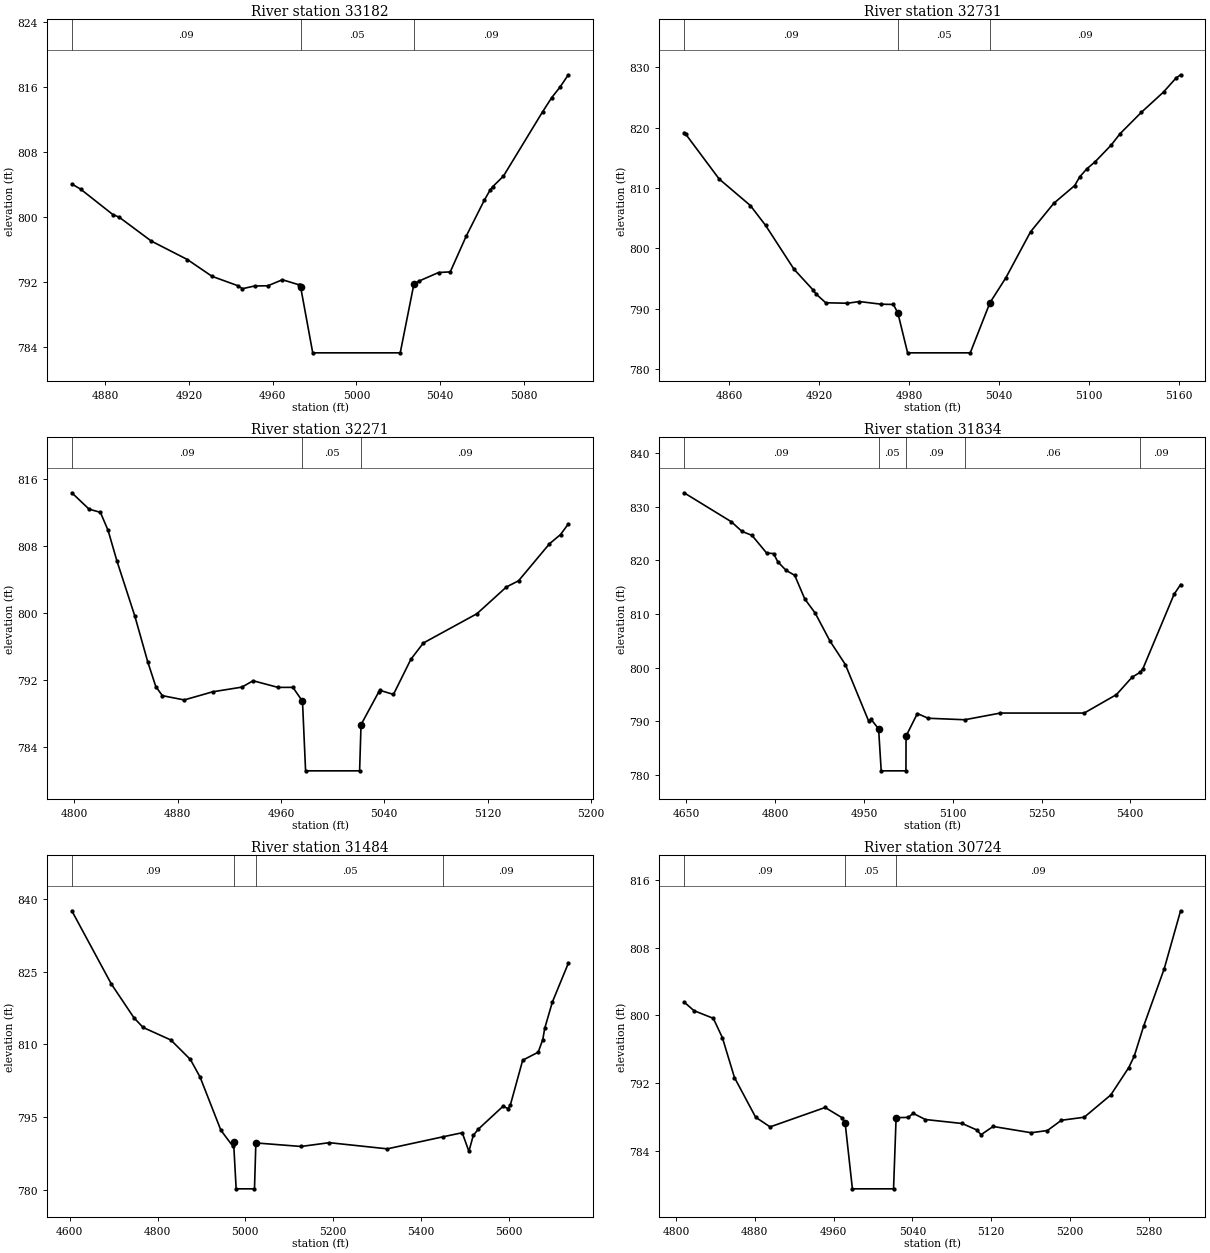
Type RM Length L Ch R = 1 ,33182   ,451,451,451
BEGIN DESCRIPTION:
Mtn_Crk-61.0
END DESCRIPTION:
XS GIS Cut Line= 5
      1100219.61       606058.21       1100120.1       606020.89
      1100082.78       606000.16      1100043.39       605998.08
       1099995.7       606008.45
#Sta/Elev= 30
    4864   804.1  4868.2  803.47  4883.6  800.34  4886.6  800.02    4902  797.07
  4919.2   794.8    4931  792.73  4943.4  791.57  4945.5  791.21  4951.3  791.54
  4957.7  791.57  4964.6  792.31  4972.4   791.7  4972.9  791.65  4973.3  791.45
  4979.1  783.31  5020.9  783.31  5027.4  791.74  5029.8  792.14  5039.2   793.2
  5044.8  793.28  5052.4  797.67  5061.1  802.12  5063.8  803.34    5065  803.75
  5070.2  805.07  5088.9  812.99  5093.3  814.75  5097.2  816.02  5101.2  817.55
#Mann= 3 ,-1 , 0
    4864     .09       0  4973.3     .05       0  5027.4     .09       0
Bank Sta=4973.3,5027.4
Exp/Cntr=0.3,0.1

Type RM Length L Ch R = 1 ,32731   ,460,460,460
BEGIN DESCRIPTION:
Mtn_Crk-60.0
END DESCRIPTION:
XS GIS Cut Line= 5
      1100333.64       605639.42      1100254.86        605602.1
      1100163.64         605571.      1100103.51       605554.41
      1100018.51       605560.63
#Sta/Elev= 30
    4830  819.17  4831.1  818.92  4853.4   811.5  4874.2  807.11  4884.4  803.81
  4903.3  796.57    4916  793.14  4918.2  792.42  4924.5  791.01    4939  790.93
  4946.9  791.21  4961.5  790.77  4969.6  790.73  4972.6  789.33  4979.1  782.72
  5020.9  782.72    5034     791  5044.7  795.17  5061.1  802.75  5076.6  807.47
  5090.6  810.42  5093.9  811.85  5098.7  813.19  5104.2  814.35  5114.9  817.11
  5120.8  818.99  5135.1  822.55  5149.8  825.89    5158  828.17  5161.2  828.75
#Mann= 3 ,-1 , 0
    4830     .09       0  4972.6     .05       0    5034     .09       0
Bank Sta=4972.6,5034
Exp/Cntr=0.3,0.1

Type RM Length L Ch R = 1 ,32271   ,437,437,437
BEGIN DESCRIPTION:
Mtn_Crk-59.0
END DESCRIPTION:
XS GIS Cut Line= 5
      1100460.11       605179.16      1100393.76       605143.92
      1100288.03       605127.33      1100246.56       605123.19
      1100091.07       605162.58
#Sta/Elev= 30
  4798.2  814.31  4811.6  812.35  4820.3  811.98  4826.3  809.81  4833.1  806.18
    4847  799.58  4856.9  794.17  4863.2  791.18  4868.3   790.1  4885.2  789.59
  4907.2  790.56  4929.8  791.12  4938.5  791.88  4957.7  791.09  4969.3  791.09
  4976.7  789.43  4979.1  781.13  5020.9  781.13    5022  786.64  5035.8  790.57
  5036.9  790.72  5047.1  790.25  5060.6  794.45  5070.2  796.38  5111.7  799.88
  5134.5  803.07  5143.9  803.81  5167.8  808.22  5176.4  809.33  5182.4  810.59
#Mann= 3 ,-1 , 0
  4798.2     .09       0  4976.7     .05       0    5022     .09       0
Bank Sta=4976.7,5022
Exp/Cntr=0.3,0.1

Type RM Length L Ch R = 1 ,31834   ,350,350,350
BEGIN DESCRIPTION:
Mtn_Crk-58.0
END DESCRIPTION:
XS GIS Cut Line= 6
      1100799.23       604798.81      1100488.28        604770.1
      1100439.37       604733.42      1100136.68       604741.71
      1100053.75       604766.59      1099983.27       604795.62
#Sta/Elev= 30
    4646  832.61  4725.8  827.21  4743.9   825.4  4760.7  824.67  4785.5  821.37
  4797.2  821.27  4804.3  819.75  4818.3  818.14    4833  817.21  4849.9  812.81
  4867.6  810.16  4892.4  804.98  4918.6  800.55  4957.9  790.02  4962.1  790.33
  4974.7  788.57  4979.1  780.74  5020.9  780.74  5021.1  787.22  5040.2  791.43
  5058.4  790.55  5120.3  790.27  5180.5  791.52  5322.2  791.52  5376.7  794.97
  5402.9  798.19  5416.7  799.13  5421.3  799.78  5473.9  813.65    5485   815.5
#Mann= 5 ,-1 , 0
    4646     .09       0  4974.7     .05       0  5021.1     .09       0
  5120.3     .06       0  5416.7     .09       0
Bank Sta=4974.7,5021.1
Exp/Cntr=0.3,0.1

Type RM Length L Ch R = 1 ,31484   ,760,760,760
BEGIN DESCRIPTION:
Mtn_Crk-57.0
END DESCRIPTION:
XS GIS Cut Line= 6
      1100961.88       604315.64      1100654.99       604426.58
      1100588.64       604428.66      1100229.98       604260.73
      1100118.02        604231.7      1099894.12       604233.78
#Sta/Elev= 30
  4604.5  837.52  4694.6  822.43  4746.2  815.47    4767  813.48  4830.2   810.9
  4874.8  806.88  4896.8  803.27  4944.3   792.3  4970.9  789.09  4973.2  789.96
  4979.1  780.23  5020.9  780.23    5024  789.69  5126.9  788.96  5191.4  789.74
  5323.6  788.47  5451.4  790.97  5494.4  791.79  5509.6  787.95  5519.6  791.25
  5531.1  792.53  5587.5  797.25  5598.7  796.76  5603.9  797.45  5632.2  806.73
  5667.5  808.38    5678  810.99  5682.4   813.3  5699.8  818.71  5736.2   826.7
#Mann= 4 ,-1 , 0
  4604.5     .09       0  4973.2     .05       0    5024     .05       0
  5451.4     .09       0
Bank Sta=4973.2,5024
Exp/Cntr=0.3,0.1

Type RM Length L Ch R = 1 ,30724   ,407,407,407
BEGIN DESCRIPTION:
Mtn_Crk-56.0
END DESCRIPTION:
XS GIS Cut Line= 6
      1100698.53       603740.35      1100596.94       603692.67
      1100505.72       603690.59      1100462.18       603692.67
      1100265.22       603692.67      1100207.17       603676.08
#Sta/Elev= 30
  4808.1  801.58  4818.2  800.56  4837.8  799.66    4847  797.38  4859.3  792.67
  4880.8  787.99  4895.5  786.85  4951.4  789.14  4968.6  787.93  4971.7  787.33
  4979.1  779.54  5020.9  779.54  5023.5  787.94  5035.9  787.97  5040.8  788.45
  5053.2  787.72  5090.6  787.25  5105.4  786.49  5109.8  785.93  5122.1   786.9
  5160.7  786.16  5177.2  786.42  5191.4  787.63  5214.6  787.99  5241.6  790.62
  5259.8  793.84  5265.4  795.19    5275  798.75  5295.9  805.52  5312.5  812.35
#Mann= 3 ,-1 , 0
  4808.1     .09       0  4971.7     .05       0  5023.5     .09       0
Bank Sta=4971.7,5023.5
Exp/Cntr=0.3,0.1

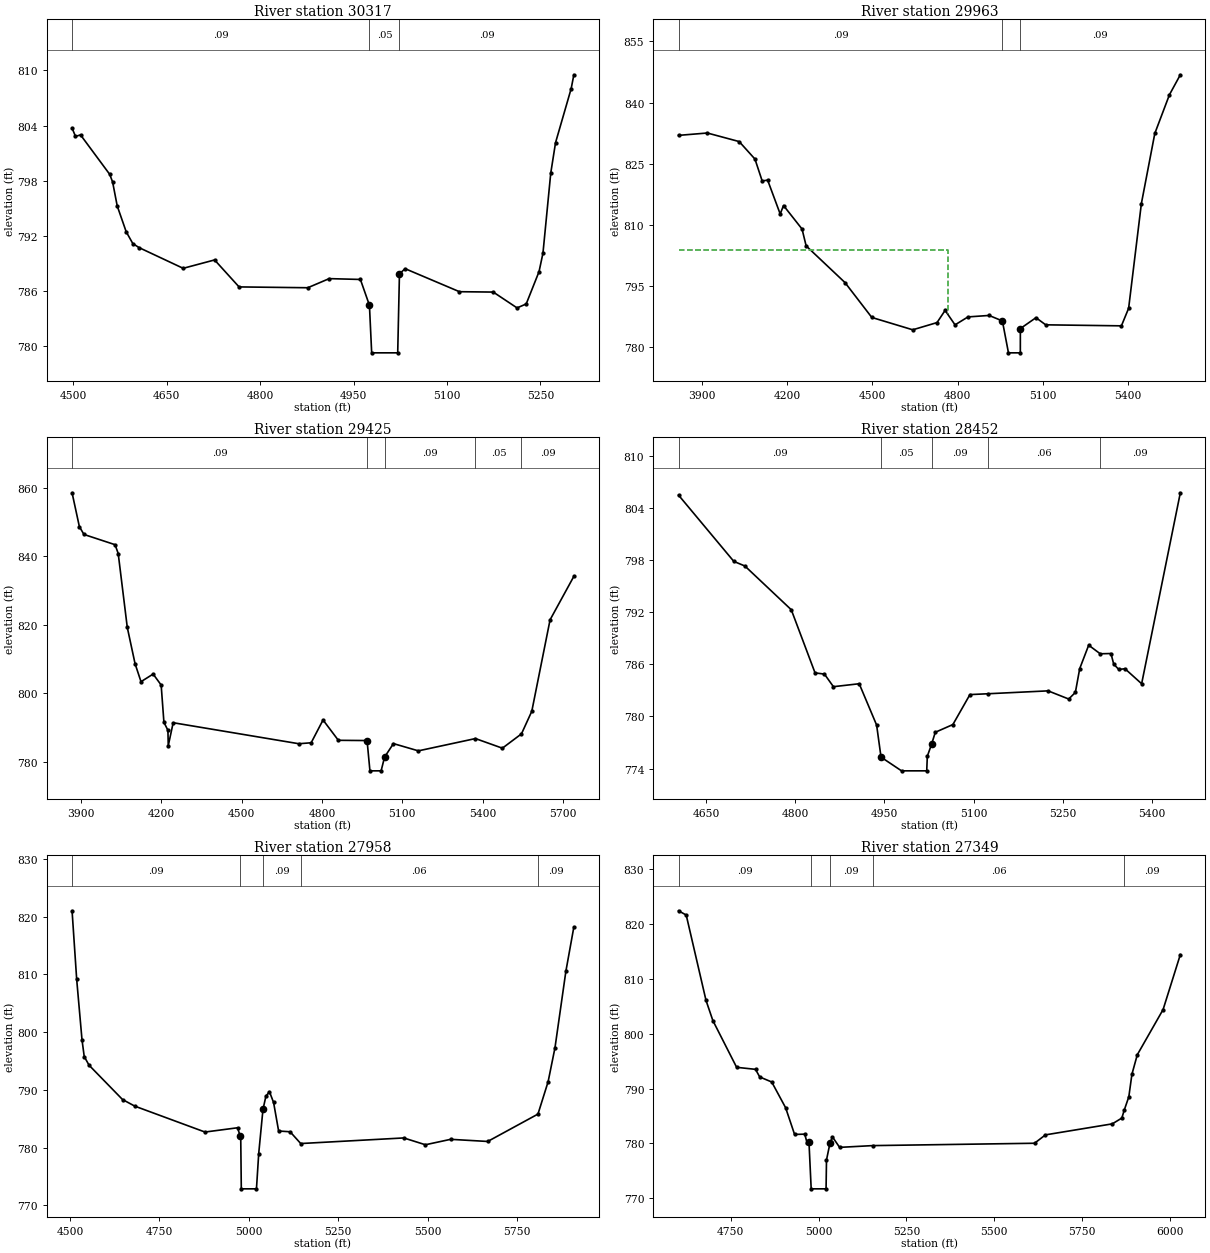
Type RM Length L Ch R = 1 ,30317   ,354,354,354
BEGIN DESCRIPTION:
Mtn_Crk-55.0
END DESCRIPTION:
XS GIS Cut Line= 5
       1100932.8       603522.66      1100752.43       603373.39
      1100489.13       603288.39      1100377.18       603282.17
      1100194.73       603290.46
#Sta/Elev= 30
  4498.1  803.72  4503.6  802.82  4511.7  802.98  4558.6  798.69  4563.2  797.86
  4570.6  795.26    4585  792.46  4595.6  791.18  4605.6  790.74  4676.5  788.49
  4726.9   789.4  4766.2  786.47  4876.5  786.38  4910.9  787.37    4961  787.28
  4975.5  784.48  4979.1  779.31  5020.9  779.31  5023.7  787.89  5032.8  788.45
    5120  785.95  5174.3  785.91  5212.5  784.19  5227.2  784.62  5247.8  788.13
  5254.1  790.14  5266.6  798.83  5274.3  802.14  5299.4  808.01  5303.7  809.51
#Mann= 3 ,-1 , 0
  4498.1     .09       0  4975.5     .05       0  5023.7     .09       0
Bank Sta=4975.5,5023.7
Exp/Cntr=0.3,0.1

Type RM Length L Ch R = 1 ,29963   ,538,538,538
BEGIN DESCRIPTION:
Mtn_Crk-53.0
END DESCRIPTION:
XS GIS Cut Line= 6
      1101808.61       603052.72      1101067.12       602966.62
      1100675.72       603002.28      1100588.64       603047.89
      1100534.74       603062.41      1100067.31       603138.83
#Sta/Elev= 30
  3816.9  831.95  3918.3  832.53  4030.5  830.43  4086.1  826.14  4111.5  820.78
  4130.8  820.97    4175  812.67  4186.7  814.75    4252  808.98  4266.4  804.85
  4403.3  795.85  4497.7   787.3  4641.9  784.27  4727.5  786.04  4755.9  789.03
  4790.9  785.48  4836.5  787.43  4910.9  787.79  4957.7  786.44  4979.1  778.62
  5020.9  778.62    5021  784.57    5076  787.24  5110.3  785.49    5377  785.24
  5402.4  789.55  5447.3  815.22  5494.6  832.42  5546.2  841.92  5584.5  846.81
#Mann= 3 ,-1 , 0
  3816.9     .09       0  4957.7     .05       0    5021     .09       0
#XS Ineff= 2 , 0
       0 4764.66  803.82               0
Permanent Ineff=
       F       F
Bank Sta=4957.7,5021
Exp/Cntr=0.3,0.1

Type RM Length L Ch R = 1 ,29425   ,973,973,973
BEGIN DESCRIPTION:
mtn crk c
END DESCRIPTION:
XS GIS Cut Line= 3
      1101822.94       602367.16      1100874.18       602544.69
      1099983.62       602358.43
#Sta/Elev= 30
  3866.1  858.53  3893.4  848.63  3910.6  846.35  4026.8  843.36  4038.5  840.78
  4072.4  819.19  4101.5  808.58  4123.7  803.33    4169  805.56    4199  802.35
  4209.3  791.46  4224.3  789.12  4225.5  784.62  4243.9  791.34  4713.5   785.2
  4759.5  785.48  4803.9  792.14  4861.1   786.2  4968.4  786.13  4979.1  777.28
  5020.9  777.28  5033.7  781.28  5066.9  785.24  5160.1  783.12  5373.4  786.71
    5474   783.9  5545.3  788.08  5583.9  794.68  5652.2  821.41  5741.1  834.11
#Mann= 5 ,-1 , 0
  3866.1     .09       0  4968.4     .05       0  5033.7     .09       0
  5373.4     .05       0  5545.3     .09       0
Bank Sta=4968.4,5033.7
Exp/Cntr=0.3,0.1

Type RM Length L Ch R = 1 ,28452   ,494,494,494
BEGIN DESCRIPTION:
Mtn_Crk-52.0
END DESCRIPTION:
XS GIS Cut Line= 6
      1100928.65        601824.7       1100669.5       601801.89
       1100615.6       601801.89       1100522.3       601841.28
      1100275.59       601905.55       1100111.8        601963.6
#Sta/Elev= 30
  4603.6  805.49  4696.6  797.86  4715.2  797.33  4793.3  792.29  4833.3  785.02
  4849.1  784.88  4864.2  783.43  4907.6  783.77  4936.9  779.01  4944.3  775.32
  4978.8  773.74  5021.2  773.74  5022.2  775.42  5029.4  776.81  5035.6  778.18
  5065.2  779.07  5093.9  782.52  5125.1  782.62  5225.4  782.95  5260.1  782.01
  5271.3  782.77  5278.6  785.51  5293.7  788.21  5313.1  787.22  5331.2  787.25
  5335.8  786.03  5344.4  785.41  5354.7   785.5  5382.8  783.77  5447.9  805.76
#Mann= 5 ,-1 , 0
  4603.6     .09       0  4944.3     .05       0  5029.4     .09       0
  5125.1     .06       0  5313.1     .09       0
Bank Sta=4944.3,5029.4
Exp/Cntr=0.3,0.1

Type RM Length L Ch R = 1 ,27958   ,609,609,609
BEGIN DESCRIPTION:
Mtn_Crk-51.0
END DESCRIPTION:
XS GIS Cut Line= 6
      1101113.17       601497.13      1101044.75       601461.88
      1100833.28       601385.17      1100518.16       601387.25
      1099804.97       601366.52      1099736.55       601391.39
#Sta/Elev= 30
  4505.5  821.01  4518.4  809.14  4533.3  798.67  4539.5  795.78    4553  794.28
  4646.6  788.34  4681.1  787.19  4877.3  782.71  4968.2  783.45  4976.1  781.96
  4977.2  781.95  4978.8  772.88  5021.2  772.88  5027.5  778.99  5039.4  786.62
  5047.6   788.9  5057.5   789.7  5069.1  787.83  5083.2  782.89  5115.3  782.76
    5145  780.72  5433.2  781.69  5493.7  780.51  5564.3  781.45  5667.9  781.08
  5808.5  785.82  5836.9  791.42  5856.1   797.3  5886.6  810.55  5908.9  818.21
#Mann= 5 ,-1 , 0
  4505.5     .09       0  4976.1     .05       0  5039.4     .09       0
    5145     .06       0  5808.5     .09       0
Bank Sta=4976.1,5039.4
Exp/Cntr=0.3,0.1

Type RM Length L Ch R = 1 ,27349   ,222,222,222
BEGIN DESCRIPTION:
Mtn_Crk-50.0
END DESCRIPTION:
XS GIS Cut Line= 4
      1101102.64       600993.49       1100816.7       600827.48
       1100731.7       600786.02      1099752.25       601008.04
#Sta/Elev= 30
  4600.9  822.46  4622.8  821.68  4679.2   806.1  4698.7  802.42  4766.4  793.89
  4820.2  793.52  4832.2  792.13  4866.4  791.21  4905.9  786.52  4931.5  781.64
  4960.5  781.69  4967.1  780.09  4972.5  780.25  4978.8  771.71  5021.2  771.71
  5022.4  776.98  5032.6  780.13  5039.5  781.18  5059.8  779.28  5153.9   779.6
    5615  780.03  5646.2  781.56  5836.6  783.57  5863.8  784.63  5870.5  786.05
  5883.7  788.52  5892.5  792.62  5907.8  796.18  5981.3  804.43  6030.4  814.46
#Mann= 5 ,-1 , 0
  4600.9     .09       0  4978.8     .05       0  5032.6     .09       0
  5153.9     .06       0  5870.5     .09       0
Bank Sta=4972.5,5032.6
Exp/Cntr=0.5,0.3

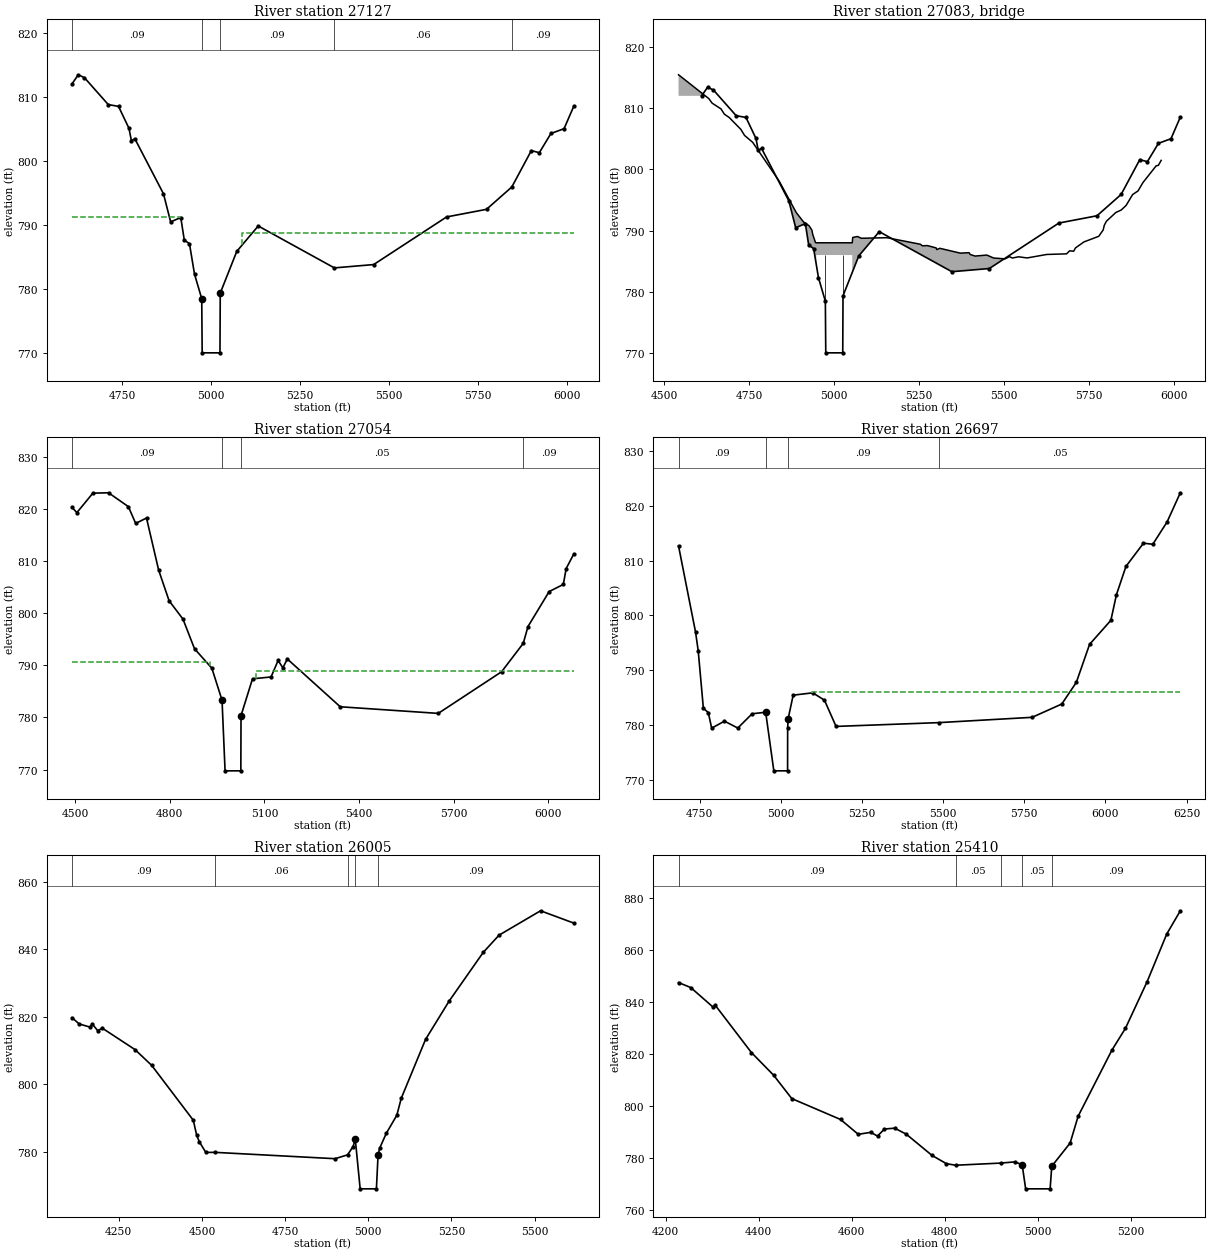
Type RM Length L Ch R = 1 ,27127   ,73,73,73
BEGIN DESCRIPTION:
Maple Creek Rd. SR-1178-US
END DESCRIPTION:
XS GIS Cut Line= 6
      1101003.29       600862.72      1100878.89       600665.77
      1100827.06       600620.16       1100754.5       600607.72
      1100511.94       600638.82      1099772.92        600914.4
#Sta/Elev= 30
  4609.5  812.03  4626.9  813.44  4644.2  812.99  4711.1  808.79    4740   808.5
  4769.4  805.07  4776.1  803.14    4786  803.43  4866.3  794.85  4886.4  790.46
  4914.9  791.14  4924.7  787.63  4939.3  787.05  4953.5  782.29  4973.8  778.45
    4975     770    5025     770  5025.8  779.33  5072.2  785.85  5132.5  789.82
  5346.4  783.27  5456.8  783.79  5661.6  791.23  5773.8  792.42  5844.9  795.91
  5899.7  801.59  5922.2  801.27  5954.8  804.27  5991.7  805.02  6019.2  808.56
#Mann= 5 ,-1 , 0
  4609.5     .09       0  4973.8     .05       0  5025.8     .09       0
  5346.4     .06       0  5844.9     .09       0
#XS Ineff= 2 , 0
       0    4913  791.28    5087       0  788.74
Permanent Ineff=
       F       F
Bank Sta=4973.8,5025.8
Exp/Cntr=0.5,0.3

Type RM Length L Ch R = 3 ,27083   ,,,
BEGIN DESCRIPTION:
Maple Creek Rd. SR-1178
Structure ID: Maple Creek Rd. SR-1178
Approximate Survey Structure
END DESCRIPTION:
Bridge Culvert--1,0,-1,-1, 0
Deck Dist Width WeirC Skew NumUp NumDn MinLoCord MaxHiCord MaxSubmerge Is_Ogee
34,20,3,0, 60, 60, , , , 0, 1,1,,
  4541.4  4630.6  4640.3  4666.4  4676.6  4690.3  4724.9  4735.8  4759.8  4838.1
  4888.1  4909.7  4925.8  4934.3  4936.4  4944.8    4947    4947    5053    5053
  5054.4  5068.3  5079.5  5155.2  5253.7  5259.4  5274.6  5300.1  5302.1  5310.9
    5371  5397.2  5400.3  5414.7  5449.3  5469.5    5503  5516.1  5524.5  5543.1
  5567.9  5625.8  5684.2  5693.2  5705.1  5710.4  5735.3  5778.9    5792  5795.1
  5801.4  5829.2  5845.3  5859.4  5878.7  5894.6    5909  5948.1  5954.4  5962.8
  815.48  811.58  810.84   809.9  809.02  808.51  806.55  805.56  804.43  798.06
  792.94   791.4  790.79  790.05  789.41  788.03     788     788     788     788
  788.87  789.03  788.74  788.83  787.76  787.51  787.54  787.16  786.89   787.1
  786.31  786.38  786.09  785.83  785.99  785.51  785.37  785.73  785.51  785.71
  785.52  786.09  786.19  786.69  786.62  787.16  788.14  789.06   790.1  790.84
  791.52  792.95  793.37   794.1  795.89  796.48  797.84  800.59  800.66  801.48
     748     748     748     748     748     748     748     748     748     748
     748     748     748     748     748     748     748     786     786     748
     748     748     748     748     748     748     748     748     748     748
     748     748     748     748     748     748     748     748     748     748
     748     748     748     748     748     748     748     748     748     748
     748     748     748     748     748     748     748     748     748     748
  4541.4  4630.6  4640.3  4666.4  4676.6  4690.3  4724.9  4735.8  4759.8  4838.1
  4888.1  4909.7  4925.8  4934.3  4936.4  4944.8    4947    4947    5053    5053
  5054.4  5068.3  5079.5  5155.2  5253.7  5259.4  5274.6  5300.1  5302.1  5310.9
    5371  5397.2  5400.3  5414.7  5449.3  5469.5    5503  5516.1  5524.5  5543.1
  5567.9  5625.8  5684.2  5693.2  5705.1  5710.4  5735.3  5778.9    5792  5795.1
  5801.4  5829.2  5845.3  5859.4  5878.7  5894.6    5909  5948.1  5954.4  5962.8
  815.48  811.58  810.84   809.9  809.02  808.51  806.55  805.56  804.43  798.06
  792.94   791.4  790.79  790.05  789.41  788.03     788     788     788     788
  788.87  789.03  788.74  788.83  787.76  787.51  787.54  787.16  786.89   787.1
  786.31  786.38  786.09  785.83  785.99  785.51  785.37  785.73  785.51  785.71
  785.52  786.09  786.19  786.69  786.62  787.16  788.14  789.06   790.1  790.84
  791.52  792.95  793.37   794.1  795.89  796.48  797.84  800.59  800.66  801.48
     748     748     748     748     748     748     748     748     748     748
     748     748     748     748     748     748     748     786     786     748
     748     748     748     748     748     748     748     748     748     748
     748     748     748     748     748     748     748     748     748     748
     748     748     748     748     748     748     748     748     748     748
     748     748     748     748     748     748     748     748     748     748
Pier Skew, UpSta & Num, DnSta & Num=  ,4973.5, 2 ,4973.5, 2 , 0 , 0 , 0 ,0,0
       1       1
  778.51     786
       1       1
  771.87     786
Pier Skew, UpSta & Num, DnSta & Num=  ,5026.5, 2 ,5026.5, 2 , 0 , 0 , 0 ,0,0
       1       1
  779.44     786
       1       1
  780.59     786
Abutment Skew #Up #Dn= , 2 , 2
    4947  4948.5
     786  783.97
    4947  4948.5
     786  786.67
Abutment Skew #Up #Dn= , 2 , 2
  5051.5    5053
  783.08     786
  5051.5    5053
  786.23     786
BR Coef= 1 , 1 , 0 ,1.25, 0 ,,,0.8,0,2,0,
WSPro=,,,, 1 ,,,, 0 ,,,, 0 ,,,,-1 ,-1 ,-1 , 0 , 0 , 0 , 0 , 0
BC Design=,, 0 ,, 0 ,,,,,,
BC HTab HWMax=813.44

Type RM Length L Ch R = 1 ,27054   ,357,357,357
BEGIN DESCRIPTION:
Maple Creek Rd. SR-1178-DS
END DESCRIPTION:
XS GIS Cut Line= 6
      1101061.76        600858.2      1100887.19       600591.13
      1100814.63       600549.67      1100589.51       600534.08
      1100187.41       600628.73       1099697.3       600863.99
#Sta/Elev= 30
  4489.9  820.29  4505.1  819.28  4555.9  823.02  4605.5  823.09  4668.4  820.43
  4691.6  817.21  4725.9  818.25  4764.4  808.26  4797.5  802.38  4841.6  798.85
  4878.1  793.17  4933.1  789.44  4965.4   783.3    4975  769.75    5025  769.75
  5025.6  780.35    5062   787.4  5120.8  787.76  5143.2  790.92  5158.4   789.5
  5172.3  791.21  5340.2  782.04  5650.9  780.77  5851.8  788.76  5920.5  794.21
  5935.4  797.43  6002.6  804.14  6047.5  805.51  6056.5  808.55  6080.9  811.38
#Mann= 4 ,-1 , 0
  4489.9     .09       0  4965.4     .05       0  5025.6     .05       0
  5920.5     .09       0
#XS Ineff= 2 , 0
       0    4928   790.6    5072       0  788.85
Permanent Ineff=
       F       F
Bank Sta=4965.4,5025.6
Exp/Cntr=0.5,0.3

Type RM Length L Ch R = 1 ,26697   ,692,692,692
BEGIN DESCRIPTION:
Mtn_Crk-49.0
END DESCRIPTION:
XS GIS Cut Line= 6
      1100849.87       600188.93      1100628.04       600182.71
      1100524.37        600253.2      1100460.71       600288.41
      1100405.71       600307.22      1099506.85       600880.79
#Sta/Elev= 30
  4685.3   812.7  4737.8  796.92  4745.9  793.54  4761.8  783.02  4777.1  782.23
  4787.3  779.39  4826.8  780.67  4867.8  779.41    4912  782.02  4953.7   782.3
  4978.8  771.59  5021.2  771.59  5021.4   779.4  5022.9   781.1  5038.4  785.42
  5098.8  785.85  5134.8   784.5  5170.5  779.71  5486.2   780.4  5774.4  781.37
  5865.7   783.8  5910.5  787.75  5951.4  794.71    6017   799.1    6034  803.76
  6063.4  808.95  6117.4   813.2  6146.1     813  6190.1  817.08  6230.9  822.41
#Mann= 4 ,-1 , 0
  4685.3     .09       0  4953.7     .05       0  5022.9     .09       0
  5486.2     .05       0
#XS Ineff= 2 , 0
       0                  5096.9       0     786
Permanent Ineff=
       F       F
Bank Sta=4953.7,5022.9
Exp/Cntr=0.3,0.1

Type RM Length L Ch R = 1 ,26005   ,595,595,595
BEGIN DESCRIPTION:
Mtn_Crk-48.0
END DESCRIPTION:
XS GIS Cut Line= 6
      1101086.25       599546.21      1100733.77       599500.62
      1100694.38       599506.84      1100688.16       599513.06
      1100184.37       599649.89      1099713.31        599991.1
#Sta/Elev= 30
  4109.9  819.75  4131.1   817.9  4162.9  816.98  4171.2  817.81  4186.7  815.93
    4201  816.62  4299.1  810.28  4349.1  805.61  4474.1  789.34  4484.1  784.99
  4491.9  783.01  4511.8  779.79  4539.1  779.81  4900.1  777.93  4937.7  779.07
  4954.3  781.52  4960.9  783.71  4975.6  768.99  5024.4  768.99  5029.3  778.89
  5033.8  780.96  5054.3  785.49  5085.7   790.8  5099.1  795.86  5172.1  813.31
  5242.7  824.64  5345.3   839.1  5392.9  844.22  5517.6  851.45  5617.7  847.79
#Mann= 5 ,-1 , 0
  4109.9     .09       0  4539.1     .06       0  4937.7     .09       0
  4960.9     .05       0  5029.3     .09       0
Bank Sta=4960.9,5029.3
Exp/Cntr=0.3,0.1

Type RM Length L Ch R = 1 ,25410   ,907,907,907
BEGIN DESCRIPTION:
Mtn_Crk-47.0
END DESCRIPTION:
XS GIS Cut Line= 3
      1100622.23       598972.15      1100019.47       599096.53
      1099593.71       599278.31
#Sta/Elev= 30
  4227.7  847.59    4254  845.66  4301.9  838.16  4306.9   838.8  4384.3   820.7
  4431.9  812.01  4471.1     803  4575.9  794.97  4613.9  789.28  4640.8  790.03
  4655.3   788.6  4670.3  791.31  4692.2  791.63  4717.1  789.33  4772.4  781.17
  4803.4  777.99  4823.3  777.39  4920.6  778.22  4950.6  778.68  4966.2  777.58
  4973.7  768.32  5026.3  768.32  5029.8     777  5069.3  785.93  5086.5  796.23
  5158.9  821.57  5188.1  829.98  5234.8  847.95    5277  866.27  5306.1  875.17
#Mann= 5 ,-1 , 0
  4227.7     .09       0  4823.3     .05       0  4920.6     .09       0
  4966.2     .05       0  5029.8     .09       0
Bank Sta=4966.2,5029.8
Exp/Cntr=0.3,0.1

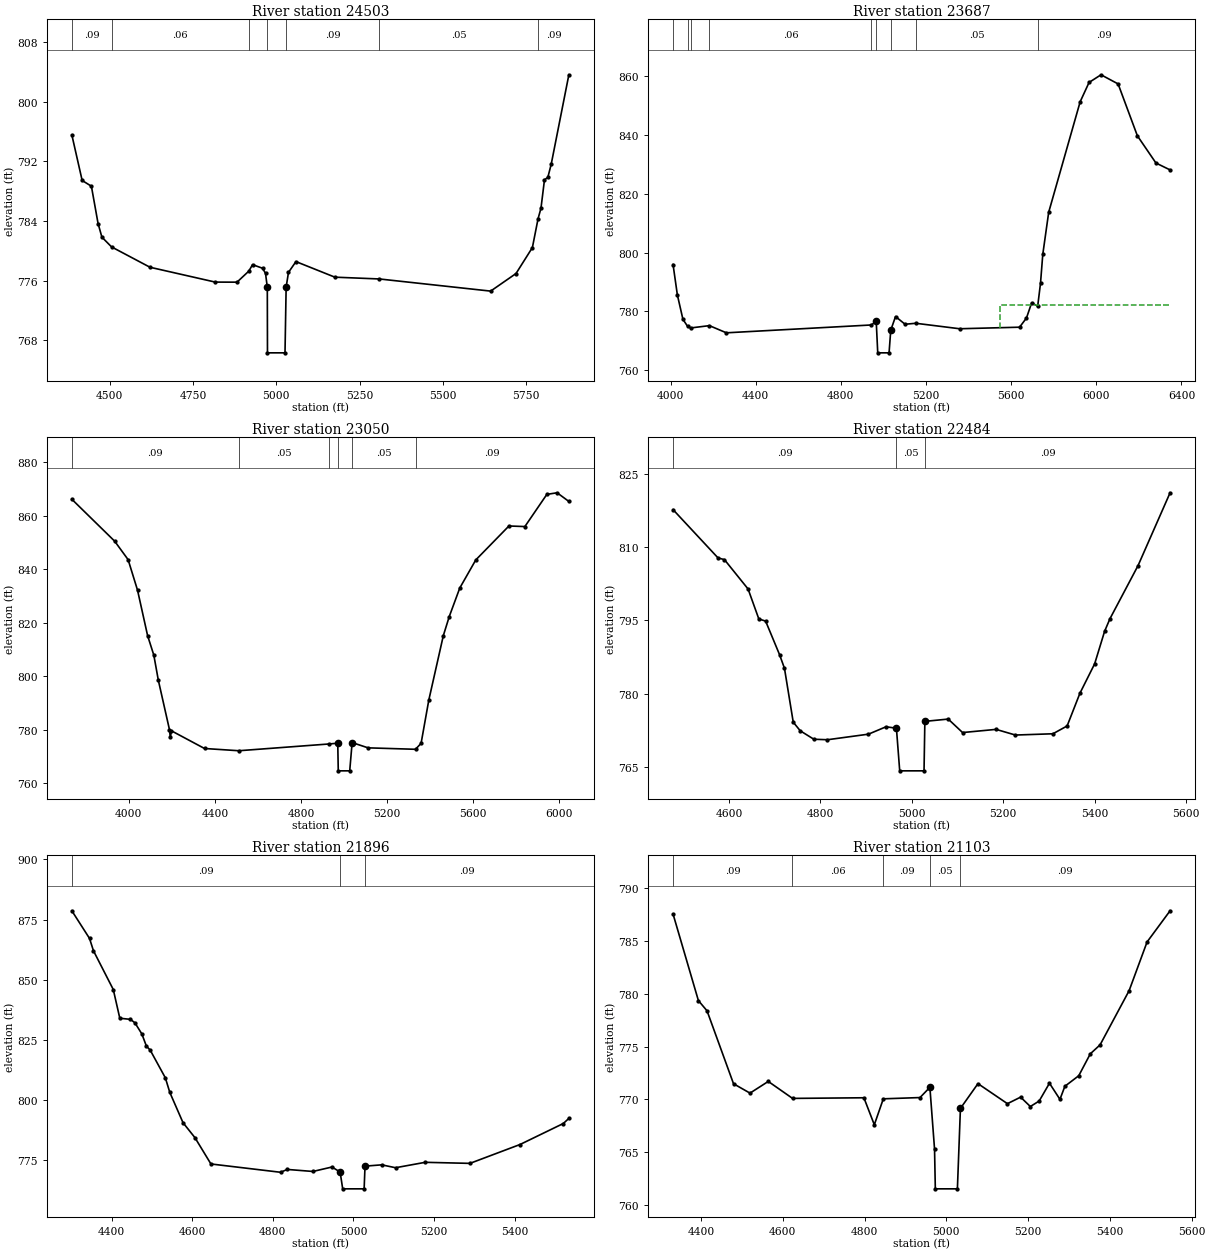
Type RM Length L Ch R = 1 ,24503   ,816,816,816
BEGIN DESCRIPTION:
Mtn_Crk-46.0
END DESCRIPTION:
XS GIS Cut Line= 6
      1100256.93       598453.65      1099798.75        598271.2
      1099651.55        598302.3      1099236.91       598314.74
      1098994.34       598372.79      1098886.53       598515.84
#Sta/Elev= 30
  4386.8  795.56  4417.8  789.44  4445.5  788.67  4465.5  783.67    4477  781.84
    4506  780.53  4621.3   777.8  4817.1  775.81  4882.3   775.8  4917.7  777.28
  4928.9  778.15  4958.8  777.67  4967.8  776.99  4973.2  775.12  4973.7  766.32
  5026.3  766.32  5029.7  775.13  5036.7  777.11  5059.1  778.56  5175.9  776.47
  5309.3  776.23  5643.2   774.6  5719.3  776.96  5768.4  780.44  5785.4   784.3
  5794.2  785.73  5804.7  789.54  5814.7  789.85  5824.9  791.63  5877.8  803.62
#Mann= 7 ,-1 , 0
  4386.8     .09       0    4506     .06       0  4917.7     .09       0
  4973.2     .05       0  5029.7     .09       0  5309.3     .05       0
  5785.4     .09       0
Bank Sta=4973.2,5029.7
Exp/Cntr=0.3,0.1

Type RM Length L Ch R = 1 ,23687   ,637,637,637
BEGIN DESCRIPTION:
Mtn_Crk-45.0
END DESCRIPTION:
XS GIS Cut Line= 6
      1100675.72       597813.02       1100522.3       597717.65
      1100113.88        597605.7      1099695.09       597539.36
      1099087.64       597555.94      1098426.47        597776.2
#Sta/Elev= 30
  4011.9  795.93  4032.2  785.58  4058.3  777.29  4079.8  774.95  4094.3  774.36
  4182.6  775.15  4262.4  772.71    4944  775.38  4966.2   776.7  4973.4   765.9
  5026.6   765.9  5034.5  773.58    5057  778.25  5101.7  775.62  5152.3  775.95
  5358.1  774.09  5639.6  774.62    5672  777.74  5696.3  782.88  5724.8  781.79
    5738  789.59  5748.6  799.36  5776.4  813.71  5924.2  851.27    5966  857.84
  6022.2  860.45  6102.5  857.34    6193   839.7  6280.2  830.45  6346.6   828.1
#Mann= 9 ,-1 , 0
  4011.9     .09       0  4079.8     .06       0  4094.3    .032       0
  4182.6     .06       0    4944     .09       0  4966.2     .05       0
  5034.5     .09       0  5152.3     .05       0  5724.8     .09       0
#XS Ineff= 2 , 0
       0                  5548.7       0     782
Permanent Ineff=
       F       F
Bank Sta=4966.2,5034.5
Exp/Cntr=0.3,0.1

Type RM Length L Ch R = 1 ,23050   ,566,566,566
BEGIN DESCRIPTION:
Mtn_Crk-44.0
END DESCRIPTION:
XS GIS Cut Line= 4
      1101258.47       597355.23      1100210.82       597130.39
      1099938.14       596939.04      1099062.71       596709.42
#Sta/Elev= 30
  3735.3  866.23  3934.4  850.54  3996.8  843.64  4040.6  832.21  4087.4  815.21
  4116.3  807.91  4137.3  798.51  4188.9  780.08  4192.9  777.19  4198.2   779.6
  4351.8  772.99  4511.2  772.15  4930.5  774.68    4971  774.97  4973.4  764.63
  5026.6  764.63  5037.8   775.2  5112.1  773.23  5332.4  772.69  5358.3  774.93
  5394.1   791.1  5461.6   815.2  5489.1  822.34  5538.1  833.03  5612.3  843.52
  5766.5  856.23  5840.5  856.01  5942.7  868.06  5990.4  868.65  6044.9  865.41
#Mann= 6 ,-1 , 0
  3735.3     .09       0  4511.2     .05       0  4930.5     .09       0
    4971     .05       0  5037.8     .05       0  5332.4     .09       0
Bank Sta=4971,5037.8
Exp/Cntr=0.3,0.1

Type RM Length L Ch R = 1 ,22484   ,588,588,588
BEGIN DESCRIPTION:
Mtn_Crk-43.0
END DESCRIPTION:
XS GIS Cut Line= 6
      1100875.77        596862.5      1100619.74       596732.88
      1100503.64       596664.46      1100404.13       596577.38
      1100281.81       596461.28       1099981.2       596254.96
#Sta/Elev= 30
  4477.6  817.67    4576  807.78    4590  807.43  4641.7  801.42  4665.2  795.29
  4680.1  794.84  4710.6  787.96  4721.3  785.18  4740.5  774.15  4755.8  772.38
  4785.6  770.65  4815.4  770.55  4905.1  771.69  4943.4   773.2  4966.2  772.91
  4973.4  764.18  5026.6  764.18  5028.4  774.31  5079.5  774.78  5110.9  772.02
  5184.2  772.67  5226.5  771.51  5308.5  771.77  5339.6  773.37  5367.6  780.07
  5399.8  786.09  5421.6  792.76  5433.4  795.35  5494.7   806.2  5564.8  821.12
#Mann= 3 ,-1 , 0
  4477.6     .09       0  4966.2     .05       0  5028.4     .09       0
Bank Sta=4966.2,5028.4
Exp/Cntr=0.3,0.1

Type RM Length L Ch R = 1 ,21896   ,793,793,793
BEGIN DESCRIPTION:
Mtn_Crk-42.0
END DESCRIPTION:
XS GIS Cut Line= 6
       1101397.2       596484.58      1101077.92       596274.69
      1100818.77        596181.4      1100771.09       596129.57
      1100642.55       596075.67      1100277.66       596071.52
#Sta/Elev= 30
    4301  878.67  4344.9  867.19  4354.7  862.05  4403.9  845.95  4420.1  834.02
  4446.3  833.57  4457.6  832.13  4474.8  827.51  4486.1  822.45  4495.5  820.79
  4533.1  809.28  4544.2  803.22    4577  790.63  4606.7  784.39  4646.3  773.48
  4819.2  770.03  4835.8  771.21  4899.4  770.37  4946.8  772.22    4967  770.13
  4973.4  763.15  5026.6  763.15  5028.8  772.58  5070.3  773.12  5104.6  771.92
  5178.2  774.17  5289.3  773.73  5413.6  781.57    5521  790.29  5534.8  792.41
#Mann= 3 ,-1 , 0
    4301     .09       0    4967     .05       0  5028.8     .09       0
Bank Sta=4967,5028.8
Exp/Cntr=0.3,0.1

Type RM Length L Ch R = 1 ,21103   ,309,309,309
BEGIN DESCRIPTION:
Mtn_Crk-40.0
END DESCRIPTION:
XS GIS Cut Line= 6
      1101639.77       595619.56      1101007.43       595526.26
      1100837.43       595517.97      1100686.09        595453.7
       1100522.3       595472.36      1100451.81       595445.41
#Sta/Elev= 30
  4331.5  787.57  4393.5  779.36  4414.6  778.39  4479.4  771.47  4519.7  770.58
  4564.4  771.69  4623.8  770.08  4798.3  770.14  4823.8  767.58  4845.8  770.04
  4935.5  770.16  4959.7  771.13  4971.1  765.27    4973   761.5    5027   761.5
  5034.4  769.13  5077.3  771.48  5149.4  769.58  5181.6   770.2  5205.4  769.31
    5227  769.83  5252.2  771.52  5277.8  769.99  5289.9  771.23  5323.8  772.23
  5352.1  774.31    5376  775.16    5447   780.3  5490.9  784.92  5547.2  787.88
#Mann= 5 ,-1 , 0
  4331.5     .09       0  4621.9     .06       0  4845.8     .09       0
  4959.7     .05       0  5034.4     .09       0
Bank Sta=4959.7,5034.4
Exp/Cntr=0.3,0.1