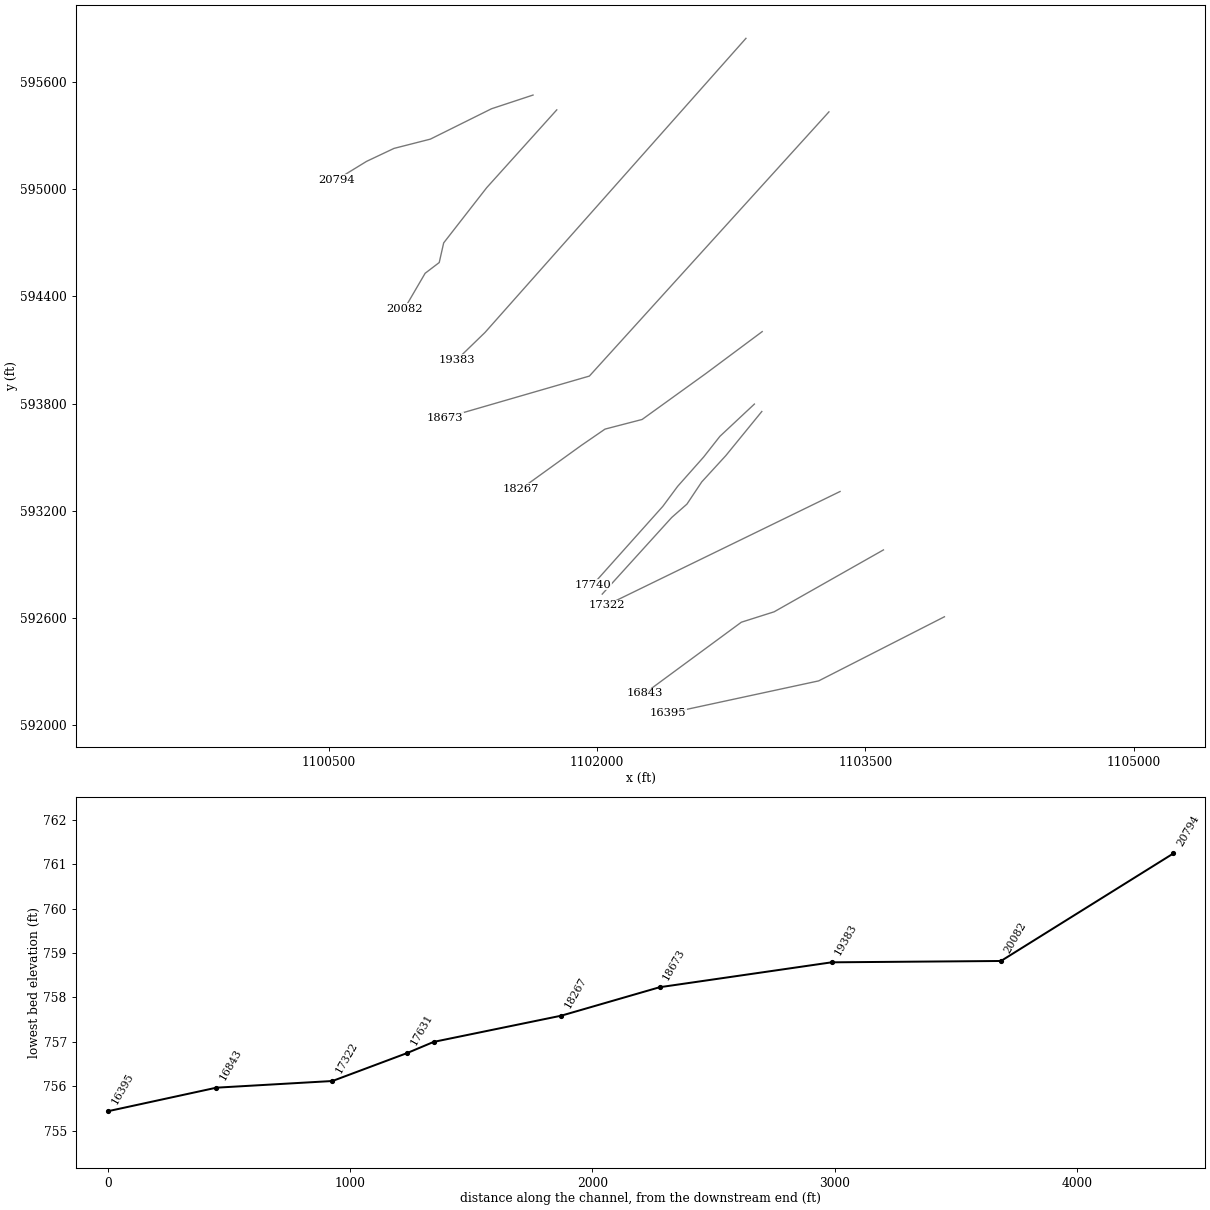
HEC-RAS study lds_mountain_crk.prj: Mountain Creek Limited Detail Study

--- lds_mountain_crk.g01 (geometry) --- (continued)

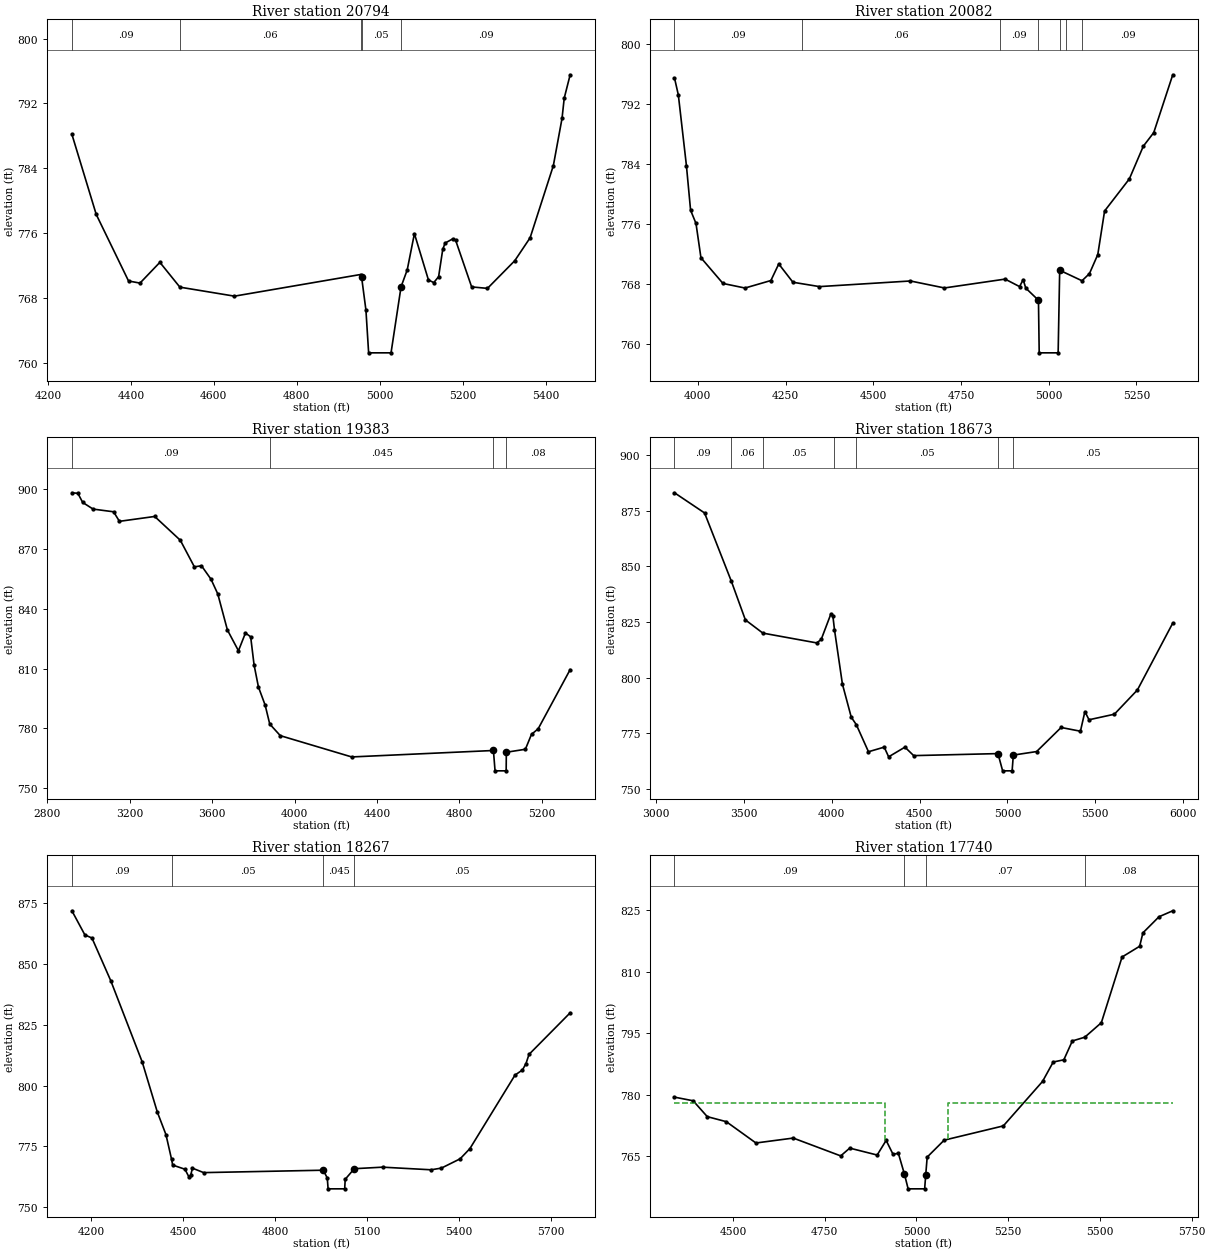
Type RM Length L Ch R = 1 ,20794   ,712,712,712
BEGIN DESCRIPTION:
Mtn_Crk-39.0
END DESCRIPTION:
XS GIS Cut Line= 6
      1101641.84       595526.26      1101409.64       595449.55
      1101067.56       595279.55      1100864.38       595227.72
      1100710.96       595155.16      1100545.11       595053.57
#Sta/Elev= 30
    4258  788.19  4316.7   778.3  4394.5   770.1  4422.1  769.84    4470   772.4
  4518.2  769.34  4649.7  768.23  4953.6   770.9    4956   770.6  4966.5  766.51
    4973  761.24    5027  761.24  5051.1  769.38    5066  771.47  5083.3  775.94
  5117.1  770.23  5129.9   769.9  5141.6  770.63  5151.6     774  5157.3  774.78
  5175.9   775.3  5182.5  775.14  5221.2  769.37  5259.4  769.19  5325.1   772.6
  5362.1  775.43  5418.1  784.33    5439  790.15  5444.3  792.65  5458.6  795.53
#Mann= 5 ,-1 , 0
    4258     .09       0  4518.2     .06       0  4953.6     .09       0
    4956     .05       0  5051.1     .09       0
Bank Sta=4956,5051.1
Exp/Cntr=0.3,0.1

Type RM Length L Ch R = 1 ,20082   ,699,699,699
BEGIN DESCRIPTION:
Mtn_Crk-38.0
END DESCRIPTION:
XS GIS Cut Line= 6
      1101774.52       595443.33      1101382.69       595007.96
      1101142.19       594699.05      1101117.31       594589.17
      1101038.53       594529.05      1100922.43       594330.02
#Sta/Elev= 30
  3933.4  795.47  3944.4   793.2  3967.4  783.79  3979.3  777.83  3994.7  776.07
  4008.8   771.5  4071.6  768.07  4134.4  767.46  4208.2  768.46  4230.6  770.67
    4271  768.23  4346.7  767.65  4605.9   768.4  4702.9  767.47  4875.8  768.65
  4917.1  767.65  4927.3  768.58  4934.7  767.45  4970.9  765.83    4973  758.82
    5027  758.82  5031.4  769.83    5095  768.43  5116.2  769.38    5140  771.92
  5159.4  777.73    5230  782.01  5269.8  786.37  5299.5  788.18  5353.7  795.89
#Mann= 7 ,-1 , 0
  3933.4     .09       0  4297.5     .06       0  4859.9     .09       0
  4970.9     .05       0  5031.4     .09       0    5049     .06       0
    5095     .09       0
Bank Sta=4970.9,5031.4
Exp/Cntr=0.3,0.1

Type RM Length L Ch R = 1 ,19383   ,710,710,710
BEGIN DESCRIPTION:
Mtn_Crk-36.0
END DESCRIPTION:
XS GIS Cut Line= 3
      1102832.34       595843.55      1101373.28       594197.93
      1101215.42       594044.85
#Sta/Elev= 30
  2918.5  898.04  2947.4  897.78    2971  893.19  3021.5  889.87    3121  888.52
  3149.3  883.74  3320.5  886.18    3445  874.25  3513.2  860.94  3547.7  861.49
  3593.9  854.76  3626.8  847.39  3673.6  829.32  3727.2  818.92  3761.2  827.82
  3786.5   825.9    3803  811.87  3824.2  800.78  3856.9  791.67  3879.1  782.23
  3930.3  776.41    4277  765.75  4965.1  768.98    4973  758.79    5027  758.79
  5027.8   768.1  5120.3  769.59    5150  777.07  5182.2  779.82  5337.7  809.49
#Mann= 4 ,-1 , 0
  2918.5     .09       0  3879.1    .045       0  4965.1     .05       0
  5027.8     .08       0
Bank Sta=4965.1,5027.8
Exp/Cntr=0.3,0.1

Type RM Length L Ch R = 1 ,18673   ,406,406,406
BEGIN DESCRIPTION:
Mtn_Crk-35.0
END DESCRIPTION:
XS GIS Cut Line= 3
      1103296.36       595432.15       1101956.9       593953.96
      1101148.44       593719.55
#Sta/Elev= 30
  3104.9  883.02  3276.2  873.96  3428.9  843.26  3508.5  825.97    3608  820.04
  3914.8  815.64  3940.2  817.21  3995.8  828.75  4006.6  827.75  4015.8  821.52
    4061  797.12  4111.2  782.32  4140.2  778.93  4209.2   766.8  4298.9  768.87
    4324  764.52  4416.8  768.86  4466.7  765.06  4946.5  765.97    4973  758.23
    5027  758.23  5033.9   765.3  5166.4  766.88    5306  777.69  5415.9  776.01
  5441.3  784.82  5464.8  781.15  5609.1  783.64  5740.3  794.53  5941.5  824.53
#Mann= 7 ,-1 , 0
  3104.9     .09       0  3428.9     .06       0    3608     .05       0
  4015.8     .09       0  4140.2     .05       0  4946.5    .045       0
  5033.9     .05       0
Bank Sta=4946.5,5033.9
Exp/Cntr=0.3,0.1

Type RM Length L Ch R = 1 ,18267   ,527,527,527
BEGIN DESCRIPTION:
Mtn_Crk-34.0
END DESCRIPTION:
XS GIS Cut Line= 6
      1102923.23       594202.71      1102608.36       593968.24
      1102251.76       593711.16      1102044.44       593657.26
      1101911.76       593566.04       1101574.2        593322.5
#Sta/Elev= 30
  4138.1  871.91  4180.4  861.99  4203.5  860.71  4264.7  843.18  4367.3  809.73
  4416.6  789.12  4444.6  779.89    4463  769.68  4466.5  767.37  4506.5  765.65
  4519.9  762.38  4525.4  763.29    4531  766.09  4567.4  764.26  4957.2  765.25
  4970.3  762.06    4973  757.59    5027  757.59  5028.8  761.53  5058.4  765.87
  5150.5   766.5  5308.6  765.42  5342.3  766.12  5403.1  769.92    5435  774.11
  5582.1  804.36  5606.3  806.46  5617.8  809.07  5627.7  812.86  5761.8  829.96
#Mann= 4 ,-1 , 0
  4138.1     .09       0    4463     .05       0  4957.2    .045       0
  5058.4     .05       0
Bank Sta=4957.2,5058.4
Exp/Cntr=0.5,0.3

Type RM Length L Ch R = 1 ,17740   ,109,109,109
BEGIN DESCRIPTION:
Tryon Rd.-US
END DESCRIPTION:
XS GIS Cut Line= 6
      1102879.56       593797.32      1102686.74       593616.83
      1102595.52       593500.73      1102450.39       593336.95
      1102367.46       593224.99      1101976.04       592786.71
#Sta/Elev= 30
  4340.9  779.38  4391.8  778.49  4430.2  774.62  4482.1  773.39  4562.8  768.19
  4664.5  769.39  4793.8  765.04  4818.4  766.94  4893.1  765.25  4917.6  768.82
  4936.2  765.46  4950.9  765.66  4967.4   760.6  4977.5     757  5022.5     757
  5025.4 760.357  5029.4  764.75  5075.7  768.88  5236.9  772.36  5343.7  783.21
  5372.8  787.95  5401.7  788.49  5424.9  793.09  5458.7     794  5503.9  797.54
  5560.4  813.58  5608.3   816.2  5617.2  819.47    5661   823.4  5698.5  824.86
#Mann= 4 ,-1 , 0
  4340.9     .09       0  4967.4    .045       0  5025.4     .07       0
  5458.7     .08       0
#XS Ineff= 2 , 0
       0    4914     778    5086       0     778
Permanent Ineff=
       F       F
Bank Sta=4967.4,5025.4
Exp/Cntr=0.5,0.3

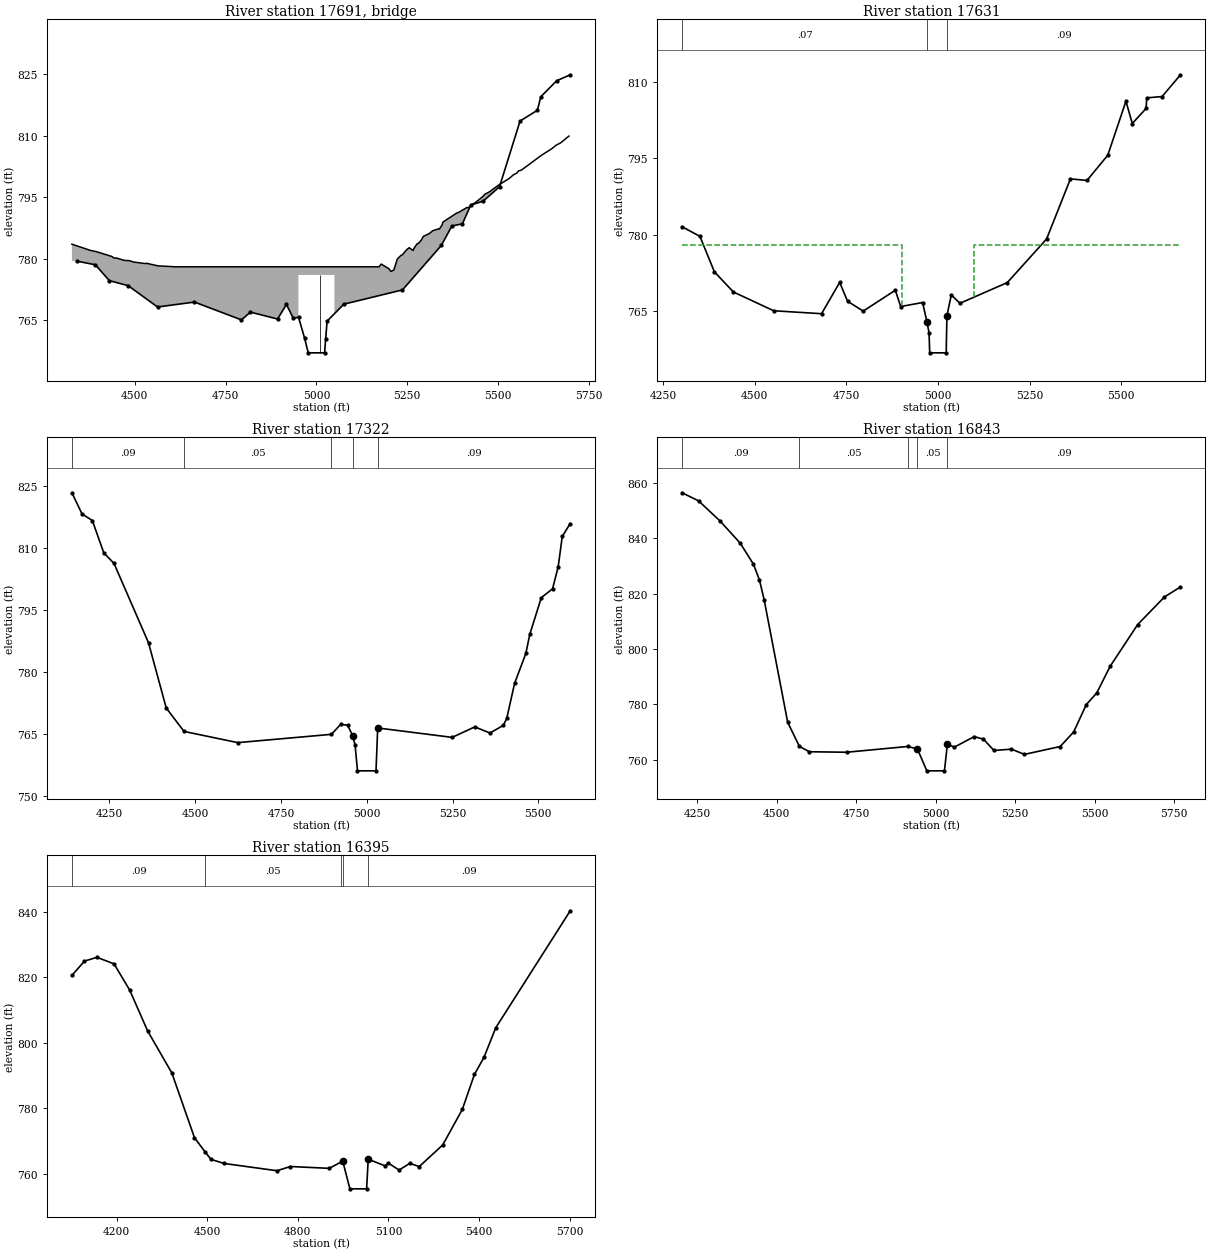
Type RM Length L Ch R = 3 ,17691   ,,,
BEGIN DESCRIPTION:
Tryon Rd.
Structure ID: Tryon Rd.
Approximate Survey Structure
END DESCRIPTION:
Bridge Culvert--1,0,-1,-1, 0
Deck Dist Width WeirC Skew NumUp NumDn MinLoCord MaxHiCord MaxSubmerge Is_Ogee
36.5,25,3,0, 60, 60, , , , 0, 1,1,,
  4327.2  4377.5  4395.1  4436.9    4444  4449.1    4472  4485.5  4496.4  4528.9
  4532.1  4564.3  4611.6  4950.5  4950.5  5049.5  5049.5  5172.5  5178.3  5200.2
    5205  5213.1  5222.4  5223.8  5232.7    5236  5248.5  5255.2  5266.3  5267.8
  5277.4  5280.6  5288.8  5294.3  5310.4  5320.2  5336.6  5338.2  5345.5  5348.2
  5384.9  5392.8  5413.1  5421.1  5428.7  5434.6  5458.2  5463.1    5477  5500.4
  5530.6  5542.3  5550.6  5556.8  5563.6  5618.9  5648.5  5658.6  5672.2  5694.8
  783.52  782.02  781.68  780.53   780.1  780.16  779.55   779.5  779.17  778.78
  778.86  778.23     778     778     778     778     778     778  778.67  777.48
  776.86  777.21  779.83     780  780.78  780.88  782.19  782.66  781.96   782.4
  783.65  783.68  784.54  785.43  786.09  786.81  787.27   787.2  788.15  788.91
  791.06  791.34  792.42  792.54  793.26  793.48  795.17  795.69  796.34  797.89
  799.56  800.46  800.81  801.43  801.56  805.19  806.87  807.61  808.26   809.9
     730     730     730     730     730     730     730     730     730     730
     730     730     730     730     776     776     730     730     730     730
     730     730     730     730     730     730     730     730     730     730
     730     730     730     730     730     730     730     730     730     730
     730     730     730     730     730     730     730     730     730     730
     730     730     730     730     730     730     730     730     730     730
  4327.2  4377.5  4395.1  4436.9    4444  4449.1    4472  4485.5  4496.4  4528.9
  4532.1  4564.3  4611.6  4950.5  4950.5  5049.5  5049.5  5172.5  5178.3  5200.2
    5205  5213.1  5222.4  5223.8  5232.7    5236  5248.5  5255.2  5266.3  5267.8
  5277.4  5280.6  5288.8  5294.3  5310.4  5320.2  5336.6  5338.2  5345.5  5348.2
  5384.9  5392.8  5413.1  5421.1  5428.7  5434.6  5458.2  5463.1    5477  5500.4
  5530.6  5542.3  5550.6  5556.8  5563.6  5618.9  5648.5  5658.6  5672.2  5694.8
  783.52  782.02  781.68  780.53   780.1  780.16  779.55   779.5  779.17  778.78
  778.86  778.23     778     778     778     778     778     778  778.67  777.48
  776.86  777.21  779.83     780  780.78  780.88  782.19  782.66  781.96   782.4
  783.65  783.68  784.54  785.43  786.09  786.81  787.27   787.2  788.15  788.91
  791.06  791.34  792.42  792.54  793.26  793.48  795.17  795.69  796.34  797.89
  799.56  800.46  800.81  801.43  801.56  805.19  806.87  807.61  808.26   809.9
     730     730     730     730     730     730     730     730     730     730
     730     730     730     730     776     776     730     730     730     730
     730     730     730     730     730     730     730     730     730     730
     730     730     730     730     730     730     730     730     730     730
     730     730     730     730     730     730     730     730     730     730
     730     730     730     730     730     730     730     730     730     730
Pier Skew, UpSta & Num, DnSta & Num=  ,5010, 2 ,5010, 2 , 0 , 0 , 0 ,,
       2       2
     757     776
       2       2
     757     776
Abutment Skew #Up #Dn= , 2 , 2
  4950.5    4952
     776  765.32
  4950.5    4952
     776  766.85
Abutment Skew #Up #Dn= , 2 , 2
    5048  5049.5
  765.82     776
    5048  5049.5
  767.35     776
BR Coef= 1 , 1 , 0 ,1.25, 0 ,,,0.8,0,2,0,
WSPro=,,,, 1 ,,,, 0 ,,,, 0 ,,,,-1 ,-1 ,-1 , 0 , 0 , 0 , 0 , 0
BC Design=,, 0 ,, 0 ,,,,,,
BC HTab HWMax=825.11

Type RM Length L Ch R = 1 ,17631   ,309,309,309
BEGIN DESCRIPTION:
Tryon Rd.-DS
END DESCRIPTION:
XS GIS Cut Line= 6
      1102921.01       593755.74      1102719.91       593509.02
      1102585.15       593361.82      1102502.22       593237.43
      1102417.22        593162.8      1102028.66       592734.09
#Sta/Elev= 30
  4302.4  781.55  4350.9  779.67  4390.4  772.68  4442.3  768.72    4552  765.03
  4682.6  764.45  4732.1  770.61  4753.5   766.9  4796.2  764.96  4883.8  769.07
  4898.4  765.86  4958.2  766.65  4969.8  762.91  4975.8  760.68  4977.5  756.75
  5022.5  756.75  5024.5  764.07  5036.5  768.15    5060   766.5  5189.1  770.57
  5296.3  779.15  5361.4  790.98  5406.5  790.67  5463.2  795.64  5512.7  806.26
    5530  801.87  5567.7  804.84  5569.4  806.92  5611.4  807.18  5661.5  811.46
#Mann= 3 ,-1 , 0
  4302.4     .07       0  4969.8     .05       0  5024.5     .09       0
#XS Ineff= 2 , 0
       0    4903     778    5097       0     778
Permanent Ineff=
       F       F
Bank Sta=4969.8,5024.5
Exp/Cntr=0.5,0.3

Type RM Length L Ch R = 1 ,17322   ,479,479,479
BEGIN DESCRIPTION:
Mtn_Crk-33.0
END DESCRIPTION:
XS GIS Cut Line= 2
      1103358.55       593308.14      1102052.58        592671.9
#Sta/Elev= 30
  4140.5  823.44    4170  818.32  4200.1  816.72  4233.4  808.91  4263.3  806.33
  4363.8  787.13  4415.5  771.33  4467.4  765.66  4624.1  762.95  4897.2  764.96
  4923.6  767.35  4944.3  767.18    4959  764.62    4966  762.37    4973  756.12
    5027  756.12  5031.9   766.5    5249  764.22  5314.8  766.76  5359.2  765.28
  5398.2  767.13  5408.1  768.81  5430.9  777.29  5463.7  784.53  5475.2  789.16
  5508.9  798.07  5541.6  800.18  5558.1  805.56  5569.9  812.87  5593.2     816
#Mann= 5 ,-1 , 0
  4140.5     .09       0  4467.4     .05       0  4897.2     .09       0
    4959     .05       0  5031.9     .09       0
Bank Sta=4959,5031.9
Exp/Cntr=0.3,0.1

Type RM Length L Ch R = 1 ,16843   ,448,448,448
BEGIN DESCRIPTION:
mtn crk d
END DESCRIPTION:
XS GIS Cut Line= 4
      1103601.15       592981.37      1102989.98       592635.04
      1102806.63       592576.83      1102265.31       592178.12
#Sta/Elev= 30
  4202.9  856.45  4254.7  853.51  4322.5  846.21  4385.5  838.25  4427.1  830.66
    4446  824.93  4460.7  817.85  4534.8  773.51  4571.6  764.82  4602.8  762.87
  4719.8  762.69    4913  764.78  4942.8  763.85  4972.3  755.97  5027.7  755.97
  5036.9  765.51  5059.3  764.56  5121.3  768.34  5150.5  767.41  5183.5  763.32
  5238.5  763.81    5279  761.91  5391.7  764.76  5433.9  769.99  5473.8   779.9
  5506.7  784.13  5548.8  793.75  5635.4  808.84  5719.4  818.78    5770  822.44
#Mann= 5 ,-1 , 0
  4202.9     .09       0  4571.6     .05       0    4913     .09       0
  4942.8     .05       0  5036.9     .09       0
Bank Sta=4942.8,5036.9
Exp/Cntr=0.3,0.1

Type RM Length L Ch R = 1 ,16395   ,885,885,885
BEGIN DESCRIPTION:
Mtn_Crk-32.0
END DESCRIPTION:
XS GIS Cut Line= 3
      1103942.18       592607.32      1103238.96       592248.53
      1102397.01       592066.75
#Sta/Elev= 30
  4051.5  820.51  4093.2  824.88  4134.3  826.03  4191.1  824.04  4243.1  816.01
  4302.4  803.58  4382.6  790.77  4457.4  771.07    4493  766.65  4512.5  764.41
  4556.1  763.17  4730.9  760.96  4775.1  762.25  4904.2  761.69  4941.8  763.56
  4948.2  764.08  4972.3  755.44  5027.7  755.44  5033.1  764.48  5089.5  762.42
  5099.3   763.3  5135.4  761.17    5171  763.22    5202  762.23  5279.8  768.81
  5344.8  779.66  5384.9  790.33  5416.6  795.54  5455.5  804.55  5702.3  840.22
#Mann= 5 ,-1 , 0
  4051.5     .09       0    4493     .05       0  4941.8     .09       0
  4948.2     .05       0  5033.1     .09       0
Bank Sta=4948.2,5033.1
Exp/Cntr=0.3,0.1