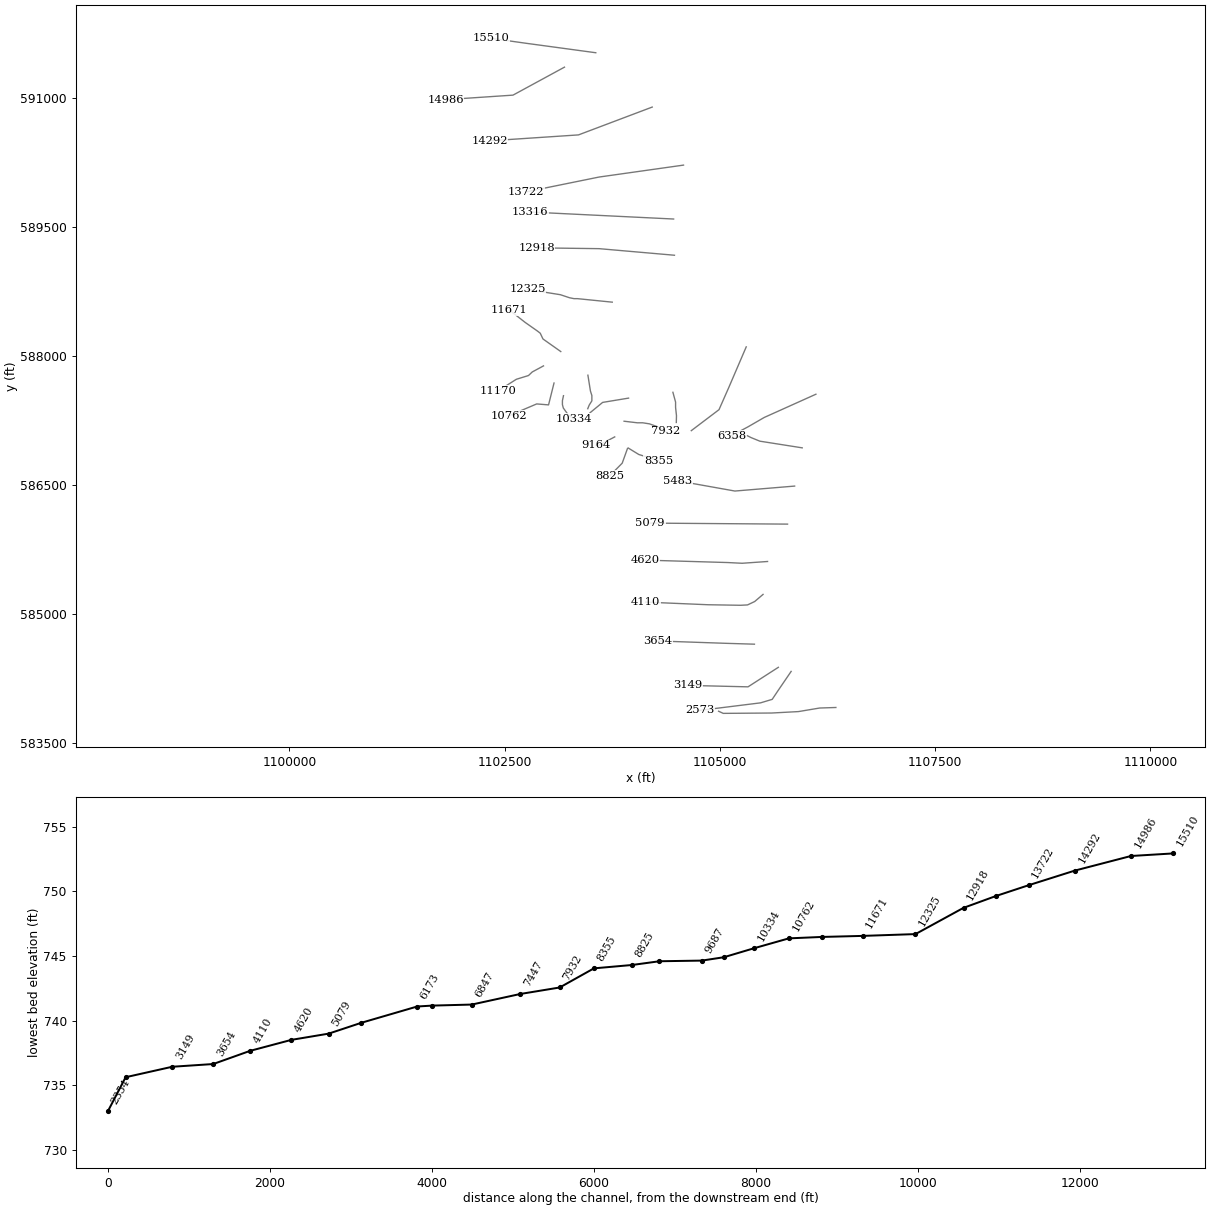
HEC-RAS study lds_mountain_crk.prj: Mountain Creek Limited Detail Study

--- lds_mountain_crk.g01 (geometry) --- (continued)

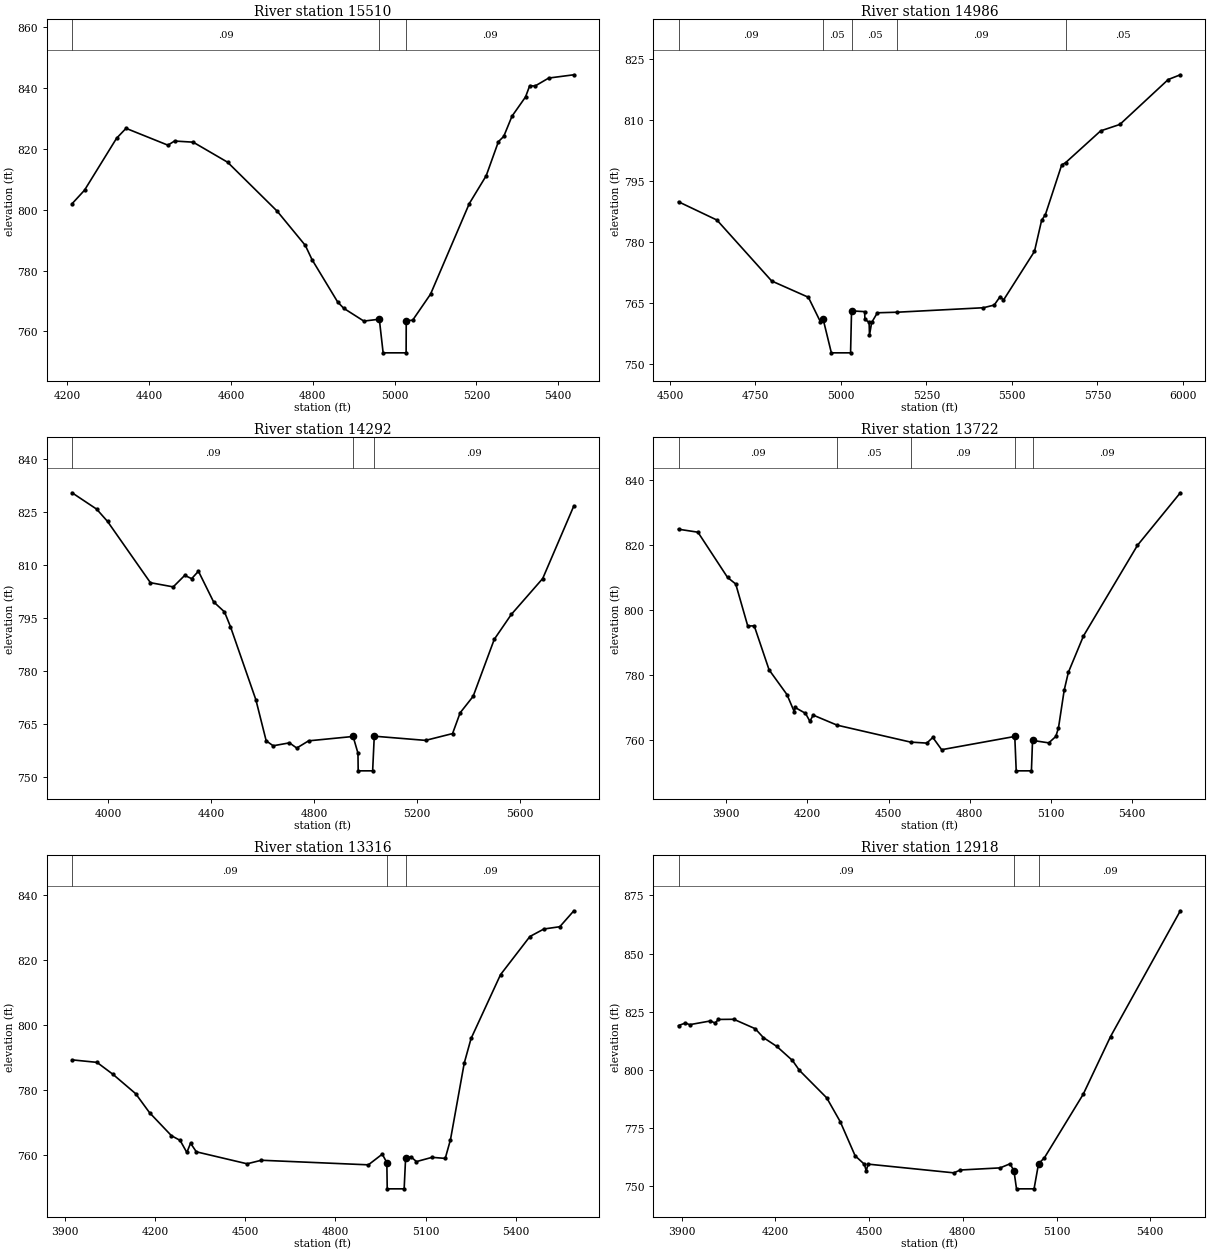
Type RM Length L Ch R = 1 ,15510   ,524,524,524
BEGIN DESCRIPTION:
Mtn_Crk-31.0
END DESCRIPTION:
XS GIS Cut Line= 4
      1103559.47       591526.18      1102867.11       591620.32
       1102759.3       591634.83      1102344.39       591693.61
#Sta/Elev= 30
  4211.6  801.98    4242  806.42  4320.4  823.51  4343.5  826.77  4445.9  821.23
    4462  822.59  4507.6  822.22  4591.8  815.62  4712.9  799.53  4781.7  788.27
  4798.1   783.6  4860.8  769.66  4875.6  767.59  4924.8  763.38  4962.6     764
  4971.9  752.94  5028.1  752.94  5028.4  763.45  5044.2   763.7  5087.8  772.24
  5182.5  802.02  5223.9   811.2  5253.7  822.39  5266.7  824.11  5286.9  830.76
    5320   837.1  5330.2  840.79  5343.1  840.67  5376.6   843.3  5438.1  844.38
#Mann= 3 ,-1 , 0
  4211.6     .09       0  4962.6     .05       0  5028.4     .09       0
Bank Sta=4962.6,5028.4
Exp/Cntr=0.3,0.1

Type RM Length L Ch R = 1 ,14986   ,694,694,694
BEGIN DESCRIPTION:
Mtn_Crk-30.0
END DESCRIPTION:
XS GIS Cut Line= 3
      1103195.91       591358.75      1102597.93       591033.45
      1101813.39       590980.83
#Sta/Elev= 30
  4525.1  789.92  4637.4  785.42  4797.5  770.42  4904.7  766.42  4939.8   760.4
  4947.5  761.02  4947.9  761.03  4971.9  752.74  5028.1  752.74  5030.9  763.07
  5069.2  762.88  5070.1  760.95  5082.3  760.26  5083.4   757.1  5089.8  760.22
  5106.5   762.6  5164.5  762.74  5416.3  763.84  5448.1   764.5  5465.4   766.6
  5475.2  765.72  5565.8  777.72  5586.6  785.34  5597.7  786.76  5645.4     799
  5656.5  799.53  5759.2  807.37  5815.5  808.96  5956.8  820.01  5992.2  821.18
#Mann= 5 ,-1 , 0
  4525.1     .09       0  4947.9     .05       0  5030.9     .05       0
  5164.5     .09       0  5656.5     .05       0
Bank Sta=4947.5,5030.9
Exp/Cntr=0.3,0.1

Type RM Length L Ch R = 1 ,14292   ,570,570,570
BEGIN DESCRIPTION:
Mtn_Crk-29.0
END DESCRIPTION:
XS GIS Cut Line= 3
      1104214.85       590894.72      1103358.46       590571.27
      1102325.26       590502.45
#Sta/Elev= 30
  3859.5  830.41    3955  825.78  3997.3   822.3  4164.1  804.93  4252.7  803.74
  4297.5     807  4324.4  806.07  4350.8  808.18  4409.5  799.52  4452.1  796.65
  4475.2  792.49  4574.2  771.73  4614.2  760.12  4641.3  758.71  4704.6  759.54
    4733  758.07  4779.1  760.11  4952.1  761.35    4971  756.62  4971.9  751.61
  5028.1  751.61  5034.4  761.43  5233.8  760.24  5338.8  762.17  5368.3  768.06
  5418.8  772.72    5501  788.89  5567.3  795.94  5689.3  806.11  5810.4   826.7
#Mann= 3 , 0 , 0
  3859.5     .09       0  4952.1     .05       0  5034.4     .09       0
Bank Sta=4952.1,5034.4
Exp/Cntr=0.3,0.1

Type RM Length L Ch R = 1 ,13722   ,406,406,406
BEGIN DESCRIPTION:
Mtn_Crk-28.0
END DESCRIPTION:
XS GIS Cut Line= 3
      1104578.42       590220.21      1103597.74       590081.48
      1102751.01       589909.26
#Sta/Elev= 30
  3723.9  824.88  3795.6  823.96  3905.1  810.03  3935.3  808.01  3979.7  795.09
  4003.7  795.12  4058.6  781.57  4124.5  773.98  4151.7  768.66  4154.6     770
    4193  768.19  4209.4  765.74  4221.5  767.64  4310.1  764.54  4581.5  759.33
  4641.4  759.02  4663.7  760.76  4696.3  756.99  4966.6  761.07  4971.9  750.48
  5028.1  750.48  5032.2  759.85  5092.2  759.09  5118.2  761.06  5128.1  763.72
  5149.2  775.31  5164.5  780.78  5220.4     792  5420.1  819.93  5578.4   836.1
#Mann= 5 ,-1 , 0
  3723.9     .09       0  4310.1     .05       0  4581.5     .09       0
  4966.6     .05       0  5032.2     .09       0
Bank Sta=4966.6,5032.2
Exp/Cntr=0.3,0.1

Type RM Length L Ch R = 1 ,13316   ,398,398,398
BEGIN DESCRIPTION:
Mtn_Crk-27.0
END DESCRIPTION:
XS GIS Cut Line= 2
      1104463.61       589593.53      1102798.85       589674.86
#Sta/Elev= 30
  3925.1  789.35  4007.8  788.58    4061  784.89  4136.2  778.95  4182.6  773.07
  4255.2     766    4284  764.55  4306.3  760.84  4318.7  763.68  4337.8  761.04
  4506.4  757.35  4553.9  758.44  4909.3  757.03  4955.4  760.32  4970.6  757.72
  4971.9  749.64  5028.1  749.64    5033  759.22    5051  759.47    5069  758.03
  5120.9  759.34  5164.6  759.01    5182  764.79  5227.7  788.35  5250.4  795.93
  5348.2  815.58  5445.8  827.33  5492.3  829.64  5545.1  830.34  5591.8  835.25
#Mann= 3 , 0 , 0
  3925.1     .09       0  4970.6     .05       0    5033     .09       0
Bank Sta=4970.6,5033
Exp/Cntr=0.3,0.1

Type RM Length L Ch R = 1 ,12918   ,593,593,593
BEGIN DESCRIPTION:
Mtn_Crk-26.0
END DESCRIPTION:
XS GIS Cut Line= 3
      1104473.18       589172.56      1103597.74        589249.1
      1102870.61       589258.67
#Sta/Elev= 30
  3890.2  819.01    3912  820.09  3925.9  819.39  3992.5     821  4007.1  820.08
  4017.8  821.64  4067.1  821.71  4135.6  817.65  4161.6  813.85  4204.9  810.01
  4254.9  803.97  4277.1  799.72  4364.4   787.9  4407.9  777.59  4455.4  762.96
  4485.2  759.28  4490.7  756.51  4497.4  759.36  4771.6  755.61  4791.6  756.83
  4919.5  757.75  4951.2  759.51  4963.7  756.49  4971.9  748.73  5028.1  748.73
  5042.4  759.53  5061.3  762.12  5185.2  789.39  5272.8  814.26  5496.2  868.41
#Mann= 3 , 0 , 0
  3890.2     .09       0  4963.7     .05       0  5042.4     .09       0
Bank Sta=4963.7,5042.4
Exp/Cntr=0.3,0.1

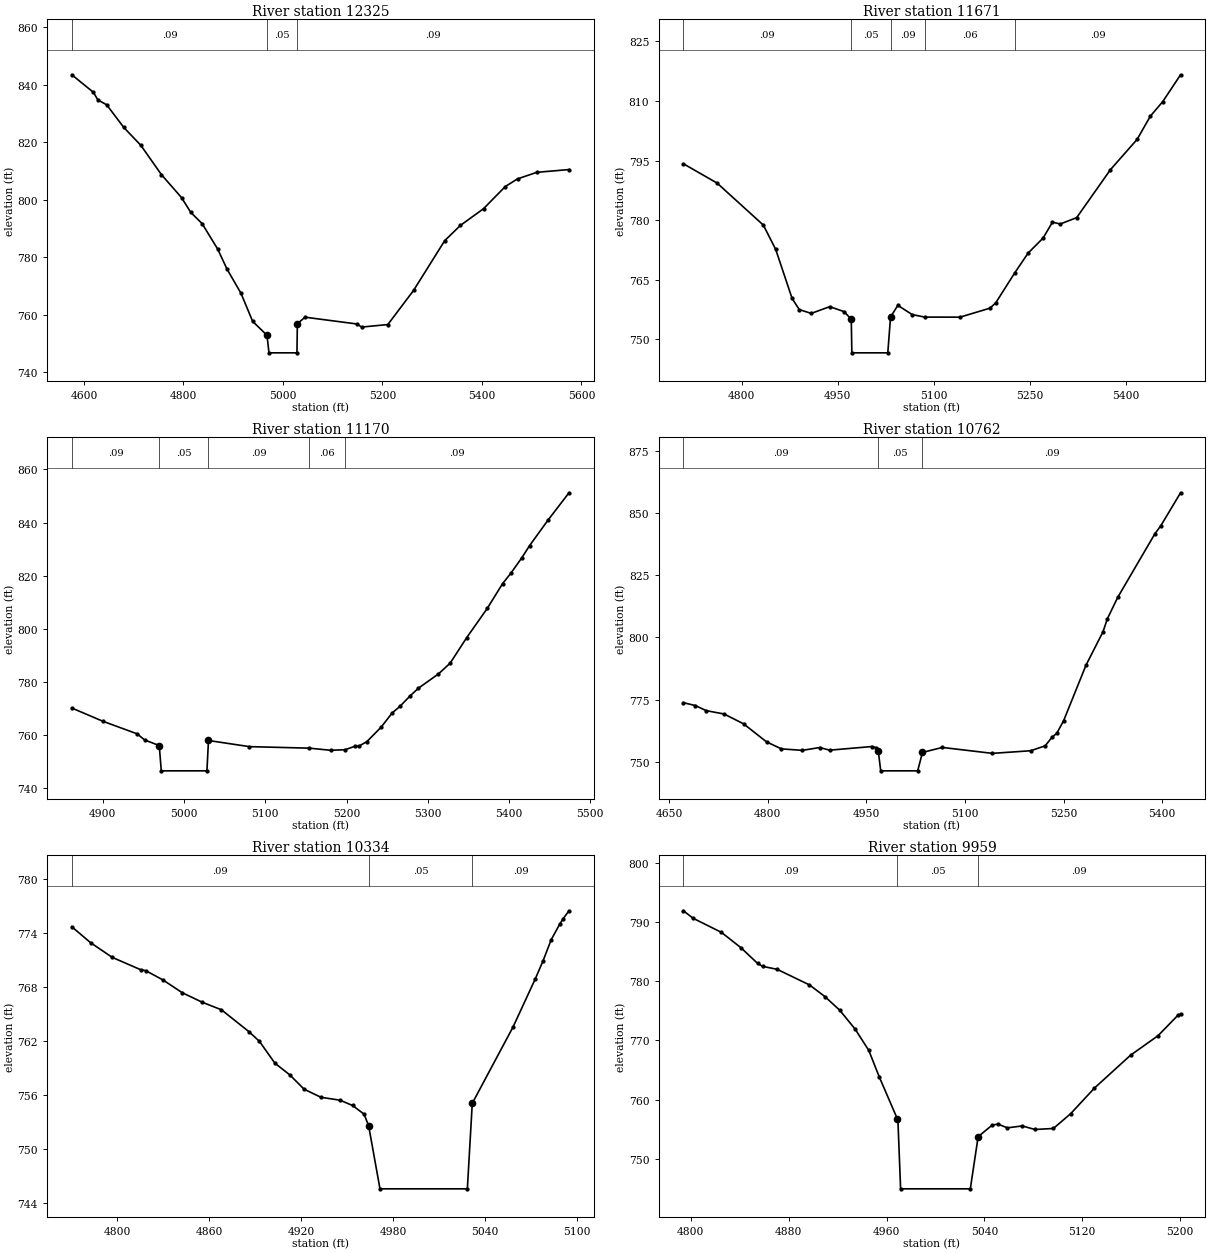
Type RM Length L Ch R = 1 ,12325   ,654,654,654
BEGIN DESCRIPTION:
Mtn_Crk-25.0
END DESCRIPTION:
XS GIS Cut Line= 6
      1103750.82       588627.21      1103346.02       588668.06
      1103306.63       588668.06       1103254.8       588678.43
      1103149.07       588713.67      1102765.36        588775.5
#Sta/Elev= 30
  4575.6  843.48  4618.9  837.38  4627.9  834.74  4645.7  833.02  4679.9  825.17
  4714.3  818.92  4755.8   808.7  4796.1  800.73  4814.7  795.58  4837.5  791.66
  4868.5   782.9  4887.6  775.81  4915.6  767.42    4939  757.66  4967.8  752.82
  4971.9   746.7  5028.1   746.7  5028.9  756.84  5044.3  759.11  5148.8  756.74
    5158  755.67  5210.7  756.54  5262.5  768.43  5325.1  785.75  5356.5  791.03
  5403.1  796.87  5446.7  804.56  5471.4  807.25  5510.3  809.53  5574.9  810.49
#Mann= 3 ,-1 , 0
  4575.6     .09       0  4967.8     .05       0  5028.9     .09       0
Bank Sta=4967.8,5028.9
Exp/Cntr=0.3,0.1

Type RM Length L Ch R = 1 ,11671   ,501,501,501
BEGIN DESCRIPTION:
Mtn_Crk-24.0
END DESCRIPTION:
XS GIS Cut Line= 6
      1103152.85       588053.15      1102945.89       588199.51
      1102914.79       588265.86      1102885.77       588288.66
      1102738.57       588392.32      1102554.88       588536.31
#Sta/Elev= 30
  4708.6  794.18  4761.3  789.31  4833.6  778.73  4852.9  772.61  4878.5  760.26
  4889.7  757.46  4908.4  756.49  4937.3  758.19  4959.7  756.95    4971  755.01
  4971.9  746.56  5028.1  746.56  5032.4  755.58  5043.8  758.52  5066.2   756.2
  5085.8  755.56  5141.1  755.55  5187.8  757.81  5196.8  759.15  5226.2  766.62
  5247.4  771.68  5270.8  775.46  5285.5  779.48  5297.7  779.01  5323.3  780.61
  5376.1  792.69  5417.8  800.32  5438.6  806.19  5457.7   809.8  5485.7  816.59
#Mann= 5 ,-1 , 0
  4708.6     .09       0    4971     .05       0  5032.4     .09       0
  5085.8     .06       0  5226.2     .09       0
Bank Sta=4971,5032.4
Exp/Cntr=0.3,0.1

Type RM Length L Ch R = 1 ,11170   ,408,408,408
BEGIN DESCRIPTION:
Mtn_Crk-23.0
END DESCRIPTION:
XS GIS Cut Line= 5
      1102952.11       587886.46       1102821.5       587815.97
      1102777.96        587774.5      1102636.98       587730.97
      1102420.93       587593.91
#Sta/Elev= 30
  4861.8  770.14  4899.9  765.17  4942.1  760.43  4951.4  758.12  4969.4  756.01
  4971.9  746.48  5028.1  746.48    5030  757.91  5080.3   755.6  5154.3  755.02
  5180.4  754.22  5198.1  754.44  5210.5  755.74  5215.1  755.78    5225  757.49
  5242.5  762.92    5256  768.24  5265.7  770.78  5278.6  774.82  5288.5  777.63
  5313.1  782.99  5327.5  787.04  5347.8  796.63  5373.2  807.69    5392  816.98
  5402.3  820.96  5415.6  826.69  5425.3  831.33  5447.7  840.83  5473.8  851.23
#Mann= 5 ,-1 , 0
  4861.8     .09       0  4969.4     .05       0    5030     .09       0
  5154.3     .06       0  5198.1     .09       0
Bank Sta=4969.4,5030
Exp/Cntr=0.3,0.1

Type RM Length L Ch R = 1 ,10762   ,428,428,428
BEGIN DESCRIPTION:
Mtn_Crk-22.0
END DESCRIPTION:
XS GIS Cut Line= 4
      1103074.43       587687.43      1103010.94       587433.26
      1102873.23       587444.43       1102545.7       587304.86
#Sta/Elev= 30
  4671.8  773.78    4690  772.63  4706.5  770.58  4733.6  769.24  4763.3  765.28
  4798.4  757.99  4820.9   755.2  4852.7  754.61  4879.2  755.75  4894.2  754.68
  4958.6  756.15  4964.4   755.7  4968.1  754.52  4971.9  746.37  5028.1  746.37
  5035.4  753.77  5065.5  755.78  5141.7   753.4  5199.9  754.45  5222.1  756.44
  5232.1  759.79  5239.7  761.49    5250   766.5  5284.2  788.92  5309.8  802.22
  5316.7  807.58  5332.3  816.12  5389.1  841.82  5397.6  844.83  5427.9   858.2
#Mann= 3 , 0 , 0
  4671.8     .09       0  4968.1     .05       0  5035.4     .09       0
Bank Sta=4968.1,5035.4
Exp/Cntr=0.3,0.1

Type RM Length L Ch R = 1 ,10334   ,375,375,375
BEGIN DESCRIPTION:
Mtn_Crk-20.0
END DESCRIPTION:
XS GIS Cut Line= 6
      1103184.31       587540.23      1103171.87       587482.18
      1103171.87       587436.57      1103182.24       587397.18
      1103240.29       587316.32      1103304.56       587270.71
#Sta/Elev= 29
  4770.5  774.72  4782.7  772.96  4796.8  771.33  4815.3  769.96  4818.7  769.85
  4829.9  768.82  4842.6  767.39  4855.7  766.33  4868.1   765.5  4886.1  763.06
  4892.9  761.99  4902.9  759.58  4912.8  758.25    4922  756.68    4933  755.78
  4945.4  755.46  4953.6  754.87  4961.1  753.91  4964.1  752.62  4971.5  745.61
  5028.5  745.61  5031.7  755.11  5058.3  763.59  5072.9  768.97  5077.9  770.95
  5083.2  773.29  5088.7     775  5090.9   775.6  5094.8   776.5
#Mann= 3 ,-1 , 0
  4770.5     .09       0  4964.1     .05       0  5031.7     .09       0
Bank Sta=4964.1,5031.7
Exp/Cntr=0.3,0.1

Type RM Length L Ch R = 1 ,9959    ,272,272,272
BEGIN DESCRIPTION:
Mtn_Crk-19.0
END DESCRIPTION:
XS GIS Cut Line= 6
      1103467.96       587778.39      1103497.37       587594.13
      1103513.95        587542.3      1103513.95       587480.11
      1103482.86       587430.35      1103466.27       587388.89
#Sta/Elev= 30
  4793.9   791.9  4801.8  790.64    4825  788.25    4841  785.65  4854.6     783
  4858.8   782.5  4870.5  782.01    4897  779.37  4909.6   777.4  4921.7   775.1
  4934.3  771.91  4945.5   768.3  4954.1   763.8  4968.9   756.7  4969.3  756.51
  4971.5  744.91  5028.5  744.91  5034.9  753.72  5046.3  755.67  5051.1  755.85
  5058.8  755.22    5071  755.54  5081.3  754.94  5096.4  755.11  5110.5   757.6
    5130  761.94  5159.5  767.49    5182  770.79  5198.6  774.32  5200.4  774.39
#Mann= 3 ,-1 , 0
  4793.9     .09       0  4968.9     .05       0  5034.9     .09       0
Bank Sta=4968.9,5034.9
Exp/Cntr=0.3,0.1

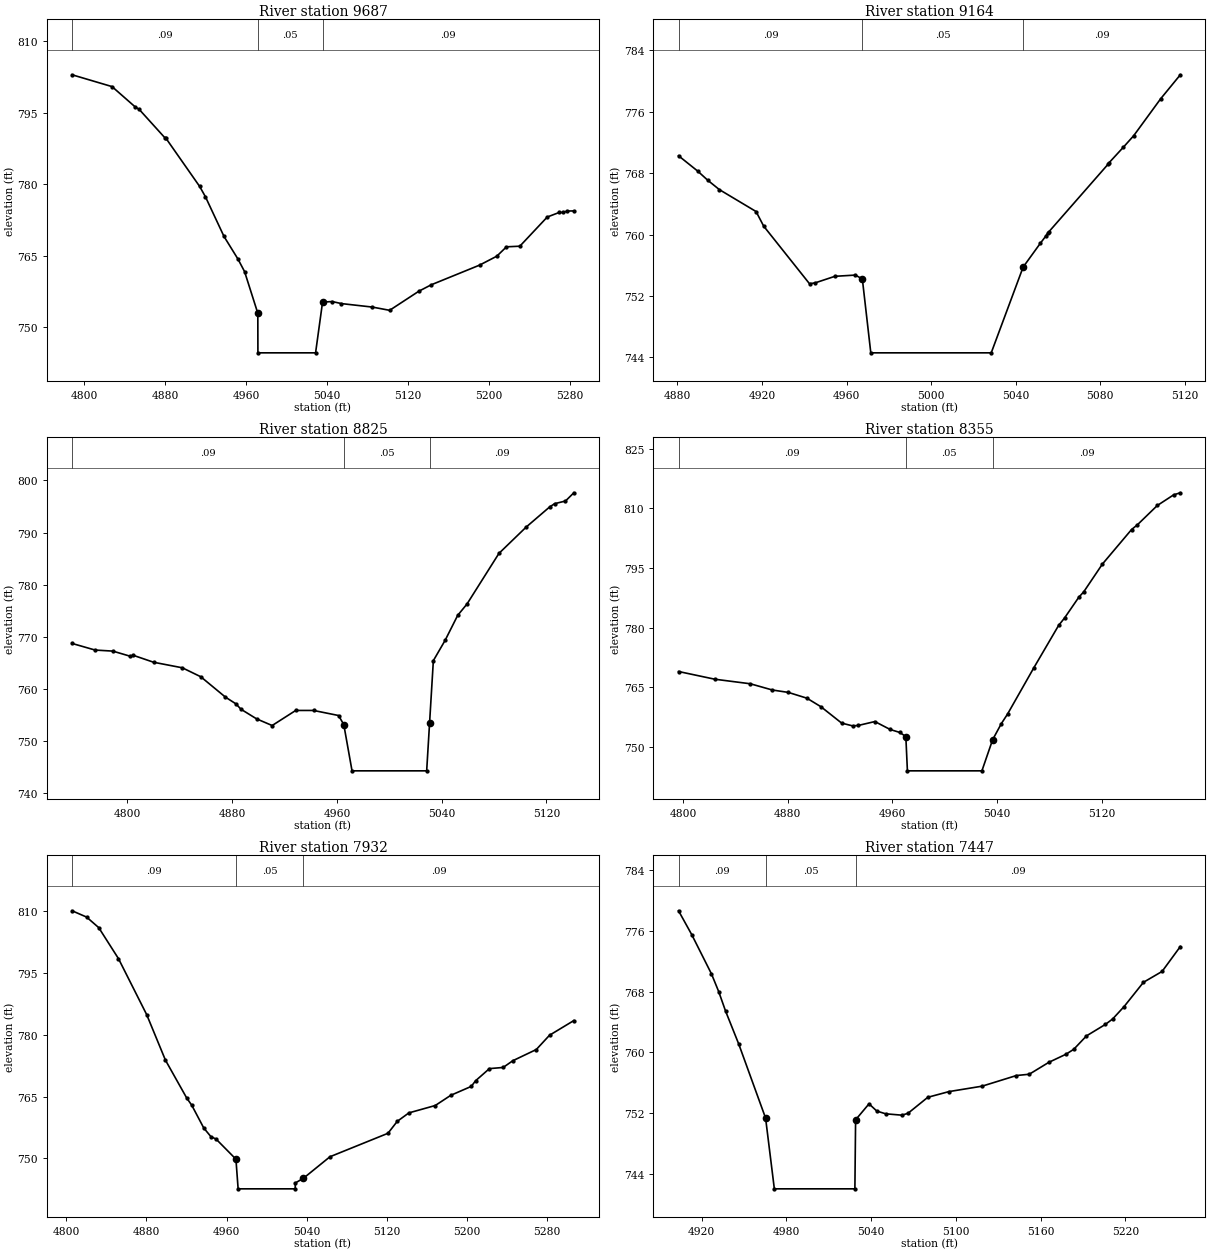
Type RM Length L Ch R = 1 ,9687    ,523,523,523
BEGIN DESCRIPTION:
Mtn_Crk-17.0
END DESCRIPTION:
XS GIS Cut Line= 3
      1103940.12       587511.99      1103639.06       587462.17
      1103491.79       587340.89
#Sta/Elev= 30
  4787.8  802.98  4827.3   800.5  4850.4   796.2  4854.1  795.73  4879.9  789.68
  4880.2  789.78  4913.9  779.56  4919.6   777.4    4938  769.06  4951.7  764.35
  4958.3   761.7  4971.4  752.95  4971.5  744.65  5028.5  744.65  5035.4  755.29
  5044.9  755.41  5054.1  754.98  5084.6  754.25  5101.7  753.57  5130.6  757.58
  5142.8  758.92  5190.6  763.05  5207.6  764.92  5217.2  766.89  5230.4  767.02
  5257.5  773.14  5269.3   774.1  5272.8   774.1  5277.4   774.4  5283.8  774.42
#Mann= 3 , 0 , 0
  4787.8     .09       0  4971.4     .05       0  5035.4     .09       0
Bank Sta=4971.4,5035.4
Exp/Cntr=0.3,0.1

Type RM Length L Ch R = 1 ,9164    ,339,339,339
BEGIN DESCRIPTION:
Mtn_Crk-16.0
END DESCRIPTION:
XS GIS Cut Line= 4
      1103779.33       587061.32      1103657.01       586997.05
      1103592.74       586963.88      1103565.78       586965.95
#Sta/Elev= 24
  4880.5  770.25  4889.5  768.27  4894.3  767.07  4899.8  765.85  4917.2  762.99
  4920.8  761.09  4942.5  753.59  4945.2  753.71  4954.5  754.56  4964.2  754.72
  4967.5  754.21  4971.5   744.6  5028.5   744.6  5043.6  755.76  5051.8  758.88
  5054.4  759.82  5055.4  760.25  5055.8  760.36  5083.9  769.18  5084.2  769.32
    5091  771.35  5095.9  772.85  5108.7  777.67    5118  780.79
#Mann= 3 ,-1 , 0
  4880.5     .09       0  4967.5     .05       0  5043.6     .09       0
Bank Sta=4967.5,5043.6
Exp/Cntr=0.3,0.1

Type RM Length L Ch R = 1 ,8825    ,470,470,470
BEGIN DESCRIPTION:
Mtn_Crk-15.0
END DESCRIPTION:
XS GIS Cut Line= 3
      1103927.12       586925.04      1103866.48       586756.11
      1103723.53         586611.
#Sta/Elev= 30
  4757.7  768.74  4775.3  767.47  4788.8  767.27  4801.9   766.3  4804.6  766.45
    4820  765.13  4841.9  764.07    4856  762.35  4874.8  758.45  4882.8  757.16
  4886.7  756.12  4898.6  754.28  4910.5     753  4928.5  755.89  4942.1  755.89
  4961.2  754.92  4965.2  753.18  4971.5  744.31  5028.5  744.31  5030.7 753.426
  5033.6  765.44  5042.6  769.34  5052.2  774.13  5059.3   776.3  5083.7  786.01
  5104.6  791.08  5122.4  794.91  5126.2  795.54  5134.5  796.05  5140.9  797.63
#Mann= 3 , 0 , 0
  4757.7     .09       0  4965.2     .05       0  5030.7     .09       0
Bank Sta=4965.2,5030.7
Exp/Cntr=0.3,0.1

Type RM Length L Ch R = 1 ,8355    ,423,423,423
BEGIN DESCRIPTION:
mtn crk e
END DESCRIPTION:
XS GIS Cut Line= 3
      1103935.84       586932.26      1104059.53       586856.59
      1104287.99       586786.74
#Sta/Elev= 30
  4796.4     769  4824.2  767.06  4851.3  765.92  4868.2  764.35  4880.4  763.75
  4894.6   762.3  4905.4  760.14  4921.2  756.04  4929.5  755.35  4933.8  755.44
  4946.6  756.43  4958.3  754.44  4965.6   753.7  4970.3  752.67  4971.5  744.05
  5028.5  744.05  5036.7  751.87  5043.4  755.93  5048.1   758.3  5068.2  769.92
  5087.2  780.58  5091.7  782.43  5102.6  787.64  5106.4  789.01  5120.7  795.99
    5143  804.66  5147.3   805.8  5162.7   810.7  5175.2  813.37  5180.3  813.89
#Mann= 3 , 0 , 0
  4796.4     .09       0  4970.3     .05       0  5036.7     .09       0
Bank Sta=4970.3,5036.7
Exp/Cntr=0.3,0.1

Type RM Length L Ch R = 1 ,7932    ,485,485,485
BEGIN DESCRIPTION:
Mtn_Crk-14.0
END DESCRIPTION:
XS GIS Cut Line= 6
      1103888.14       587243.42      1104042.62        587225.1
      1104104.82        587225.1       1104183.6       587212.66
      1104284.49       587176.28      1104366.79       587126.47
#Sta/Elev= 30
  4805.7  810.15  4820.2  808.62  4832.3  806.06    4852  798.53  4880.2  784.91
  4898.9  773.86  4920.2  764.63  4925.2  762.89  4937.2  757.35  4944.3  755.26
  4949.5  754.66  4969.3  749.78  4971.5  742.57  5028.5  742.57  5028.6     744
  5036.7  745.14  5063.2  750.37  5121.1  756.07  5130.4  758.98    5142  761.03
  5168.3  762.82  5183.8   765.3  5204.3  767.47  5208.5  768.82  5222.4  771.79
  5236.1  772.07  5245.7   773.7  5269.2  776.43  5282.4   779.9  5306.7  783.47
#Mann= 3 ,-1 , 0
  4805.7     .09       0  4969.3     .05       0  5036.7     .09       0
Bank Sta=4969.3,5036.7
Exp/Cntr=0.3,0.1

Type RM Length L Ch R = 1 ,7447    ,600,600,600
BEGIN DESCRIPTION:
Mtn_Crk-13.0
END DESCRIPTION:
XS GIS Cut Line= 5
      1104455.19       587579.62      1104486.29        587465.6
      1104486.29        587403.4      1104496.66       587308.03
      1104494.59       587229.25
#Sta/Elev= 30
  4903.7  778.61    4913  775.49    4927  770.32  4932.1     768    4937  765.42
  4946.3   761.1  4965.3  751.37  4971.5  742.07  5028.5  742.07    5029  751.14
  5038.5  753.24    5044  752.29  5050.3  751.93  5061.8  751.75  5066.1     752
  5080.1   754.1  5095.1  754.85  5118.5  755.56  5142.8  756.96  5151.9  757.13
  5165.8   758.7  5177.9  759.76  5183.4  760.41  5192.4  762.17  5205.7  763.67
  5210.9  764.39    5219  766.02  5232.7  769.21  5245.9  770.64  5258.8  773.91
#Mann= 3 ,-1 , 0
  4903.7     .09       0  4965.3     .05       0    5029     .09       0
Bank Sta=4965.3,5029
Exp/Cntr=0.3,0.1

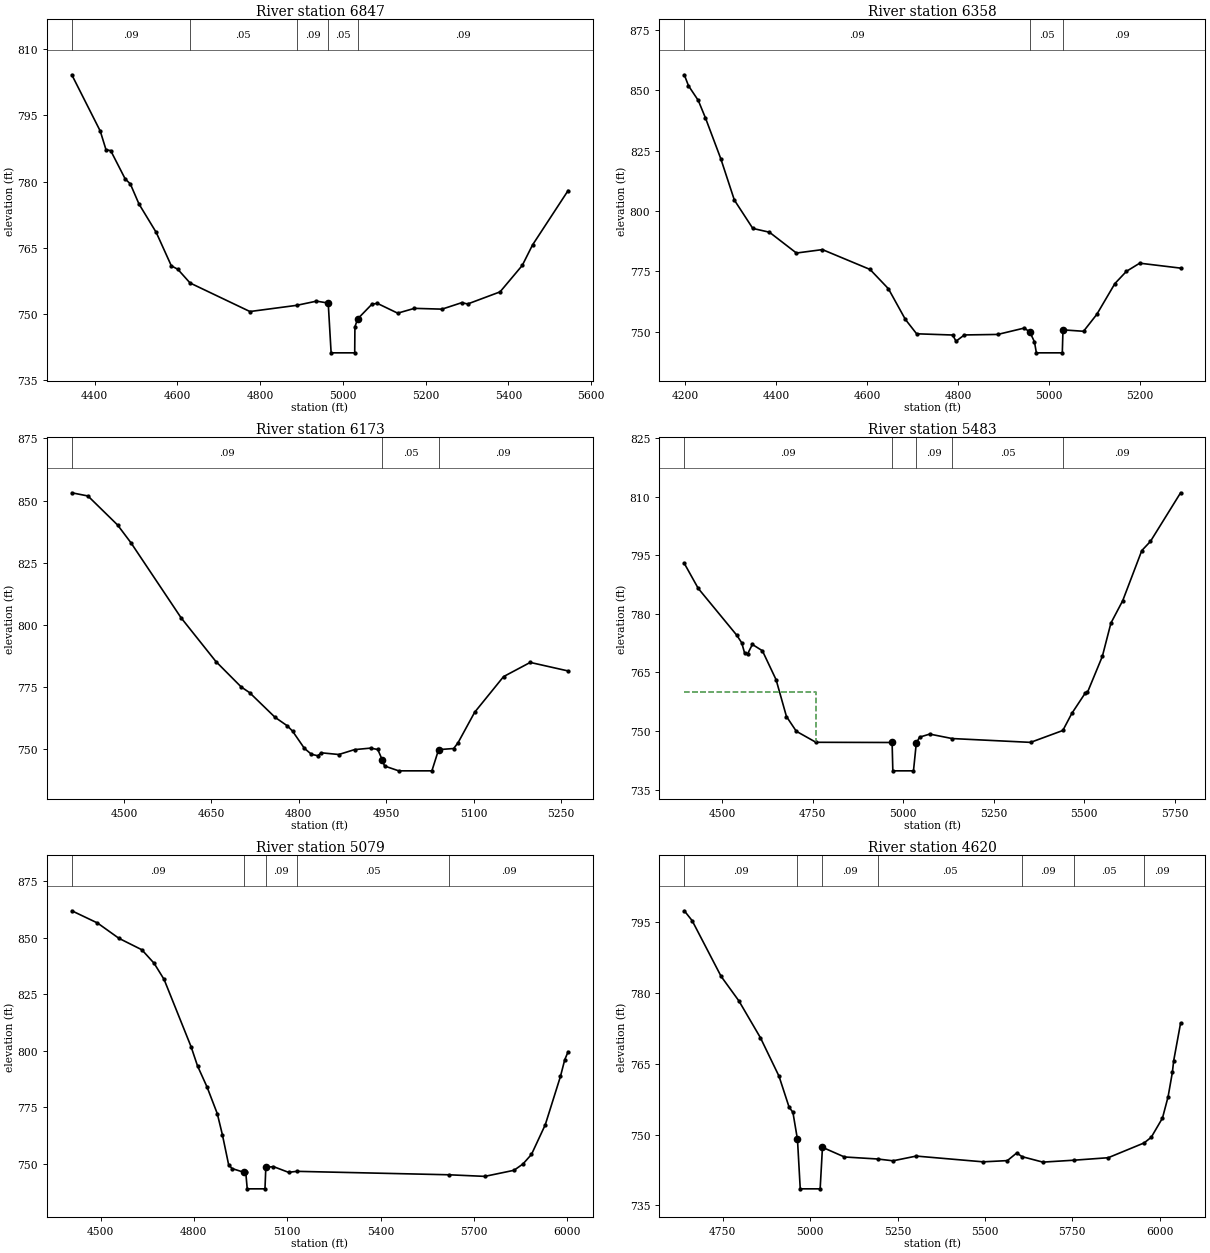
Type RM Length L Ch R = 1 ,6847    ,489,489,489
BEGIN DESCRIPTION:
Mtn_Crk-12.0
END DESCRIPTION:
XS GIS Cut Line= 4
      1105306.77        588107.6      1105103.18       587633.28
      1104990.55       587377.71      1104668.74       587133.88
#Sta/Elev= 30
  4344.9  804.19  4413.7  791.44  4427.6  787.21  4438.9  787.02  4473.9  780.62
  4486.3  779.49  4507.3  774.93    4549  768.49  4585.4  760.95  4601.1  760.16
  4630.7  757.06  4775.3   750.6  4888.2     752  4936.1  752.95  4964.5  752.52
  4971.5  741.25  5028.5  741.25    5029  747.14  5035.6  748.93  5070.1  752.26
  5083.1  752.45  5132.3  750.23  5172.8  751.32  5239.4  751.14  5287.3  752.61
  5301.4  752.31  5379.7  755.05  5433.3  761.03  5458.1  765.66  5544.1  777.98
#Mann= 5 ,-1 , 0
  4344.9     .09       0  4630.7     .05       0  4888.2     .09       0
  4964.5     .05       0  5035.6     .09       0
Bank Sta=4964.5,5035.6
Exp/Cntr=0.3,0.1

Type RM Length L Ch R = 1 ,6358    ,185,185,185
BEGIN DESCRIPTION:
mtn crk f
END DESCRIPTION:
XS GIS Cut Line= 4
      1106116.18       587557.28      1105516.14       587287.32
      1105329.88       587179.64      1105137.68       587076.46
#Sta/Elev= 30
  4197.4  856.48  4206.6  851.93  4228.1  845.85    4244  838.55  4277.6  821.69
  4307.5  804.51    4348  792.77  4384.6  791.19  4443.9  782.56  4501.1  783.98
  4605.8  775.75  4646.1  767.77  4683.5  755.02  4708.2  749.07  4787.6  748.56
  4794.8  745.98  4813.1  748.59  4886.4   748.8    4945  751.45  4957.2  749.77
  4967.3  745.72  4971.5  741.17  5028.5  741.17    5030   750.7  5075.2  750.11
  5104.3  757.11  5144.2  769.91  5169.5  774.97  5198.7  778.35  5288.6   776.3
#Mann= 3 , 0 , 0
  4197.4     .09       0  4957.2     .05       0    5030     .09       0
Bank Sta=4957.2,5030
Exp/Cntr=0.3,0.1

Type RM Length L Ch R = 1 ,6173    ,690,690,690
BEGIN DESCRIPTION:
Mtn_Crk-11.0
END DESCRIPTION:
XS GIS Cut Line= 5
      1105957.06       586933.98      1105464.85       587011.56
      1105363.26       587053.03      1105313.51        587077.9
      1105128.62       587042.27
#Sta/Elev= 30
  4410.3  853.12    4438  851.83  4488.8  840.17  4511.8     833    4598  802.73
  4657.7  785.14  4701.1   774.9  4715.5  772.61  4759.3  762.65  4780.4  759.21
  4789.2  757.12  4809.5  750.19  4821.6  747.78  4832.5  747.18  4838.8  748.36
  4868.7  747.68  4895.7  749.65  4923.1  750.25  4935.6   749.7  4943.2  745.55
  4947.2  743.05  4971.5   741.1  5028.5   741.1    5040  749.65  5065.8  750.09
  5073.3  752.39  5101.9   764.7  5151.5  779.06  5197.3  784.78  5262.3  781.34
#Mann= 3 ,-1 , 0
  4410.3     .09       0  4943.2     .05       0    5040     .09       0
Bank Sta=4943.2,5040
Exp/Cntr=0.3,0.1

Type RM Length L Ch R = 1 ,5483    ,404,404,404
BEGIN DESCRIPTION:
Mtn_Crk-10.0
END DESCRIPTION:
XS GIS Cut Line= 3
      1105869.07       586489.64      1105175.01       586431.98
      1104512.04       586550.55
#Sta/Elev= 30
  4395.9   792.9  4434.4   786.5  4540.9  774.51  4554.4  772.59  4562.5  769.91
  4570.9   769.8  4583.8  772.17  4611.5  770.55  4649.3  763.14  4677.9  753.73
  4705.1  749.96  4759.3  747.14  4969.5  747.09  4971.5  739.84  5028.5  739.84
  5036.3  746.96  5045.5  748.46  5073.4  749.24  5135.1   748.1  5351.7  747.12
  5440.7  750.16  5465.5  754.52  5502.3  759.69  5508.6  759.88  5549.8  769.12
  5573.5  777.64    5606  783.36  5658.7  796.18  5682.5  798.52  5765.8  810.96
#Mann= 5 ,-1 , 0
  4395.9     .09       0  4969.5     .05       0  5036.3     .09       0
  5135.1     .05       0  5440.7     .09       0
#XS Ineff= 2 , 0
       0  4759.3     760               0
Permanent Ineff=
       F       F
Bank Sta=4969.5,5036.3
Exp/Cntr=0.3,0.1

Type RM Length L Ch R = 1 ,5079    ,459,459,459
BEGIN DESCRIPTION:
mtn crk g
END DESCRIPTION:
XS GIS Cut Line= 2
       1105786.8       586047.52      1104191.95       586059.16
#Sta/Elev= 30
  4407.7  861.95  4490.1  856.56  4559.2  849.77  4632.8  844.71  4672.2  838.74
  4704.3  831.59  4791.1  801.82  4811.7  793.37  4842.4  784.01  4875.2  772.26
  4891.5  763.02  4911.6  749.75  4922.5  747.98  4961.1   746.3  4966.7   746.3
  4971.5     739  5028.5     739  5031.2  748.45  5055.5  748.84  5104.4  746.29
  5130.5  746.74  5618.9  745.22  5734.9  744.51  5828.7   747.2  5857.6     750
  5884.9  754.22  5929.2  767.32  5978.1  788.74  5991.9  796.13  6002.6  799.61
#Mann= 5 ,-1 , 0
  4407.7     .09       0  4961.1     .05       0  5031.2     .09       0
  5130.5     .05       0  5618.9     .09       0
Bank Sta=4961.1,5031.2
Exp/Cntr=0.3,0.1

Type RM Length L Ch R = 1 ,4620    ,510,510,510
BEGIN DESCRIPTION:
Mtn_Crk-9.0
END DESCRIPTION:
XS GIS Cut Line= 6
      1105554.35       585613.15      1105258.57       585592.44
      1105175.64       585596.59      1105096.86       585600.74
      1104250.98       585625.62      1104134.88       585625.62
#Sta/Elev= 30
  4639.6  797.33  4662.1  795.24  4744.9  783.47  4795.9  778.27  4857.6  770.47
  4910.7  762.35  4939.6  755.79  4950.5  754.71  4963.6  748.96  4971.5  738.52
  5028.5  738.52  5035.1   747.3    5098  745.26  5193.3  744.83    5237  744.45
  5303.6  745.45  5495.1  744.23  5564.4  744.49  5591.3  746.11  5606.3  745.33
    5666  744.17  5755.5  744.58    5853   745.1  5955.9  748.23  5976.3  749.43
  6008.4  753.49  6024.5     758  6036.7  763.13  6040.5  765.62  6060.3  773.58
#Mann= 7 ,-1 , 0
  4639.6     .09       0  4963.6     .05       0  5035.1     .09       0
  5193.3     .05       0  5606.3     .09       0  5755.5     .05       0
  5955.9     .09       0
Bank Sta=4963.6,5035.1
Exp/Cntr=0.3,0.1

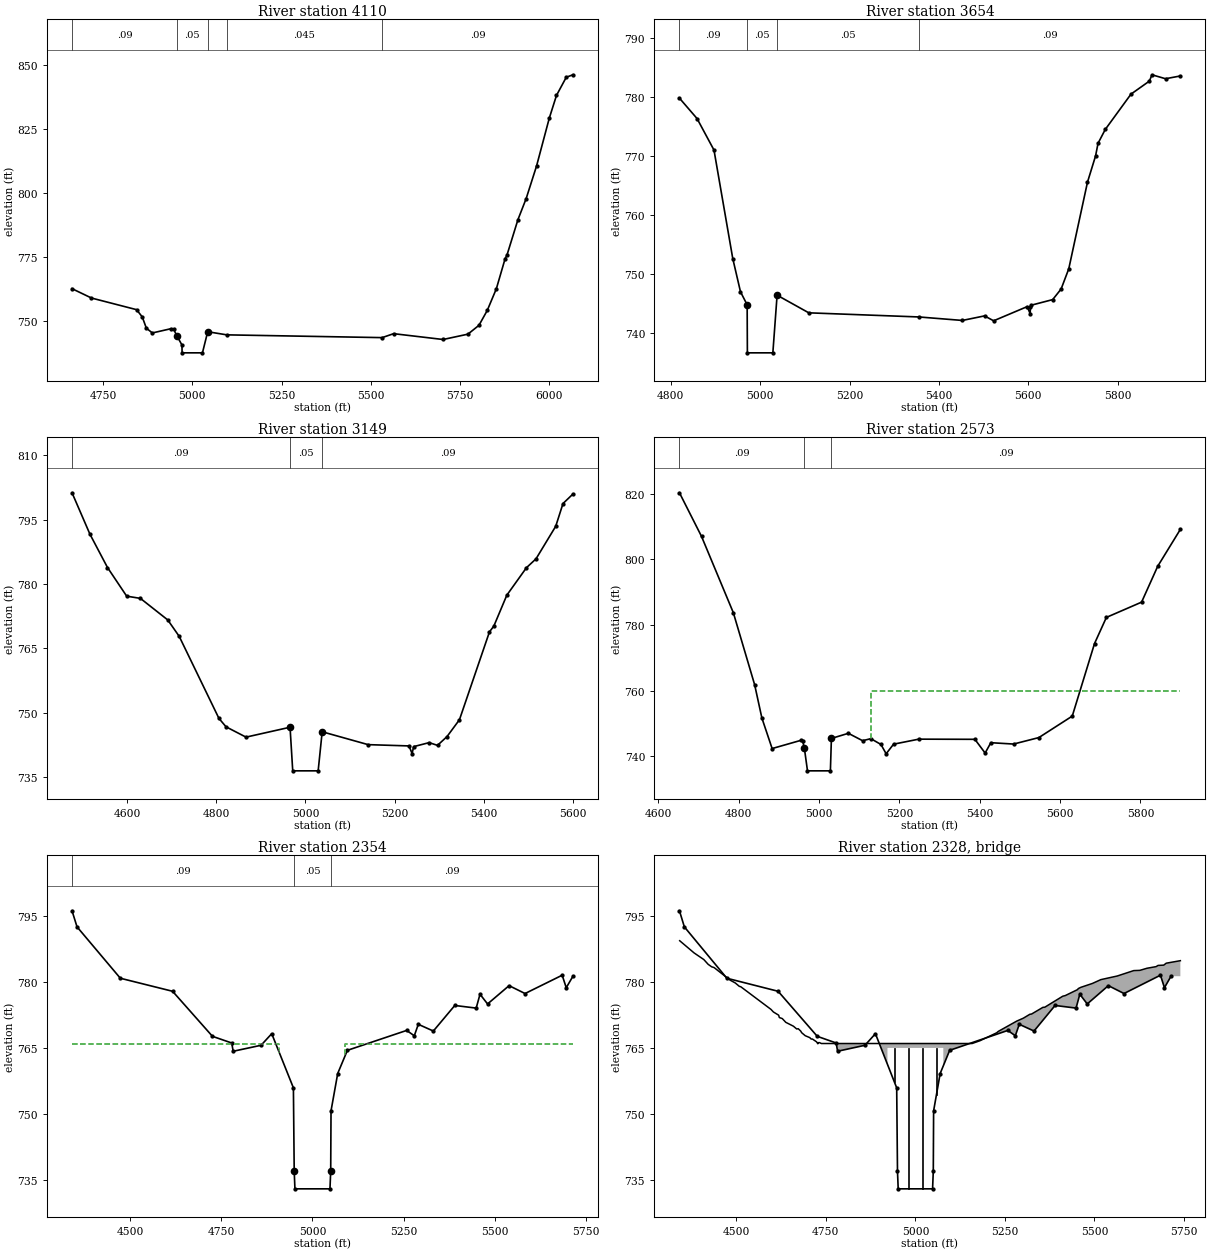
Type RM Length L Ch R = 1 ,4110    ,456,456,456
BEGIN DESCRIPTION:
Mtn_Crk-8.0
END DESCRIPTION:
XS GIS Cut Line= 6
      1105502.17       585230.67      1105404.73       585147.74
       1105321.8       585108.35      1105240.94        585104.2
      1104863.62       585110.42      1104139.78       585141.06
#Sta/Elev= 30
  4663.3  762.68  4717.8  759.03    4844   754.5    4860  751.66  4871.4  747.29
  4888.2  745.42  4939.4  747.05  4947.6  746.91  4956.9   744.3  4971.1  740.72
  4971.5  737.67  5028.5  737.67  5043.2   745.9  5096.6  744.68  5531.5   743.6
  5563.8  745.14  5702.2  742.87  5771.8  744.95  5802.8  748.41    5826  754.21
  5851.5  762.68    5876   774.4  5880.9  775.65  5911.9   789.6  5934.9   797.8
    5964   810.5  5999.6  829.12  6019.8  838.01  6047.2  845.09  6065.9  846.05
#Mann= 5 ,-1 , 0
  4663.3     .09       0  4956.9     .05       0  5043.2     .09       0
  5096.6    .045       0  5531.5     .09       0
Bank Sta=4956.9,5043.2
Exp/Cntr=0.3,0.1

Type RM Length L Ch R = 1 ,3654    ,505,505,505
BEGIN DESCRIPTION:
Mtn_Crk-7.0
END DESCRIPTION:
XS GIS Cut Line= 3
      1105402.06       584652.05      1105067.03       584662.21
      1104281.91       584689.28
#Sta/Elev= 30
  4819.5  779.81  4858.9  776.35  4896.8  771.01  4938.8  752.63  4956.1  746.99
    4971  744.79  4971.5  736.65  5028.5  736.65    5038  746.42  5108.9  743.43
  5355.4  742.73  5452.5  742.14  5502.1  742.91  5522.5  742.08  5597.5  744.48
  5604.2  743.29  5604.8  744.39    5607  744.73  5654.6  745.67  5673.5  747.47
  5690.6  750.89  5732.5  765.58  5750.6  770.03  5756.1  772.16  5772.3  774.51
  5829.8  780.49    5871   782.7  5876.7  783.77  5907.1   783.1  5940.3  783.57
#Mann= 4 ,-1 , 0
  4819.5     .09       0    4971     .05       0    5038     .05       0
  5355.4     .09       0
Bank Sta=4971,5038
Exp/Cntr=0.3,0.1

Type RM Length L Ch R = 1 ,3149    ,576,576,576
BEGIN DESCRIPTION:
Mtn_Crk-6.0
END DESCRIPTION:
XS GIS Cut Line= 3
      1105679.56       584383.01      1105327.61       584156.28
      1104623.71        584173.2
#Sta/Elev= 30
  4476.8  801.29    4517  791.62  4556.3  783.86  4599.3  777.18  4630.1  776.66
  4691.4  771.63    4717  767.81  4806.1  748.67  4822.1   746.7  4866.8   744.3
  4965.5  746.61  4971.5  736.44  5028.5  736.44  5037.5  745.55  5140.5  742.55
  5232.1  742.25    5239  740.48  5242.6  742.09  5277.3  743.02    5296  742.38
  5317.4  744.44  5345.2  748.36  5412.5  768.86  5422.2  770.18  5451.4  777.41
  5495.4  783.82  5516.8  785.88    5561  793.48  5577.3  798.78  5599.6     801
#Mann= 3 , 0 , 0
  4476.8     .09       0  4965.5     .05       0  5037.5     .09       0
Bank Sta=4965.5,5037.5
Exp/Cntr=0.3,0.1

Type RM Length L Ch R = 1 ,2573    ,219,219,219
BEGIN DESCRIPTION:
Mtn_Crk-5.0
END DESCRIPTION:
XS GIS Cut Line= 5
      1105828.46       584335.64      1105676.18       584112.28
       1105608.5       584010.76      1105473.13       583970.15
      1104765.85       583882.16
#Sta/Elev= 30
  4652.9  820.32  4707.8  807.04    4787  783.79    4840  761.86    4858  751.73
  4883.5  742.42  4954.6   744.9  4959.4  744.77  4963.7  742.57  4971.5  735.63
  5028.5  735.63    5031   745.5  5073.2  747.06  5108.6  744.81  5129.2  745.43
  5154.3  743.66  5167.2  740.83  5185.7  743.75  5248.4  745.28    5388  745.23
  5413.5  741.05  5427.7   744.2  5484.3  743.79  5547.2  745.76  5630.3   752.3
  5685.7   774.4  5715.2  782.36  5802.8  787.01  5842.9  797.93  5899.3  809.18
#Mann= 3 , 0 , 0
  4652.9     .09       0  4963.7     .05       0    5031     .09       0
#XS Ineff= 2 , 0
       0                  5129.2       0     760
Permanent Ineff=
       F       F
Bank Sta=4963.7,5031
Exp/Cntr=0.5,0.3

Type RM Length L Ch R = 1 ,2354    ,57,57,57
BEGIN DESCRIPTION:
Pleasant Hill Rd. SR-1149-US
END DESCRIPTION:
XS GIS Cut Line= 6
      1106348.04       583916.25      1106159.38       583910.03
      1105912.67       583868.56      1105601.68       583851.98
      1105039.84       583847.83      1104985.94       583872.71
#Sta/Elev= 30
  4341.1  796.14  4354.8  792.49  4473.5  780.82  4616.7  777.86    4726  767.63
  4778.7  766.12  4782.8  764.24  4859.2   765.6  4888.4  768.23  4947.8  755.93
    4950     737    4952     733    5048     733    5050     737  5050.9  750.71
  5069.2  759.19  5095.7  764.45  5258.1  768.97  5279.1  767.76  5290.1  770.36
  5331.3  768.83  5390.1  774.64  5448.7  774.04  5459.2  777.19  5479.9  774.98
  5538.9  779.14  5582.6  777.35  5684.4  781.51  5695.5  778.67  5713.9  781.28
#Mann= 3 ,-1 , 0
  4341.1     .09       0    4950     .05       0    5050     .09       0
#XS Ineff= 2 , 0
       0  4909.5     766  5090.5       0     766
Permanent Ineff=
       F       F
Bank Sta=4950,5050
Exp/Cntr=0.5,0.3

Type RM Length L Ch R = 3 ,2328    ,,,
BEGIN DESCRIPTION:
Pleasant Hill Rd. SR-1149
Structure ID: Pleasant Hill Rd. SR-1149
Approximate Survey Structure
END DESCRIPTION:
Bridge Culvert--1,0,-1,-1, 0
Deck Dist Width WeirC Skew NumUp NumDn MinLoCord MaxHiCord MaxSubmerge Is_Ogee
12.5,27,3,0, 60, 60, , , , 0, 1,1,,
  4341.8    4382  4409.1  4421.3    4431  4437.8    4482    4497  4508.3  4512.4
  4596.7  4603.5  4618.2    4620  4628.3  4638.1  4659.4  4668.5  4672.8    4680
  4682.2  4692.4    4705    4709  4712.4    4724  4727.6  4729.5  4731.9  4737.5
    4922    4922    5078    5078  5158.4  5180.6  5226.9  5231.7    5283  5301.4
  5319.7  5324.3  5356.1  5361.5  5411.5  5418.7  5452.8    5455  5462.1  5494.3
    5518  5563.7  5609.8  5626.7  5646.7  5672.2  5677.6  5693.5  5700.5    5740
  789.34  786.57  785.07  783.98  783.42  783.25  780.42  779.75  778.98  778.89
  773.75  773.16  772.43   771.9  771.66  770.81  769.93   769.3  769.36   768.8
  768.47  767.77  767.34  767.01  767.02  766.38  765.94   766.2  766.21     766
     766     766     766     766     766  766.64  768.43  768.76  771.09  771.75
  772.64  772.69  774.21  774.25  776.74  776.89  778.24  778.48  778.76  779.64
  780.51  781.33  782.56  782.61  783.09  783.46  783.73   783.8  784.24  784.81
     713     713     713     713     713     713     713     713     713     713
     713     713     713     713     713     713     713     713     713     713
     713     713     713     713     713     713     713     713     713     713
     713     765     765     713     713     713     713     713     713     713
     713     713     713     713     713     713     713     713     713     713
     713     713     713     713     713     713     713     713     713     713
  4341.8    4382  4409.1  4421.3    4431  4437.8    4482    4497  4508.3  4512.4
  4596.7  4603.5  4618.2    4620  4628.3  4638.1  4659.4  4668.5  4672.8    4680
  4682.2  4692.4    4705    4709  4712.4    4724  4727.6  4729.5  4731.9  4737.5
    4922    4922    5078    5078  5158.4  5180.6  5226.9  5231.7    5283  5301.4
  5319.7  5324.3  5356.1  5361.5  5411.5  5418.7  5452.8    5455  5462.1  5494.3
    5518  5563.7  5609.8  5626.7  5646.7  5672.2  5677.6  5693.5  5700.5    5740
  789.34  786.57  785.07  783.98  783.42  783.25  780.42  779.75  778.98  778.89
  773.75  773.16  772.43   771.9  771.66  770.81  769.93   769.3  769.36   768.8
  768.47  767.77  767.34  767.01  767.02  766.38  765.94   766.2  766.21     766
     766     766     766     766     766  766.64  768.43  768.76  771.09  771.75
  772.64  772.69  774.21  774.25  776.74  776.89  778.24  778.48  778.76  779.64
  780.51  781.33  782.56  782.61  783.09  783.46  783.73   783.8  784.24  784.81
     713     713     713     713     713     713     713     713     713     713
     713     713     713     713     713     713     713     713     713     713
     713     713     713     713     713     713     713     713     713     713
     713     765     765     713     713     713     713     713     713     713
     713     713     713     713     713     713     713     713     713     713
     713     713     713     713     713     713     713     713     713     713
Pier Skew, UpSta & Num, DnSta & Num=  ,4941.5, 2 ,4941.5, 2 , 0 , 0 , 0 ,0,0
       1       1
  757.24     765
       1       1
  756.06     765
Pier Skew, UpSta & Num, DnSta & Num=  ,4980.5, 2 ,4980.5, 2 , 0 , 0 , 0 ,0,0
       1       1
     733     765
       1       1
  732.75     765
Pier Skew, UpSta & Num, DnSta & Num=  ,5019.5, 2 ,5019.5, 2 , 0 , 0 , 0 ,0,0
       1       1
     733     765
       1       1
  732.75     765
Pier Skew, UpSta & Num, DnSta & Num=  ,5058.5, 2 ,5058.5, 2 , 0 , 0 , 0 ,0,0
       1       1
  754.51     765
       1       1
  752.48     765
Abutment Skew #Up #Dn= , 2 , 2
    4922  4923.5
     765  760.63
    4922  4923.5
     765  761.21
Abutment Skew #Up #Dn= , 2 , 2
  5076.5    5078
  761.08     765
  5076.5    5078
  759.58     765
BR Coef= 1 , 1 , 0 ,1.25, 0 ,,,0.8,0,2,0,
WSPro=,,,, 1 ,,,, 0 ,,,, 0 ,,,,-1 ,-1 ,-1 , 0 , 0 , 0 , 0 , 0
BC Design=,, 0 ,, 0 ,,,,,,
BC HTab HWMax=796.14