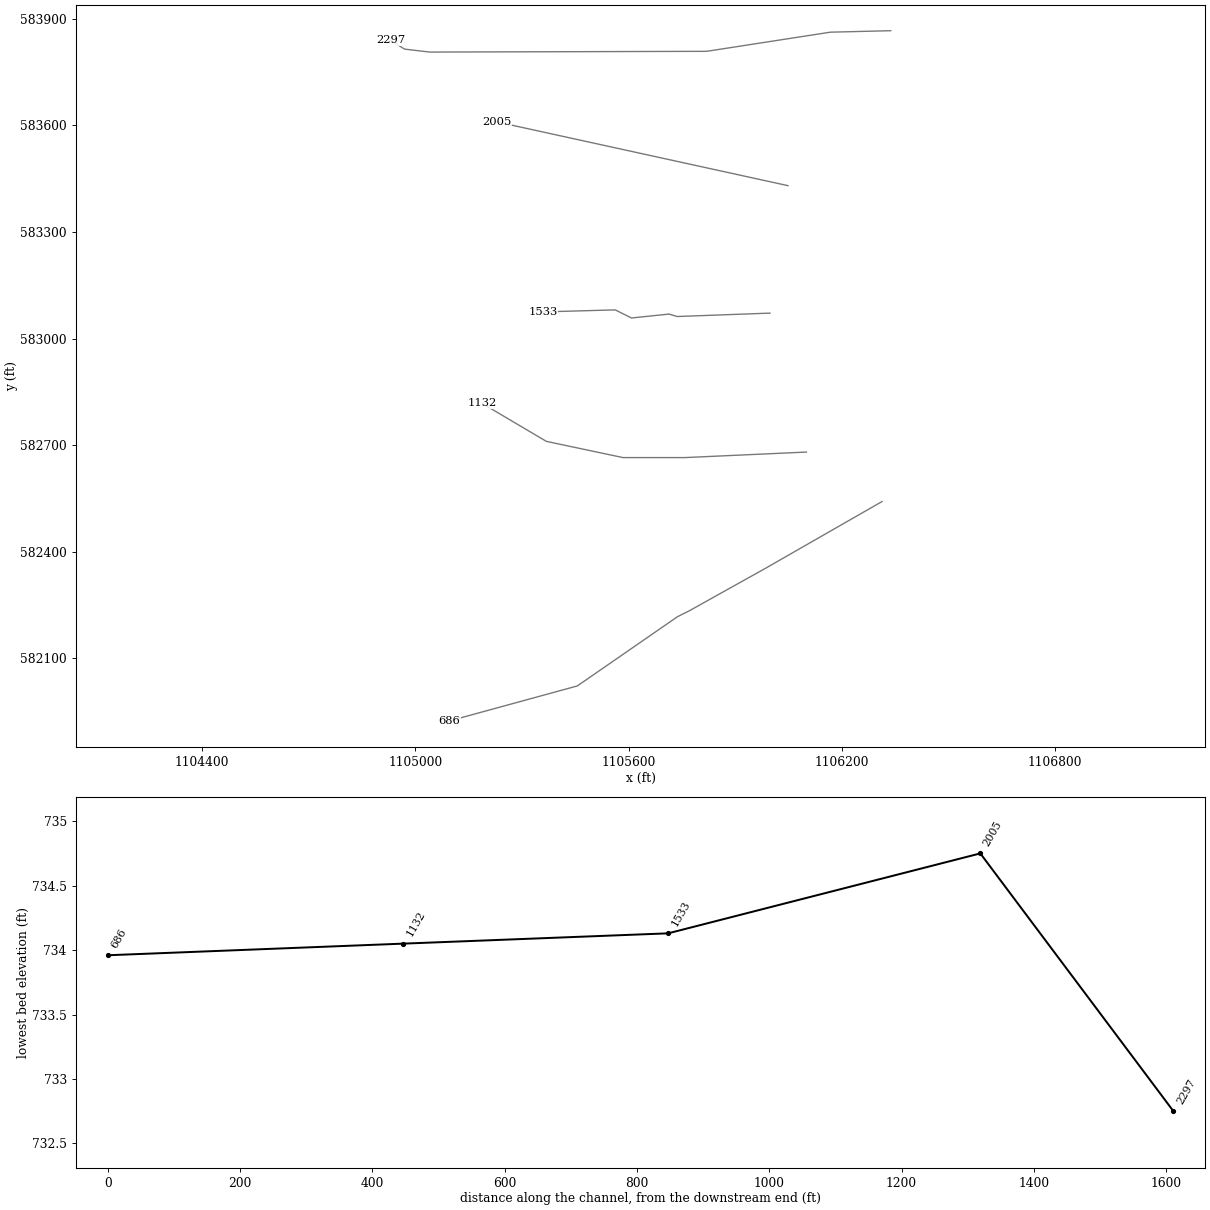
HEC-RAS study lds_mountain_crk.prj: Mountain Creek Limited Detail Study

--- lds_mountain_crk.g01 (geometry) --- (continued)

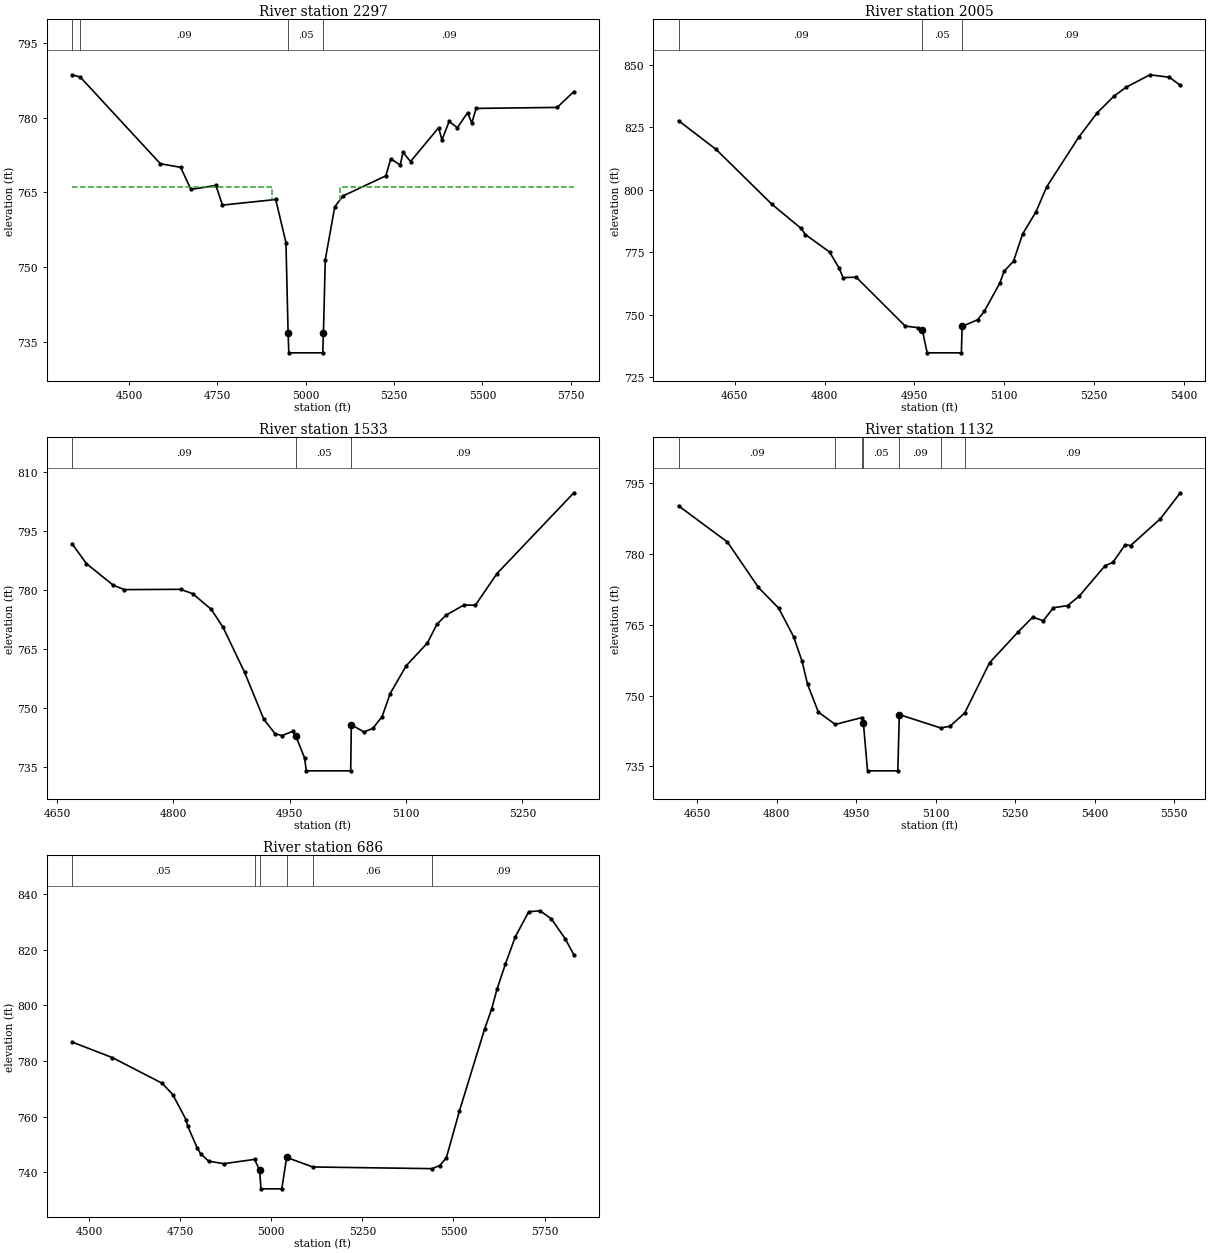
Type RM Length L Ch R = 1 ,2297    ,292,292,292
BEGIN DESCRIPTION:
Pleasant Hill Rd. SR-1149-DS
END DESCRIPTION:
XS GIS Cut Line= 6
      1106337.68       583866.49      1106167.67       583862.34
      1105819.37       583808.44      1105039.84       583806.37
      1104969.35       583814.66      1104929.96       583839.54
#Sta/Elev= 30
  4338.7  788.65  4361.9  788.19  4588.5  770.77  4645.9  770.05  4675.1   765.6
  4745.8   766.4  4764.2  762.45  4914.9  763.58  4943.9  754.93    4950  736.75
    4952  732.75    5048  732.75    5050  736.75  5055.2  751.49  5082.1  762.11
  5105.4  764.29  5226.6  768.34  5240.5  771.77  5267.2   770.5  5275.2  773.07
  5296.4  771.21  5375.9     778  5385.3  775.56  5405.8  779.27  5428.9     778
  5457.8  781.03  5469.8  778.96  5482.1  781.89  5711.4  782.09  5758.6  785.28
#Mann= 4 ,-1 , 0
  4338.7     .05       0  4361.9     .09       0    4950     .05       0
    5050     .09       0
#XS Ineff= 2 , 0
       0  4904.5     766  5095.5       0     766
Permanent Ineff=
       F       F
Bank Sta=4950,5050
Exp/Cntr=0.5,0.3

Type RM Length L Ch R = 1 ,2005    ,472,472,472
BEGIN DESCRIPTION:
Mtn_Crk-4.0
END DESCRIPTION:
XS GIS Cut Line= 2
      1106048.43       583430.38      1105229.47       583609.74
#Sta/Elev= 30
    4556  827.71  4618.9  816.18  4711.7  794.31  4760.9  784.55    4768  782.11
  4808.4  775.11  4824.1  768.76  4830.9  764.86  4852.9  765.04  4934.7  745.47
  4956.7   744.8  4963.4  743.77  4971.4  734.75  5028.6  734.75  5029.8  745.34
  5055.6  747.97  5066.9   751.4  5092.5  762.52  5100.1  767.44  5115.8  771.49
  5130.8  782.29  5153.4   791.3  5171.1  801.22  5224.5  821.05  5255.9  830.96
  5283.3  837.47  5303.5  841.05  5343.6  846.09  5376.1  845.09  5394.4  841.87
#Mann= 3 , 0 , 0
    4556     .09       0  4963.4     .05       0  5029.8     .09       0
Bank Sta=4963.4,5029.8
Exp/Cntr=0.3,0.1

Type RM Length L Ch R = 1 ,1533    ,401,401,401
BEGIN DESCRIPTION:
Mtn_Crk-3.0
END DESCRIPTION:
XS GIS Cut Line= 6
      1105997.67       583071.66      1105736.44       583062.08
      1105713.67       583068.95       1105607.9       583057.94
      1105562.29       583080.74      1105358.07       583075.05
#Sta/Elev= 30
  4669.4  791.88  4687.9  786.83  4722.3  781.36  4736.7  780.21  4809.2  780.29
    4825  779.18    4849  775.16    4864  770.64  4891.7  759.23  4916.6  747.24
  4931.3  743.53  4940.3   743.1  4953.6  744.17    4958  742.92  4969.1  737.42
  4971.4  734.13  5028.6  734.13  5029.4  745.84  5045.7  744.03    5057   744.9
  5069.1  747.92  5079.5  753.78  5100.2  760.86  5127.5  766.65  5139.7  771.38
  5151.2  773.68  5174.7  776.32  5189.3  776.24  5217.2   784.3  5316.3  804.84
#Mann= 3 ,-1 , 0
  4669.4     .09       0    4958     .05       0  5029.4     .09       0
Bank Sta=4958,5029.4
Exp/Cntr=0.3,0.1

Type RM Length L Ch R = 1 ,1132    ,446,446,446
BEGIN DESCRIPTION:
Mtn_Crk-2.0
END DESCRIPTION:
XS GIS Cut Line= 6
      1106100.32       582680.59      1105758.21       582665.06
      1105704.31       582665.06      1105584.06       582665.06
      1105368.45       582710.67      1105187.38       582817.63
#Sta/Elev= 30
  4614.6  790.24    4707  782.56  4765.5  772.93  4803.7  768.54  4831.8   762.5
  4847.7  757.32  4858.2  752.39  4878.6   746.5  4910.5  743.89  4960.8  745.35
  4963.6  744.18  4971.4  734.05  5028.6  734.05  5031.4  745.98  5109.5  743.14
  5127.2  743.51  5154.9  746.33  5201.9  756.99    5256  763.54  5283.2  766.63
  5303.2  765.89  5322.3  768.63  5349.3  769.09  5371.2  771.12  5419.6  777.52
  5434.7  778.27  5457.9     782  5467.9  781.81  5524.2  787.49  5561.9  793.01
#Mann= 7 ,-1 , 0
  4614.6     .09       0  4910.5     .05       0  4960.8     .09       0
  4963.6     .05       0  5031.4     .09       0  5109.5     .06       0
  5154.9     .09       0
Bank Sta=4963.6,5031.4
Exp/Cntr=0.3,0.1

Type RM Length L Ch R = 1 ,686     ,0,0,0
BEGIN DESCRIPTION:
Mtn_Crk-1.0
END DESCRIPTION:
XS GIS Cut Line= 6
      1106313.27       582541.43      1105986.27       582354.08
      1105770.65       582233.83      1105737.48       582217.25
      1105455.52       582022.36      1105094.61       581923.67
#Sta/Elev= 30
  4452.8  786.81  4563.4  781.21  4700.2  771.97  4729.2   767.9  4765.9  758.82
  4770.4  756.46  4796.2   748.8  4805.8  746.58  4827.5  743.95  4869.2  743.01
  4953.9  744.57  4967.7  740.67  4971.4  733.96  5028.6  733.96  5041.9  745.28
  5113.6  741.83  5441.1  741.23    5462  742.35  5480.3  745.06  5516.2  761.94
  5585.5  791.49  5604.6  798.62  5619.4  805.79  5642.7  814.94  5669.8  824.72
  5706.6  833.72  5737.6  834.07  5768.3  831.22  5806.6  824.03  5830.5  818.24
#Mann= 6 ,-1 , 0
  4452.8     .05       0  4953.9     .09       0  4967.7     .05       0
  5041.9     .09       0  5113.6     .06       0  5441.1     .09       0
Bank Sta=4967.7,5041.9
Exp/Cntr=0.3,0.1

Chan Stop Cuts=-1
Use User Specified Reach Order=0
User Specified Reach Order=Mountain Creek  ,Reach-1