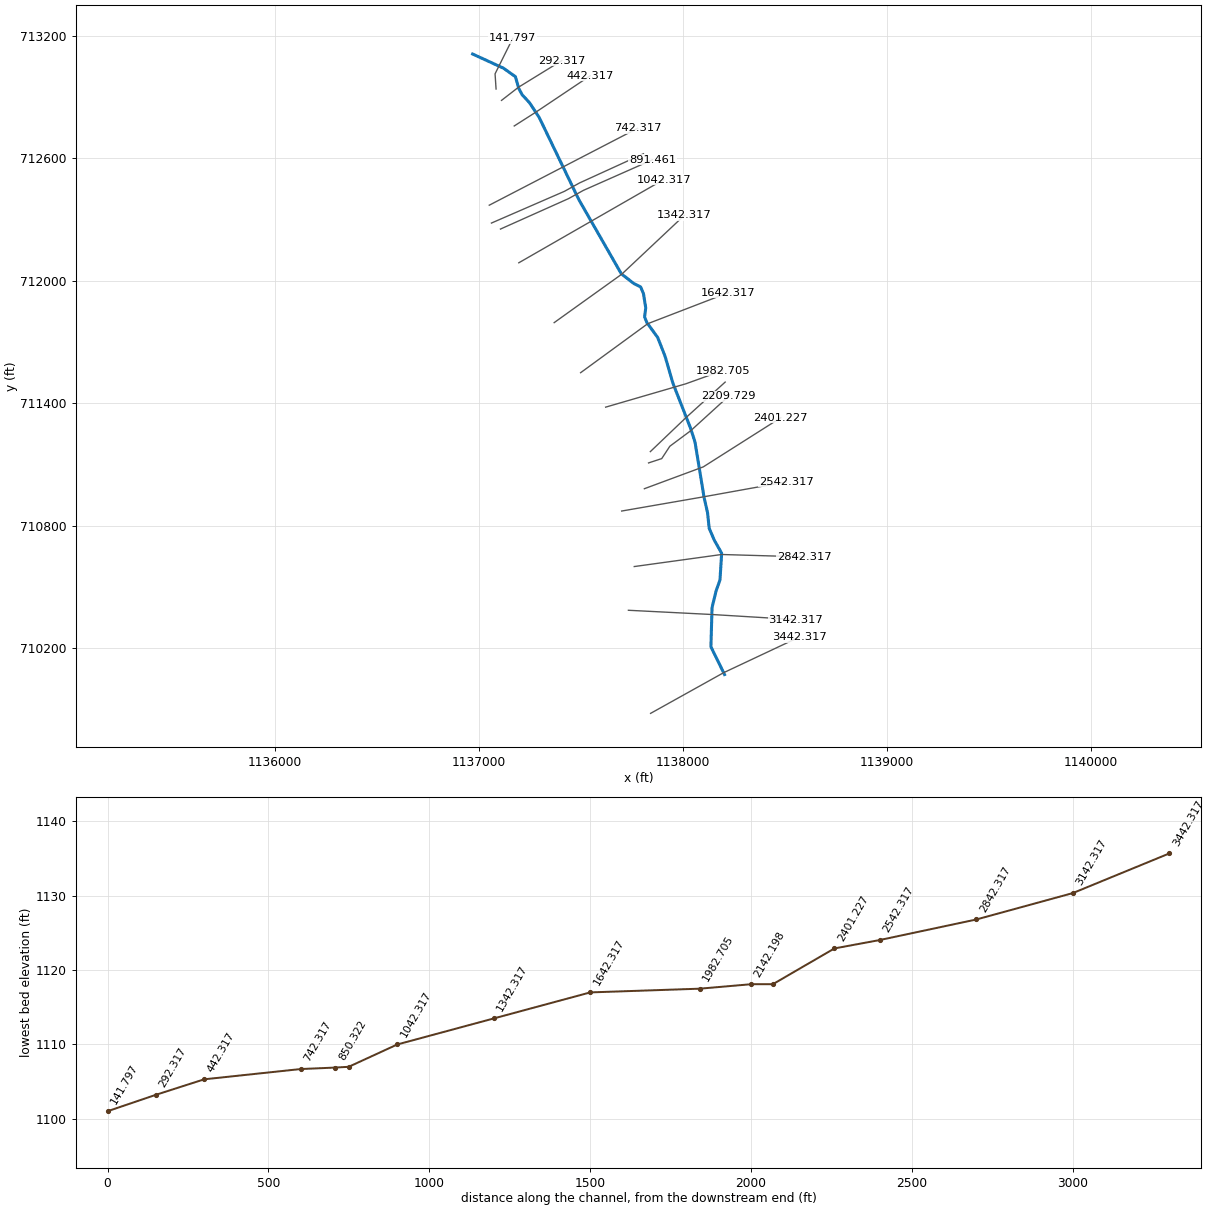
--- WaltonCrowley.prj (project) ---

Proj Title=WaltonCrowley
Current Plan=p02
Default Exp/Contr=0.3,0.1
English Units
Geom File=g01
Flow File=f01
Plan File=p02
Y Axis Title=Elevation
X Axis Title(PF)=Main Channel Distance
X Axis Title(XS)=Station
BEGIN DESCRIPTION:
END DESCRIPTION:
DSS Export Rating Curves= 0
DSS Export Rating Curve Sorted= 0
DSS Export Volume Flow Curves= 0
DXF OffsetX= 0
DXF OffsetY= 0
DXF ScaleX= 1
DXF ScaleY= 10

--- WaltonCrowley.p02 (plan) ---

Plan Title=Plan 02
Program Version=3.12
Short Identifier=Plan 02
Geom File=g01
Flow File=f01
Subcritical Flow
K Sum by GR= 0
Std Step Tol= 0.01
Critical Tol= 0.01
Num of Std Step Trials= 20
Max Error Tol= 0.3
Flow Tol Ratio= 0.001
Split Flow NTrial= 30
Split Flow Tol= 0.02
Split Flow Ratio= 0.02
Log Output Level= 0
Friction Slope Method= 1
Unsteady Friction Slope Method= 2
Unsteady Bridges Friction Slope Method= 1
Calc Critical at every XS
Parabolic Critical Depth
Global Vel Dist= 0 , 0 , 0
Global Log Level= 0
CheckData=True
Encroach Param=-1 ,10,10, 2
Encroach River=WaltonCrowley
Encroach Reach=Main
Encroach Node=3442.317
       1  301.61     421
Encroach Node=3142.317
       1  323.11     425
Encroach Node=2842.317
       1   364.8  451.24
Encroach Node=2542.317
       1   353.9  430.28
Encroach Node=2401.227
       1  208.85  356.23
Encroach Node=2209.729
       1  249.08  293.76
Encroach Node=2142.198
       1  220.37  265.05
Encroach Node=1982.705
       1  263.18  372.47
Encroach Node=1642.317
       1  346.53   490.9
Encroach Node=1342.317
       1  365.08  429.18
Encroach Node=1042.317
       1  275.91  441.61
Encroach Node=891.461
       1     350  481.35
Encroach Node=850.322
       1  415.81     520
Encroach Node=742.317
       1  387.63  515.74
Encroach Node=442.317
       1   103.9  155.84
Encroach Node=292.317
       1   94.03   171.6
Encroach Node=141.797
       1   90.53  148.26
Computation Interval=1HOUR
Output Interval=1HOUR
Run HTab= 0
Run UNet= 0
Run PostProcess= 0
UNET Theta= 1
UNET Theta Warmup= 1
UNET ZTol= 0.02
UNET ZSATol= 0.05
UNET MxIter= 20
UNET MaxInSteps= 0
UNET DtIC= 0
UNET DtMin= 0
UNET MaxCRTS= 20
UNET WFStab= 2
UNET SFStab= 1
UNET WFX= 1
UNET SFX= 1
UNET DSS MLevel= 4
UNET DZMax Abort= 100
UNET Convert EG Bridges=-1
UNET Use Existing IB Tables=-1
UNET Froude Reduction=False
UNET Froude Limit= 1
UNET Froude Power= 10
Instantaneous Interval=1HOUR
Write IC File= 0
Echo Input=False
Echo Output=False
Write Detailed= 0
Detailed Automatic Start=False, 10

--- WaltonCrowley.f01 (steady flow) ---

Flow Title=WaltonCrowley
Program Version=3.12
Number of Profiles= 2
Profile Names=P100yr,Encroachment
River Rch & RM=WaltonCrowley,Main            ,3442.317
    1080    1080
River Rch & RM=WaltonCrowley,Main            ,2401.227
    1310    1310
Boundary for River Rch & Prof#=WaltonCrowley,Main            , 1
Up Type= 0
Dn Type= 3
Dn Slope=0.008
DSS Import GetInterval= 0
DSS Import GetPeak= 0
DSS Import FillOption= 0

--- WaltonCrowley.g01 (geometry) ---

Geom Title=USGS 10m DEM
Program Version=3.12

River Reach=WaltonCrowley   ,Main
Reach XY= 30
   1138205.38151   710069.808925  1138138.629028   710205.939489
  1138144.248742   710397.558549     1138163.631   710478.130966
  1138183.127963   710533.689113  1138191.381397   710664.245016
  1138155.381665   710728.130309  1138130.379654   710786.498332
  1138121.995156   710864.248613  1138105.381781   710936.497945
  1138060.878747   711208.689423   1138038.62926   711278.128917
  1137952.494481   711497.559826  1137913.631619   711630.937865
  1137877.500823   711722.561295  1137824.744354   711794.810628
  1137813.631889   711822.561063  1137819.251604   711866.998547
  1137808.130979   711936.499493  1137794.249631   711969.808153
   1137760.87952   711986.499338  1137699.750812   712033.689384
  1137491.379077   712397.561605  1137296.999332   712800.378636
  1137249.751972   712872.558357  1137213.629337   712911.499029
  1137196.999564    712942.00605   1137180.37799   713000.378134
  1137122.001807    713042.00168  1136970.748835   713111.445273

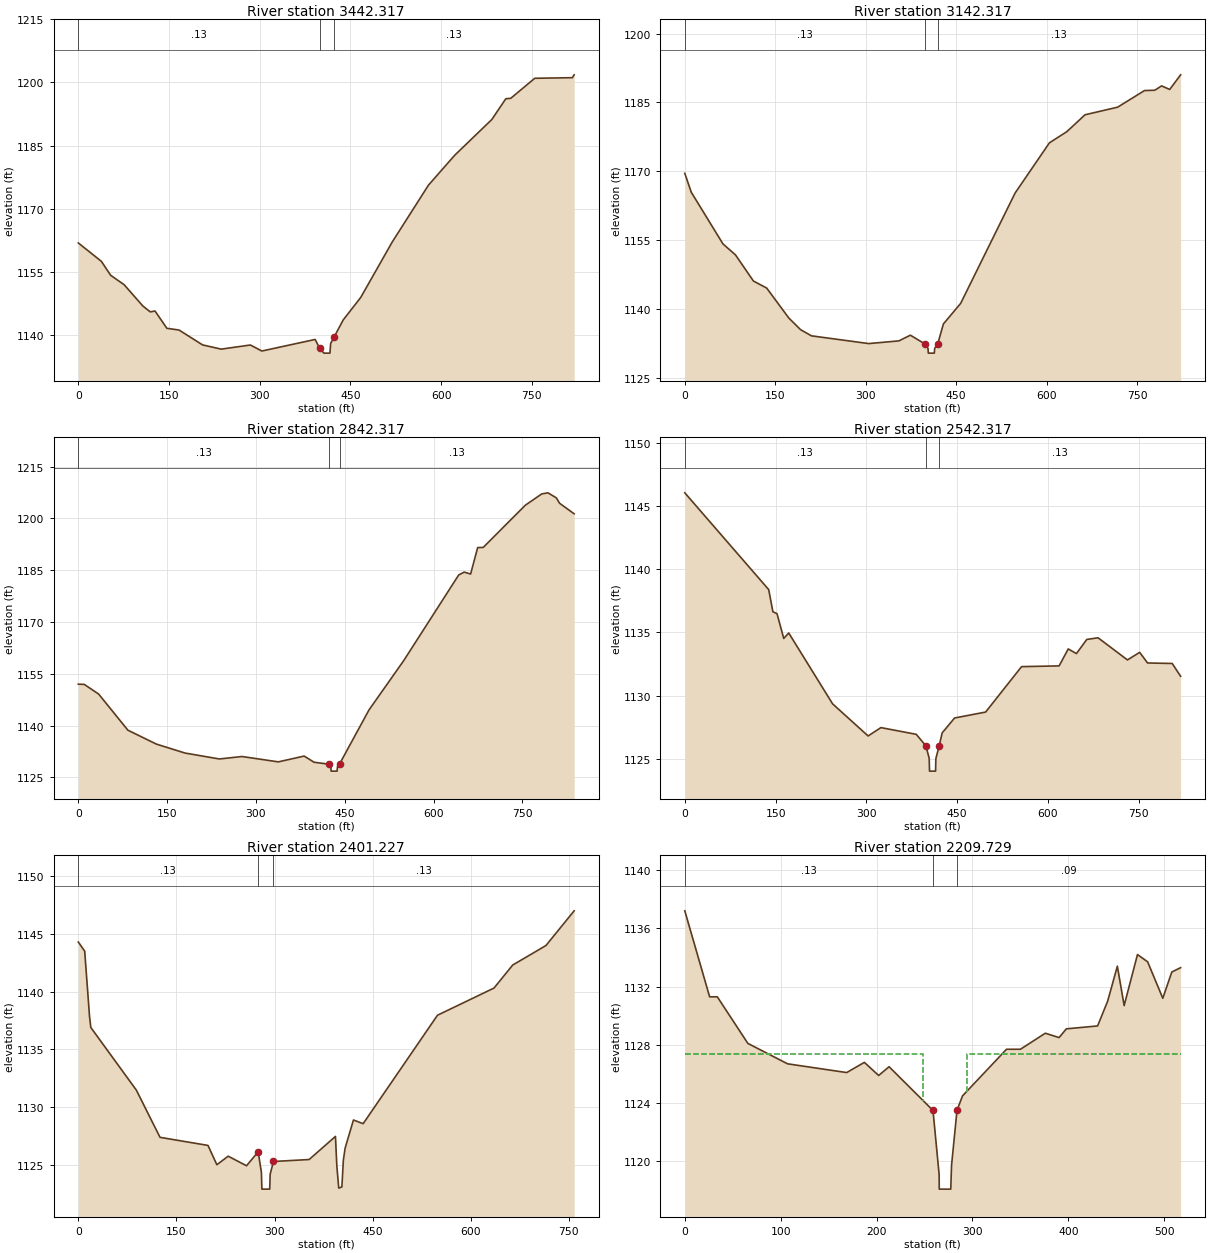
Type RM Length L Ch R = 1 ,3442.317,317,300,284.78
XS GIS Cut Line= 3
  1137842.955937   709879.361275  1138200.514994   710078.544885
  1138572.059624   710253.463246
#Sta/Elev= 30
       0 1161.86   38.18 1157.48   53.43 1154.18   75.89 1151.92  106.82 1146.86
  119.02 1145.48  126.82 1145.69  146.45 1141.58  166.69 1141.16  205.48 1137.63
  236.31 1136.63   284.5 1137.61  303.51 1136.18  391.67 1138.93  398.97 1136.87
   406.1 1135.68   416.1 1135.68  417.24 1137.95  423.23 1139.57  438.01 1143.56
  467.06 1148.92  519.03 1162.07  579.06  1175.6  622.43  1182.7  683.86  1191.2
  706.96 1196.13  715.09 1196.23  754.83 1200.99  817.06 1201.13  819.96 1201.81
#Mann= 3 , 0 , 0
       0     .13       0  398.97    .055       0  423.23     .13       0
Bank Sta=398.97,423.23
Exp/Cntr=0.3,0.1

Type RM Length L Ch R = 1 ,3142.317,290.73,300,300.93
XS GIS Cut Line= 3
  1137734.261976   710384.757304  1138142.555553   710364.097169
  1138555.169311   710339.000177
#Sta/Elev= 30
       0 1169.54   10.74 1165.42   63.32 1154.15   83.93 1151.78  113.84 1146.06
  135.82 1144.53  172.45 1138.01  191.94 1135.47  209.95 1134.12  305.02 1132.43
  355.05 1133.02  374.07 1134.26  398.24 1132.35  403.29 1131.39  403.81 1130.35
  413.81 1130.35  414.33 1131.38  419.38 1132.33  428.83 1136.71  457.47  1141.2
  547.75 1165.25  604.63 1176.19  633.62 1178.63  663.63  1182.3  717.75 1183.96
  762.28 1187.58  779.38 1187.65  790.61  1188.6  804.09 1187.82  822.19 1191.01
#Mann= 3 , 0 , 0
       0     .13       0  398.24    .055       0  419.38     .13       0
Bank Sta=398.24,419.38
Exp/Cntr=0.3,0.1

Type RM Length L Ch R = 1 ,2842.317,294.84,300,306.15
XS GIS Cut Line= 3
  1137762.931596   710599.078211  1138191.028195    710658.18292
  1138596.299735   710646.386791
#Sta/Elev= 30
       0 1151.98    9.99 1151.92   34.32 1149.12   83.75 1138.65  131.78 1134.63
  180.17 1132.04  238.19 1130.32  276.48 1131.03   337.9 1129.48  381.52 1131.16
  398.23 1129.37  422.98 1128.82  426.49 1128.04  427.11  1126.8  437.11  1126.8
  437.75 1128.07  441.24 1128.85  491.06 1144.53  549.75 1158.82   642.6 1183.61
  651.75 1184.43  662.68 1183.88  674.61 1191.53  684.02 1191.58  755.11  1203.8
  782.95 1207.08  793.36 1207.39  807.44 1205.94  812.99 1204.37   837.6 1201.32
#Mann= 3 , 0 , 0
       0     .13       0  422.98    .055       0  441.24     .13       0
Bank Sta=422.98,441.24
Exp/Cntr=0.3,0.1

Type RM Length L Ch R = 1 ,2542.317,135.47,141.09,148.39
XS GIS Cut Line= 3
  1137701.301104    710871.23643  1138104.682802   710941.210503
    1138507.9281   711013.947156
#Sta/Elev= 30
       0 1146.04  138.63 1138.39  145.54 1136.64  152.36 1136.49  163.46 1134.53
  171.73 1134.96  244.17 1129.36  302.83 1126.82  324.02 1127.48  382.38 1126.95
  398.31 1126.04  403.79 1125.05   404.3 1124.04   414.3 1124.04   414.8 1125.03
  420.28 1126.04   425.2 1127.06  445.66 1128.24  497.04 1128.71  556.37  1132.3
  618.46 1132.36  633.49  1133.7  647.02 1133.33  664.15 1134.45  682.78 1134.58
  731.34 1132.83  751.46 1133.43  764.55 1132.59  805.26 1132.55  819.16 1131.54
#Mann= 3 , 0 , 0
       0     .13       0  398.31    .055       0  420.28     .13       0
Bank Sta=398.31,420.28
Exp/Cntr=0.3,0.1

Type RM Length L Ch R = 1 ,2401.227,182.11,191.5,201.8
XS GIS Cut Line= 3
  1137812.538251   710980.655474  1138101.458813   711087.783326
  1138481.275711   711328.820973
#Sta/Elev= 30
       0 1144.28    9.75 1143.49   17.13 1137.84   19.11 1136.89   88.74 1131.47
  124.87 1127.39  198.22 1126.69  211.79 1125.02  229.12 1125.76  257.13 1124.93
  274.94 1126.14  279.88 1124.35   280.6 1122.91   292.6 1122.91  293.24 1124.19
  298.26  1125.3  352.85 1125.47  393.09 1127.47   395.2  1124.9  398.11    1123
   402.9  1123.1  405.16 1125.42  407.88 1126.46  420.57 1128.89  435.42 1128.57
  549.06 1137.95  635.46  1140.3  664.03 1142.29  714.91 1143.98  757.99 1146.98
#Mann= 3 , 0 , 0
       0     .13       0  274.94    .055       0  298.26     .13       0
Bank Sta=274.94,298.26
Exp/Cntr=0.5,0.3

Type RM Length L Ch R = 1 ,2209.729,64.18,67.54,67.11
BEGIN DESCRIPTION:
Upstream xs of Bridge 37111-0130
END DESCRIPTION:
XS GIS Cut Line= 5
   1137833.04992   711107.063254  1137897.628158   711128.286317
  1137937.296312   711188.780204  1138039.168364   711264.474078
  1138224.006548   711432.702522
#Sta/Elev= 30
       0  1137.2    25.9  1131.3    33.9  1131.3    65.8  1128.1   107.2  1126.7
   168.9  1126.1   187.3  1126.8   202.2  1125.9   213.1  1126.5   258.9  1123.5
   265.3  1119.1  265.43  1118.1  277.43  1118.1  278.24 1119.73  283.94 1123.51
   289.7  1124.5   335.6  1127.7   350.1  1127.7   376.1  1128.8   390.4  1128.5
     398  1129.1   430.6  1129.3   441.1    1131   451.2  1133.4   458.3  1130.7
   472.2  1134.2   482.8  1133.7   498.6  1131.2     508    1133   517.2  1133.3
#Mann= 3 , 0 , 0
       0     .13       0   258.9    .055       0  283.94     .09       0
#XS Ineff= 2 , 0
       0   248.7  1127.4   293.9       0  1127.4
Permanent Ineff=
       F       F
Bank Sta=258.9,283.94
Exp/Cntr=0.5,0.3

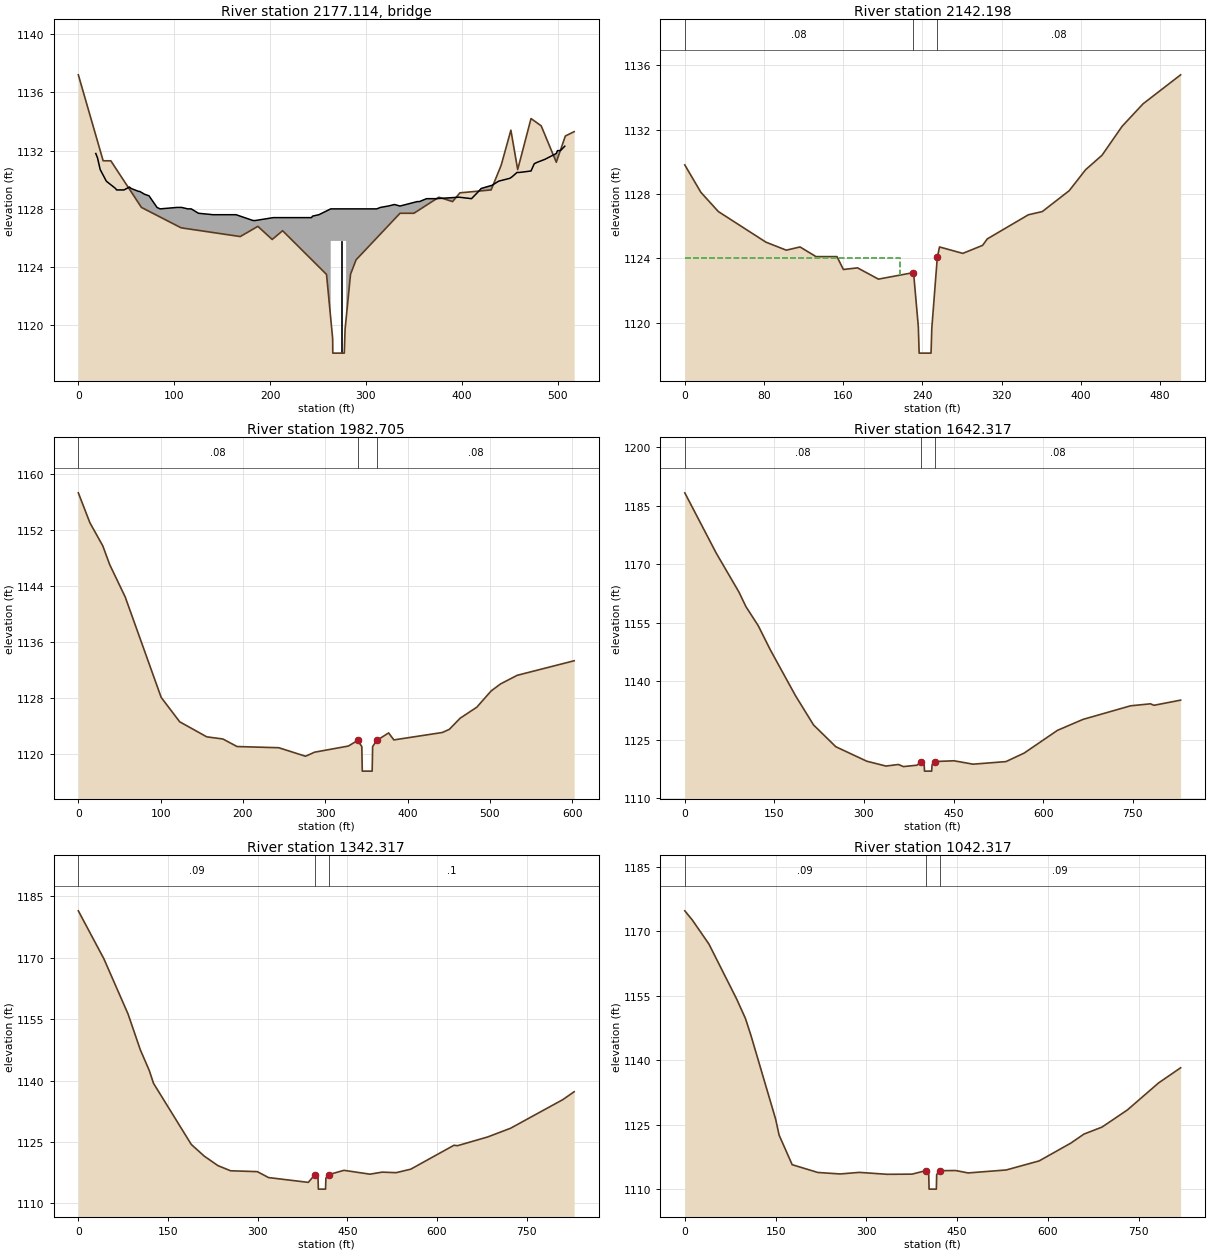
Type RM Length L Ch R = 3 ,2177.114,,,
BEGIN DESCRIPTION:
Bridge : 37111-0130
END DESCRIPTION:
Bridge Culvert--1,0,-1,-1, 0
Deck Dist Width WeirC Skew NumUp NumDn MinLoCord MaxHiCord MaxSubmerge Is_Ogee
14.6,36,2.6,0, 72, 77, 1127.4, , 0.95, 0, 0,0,,
    18.2      20    22.8    29.2    38.8    39.9    40.6    41.9    47.6    53.3
    55.1    62.9      64    69.2    73.7    82.1    85.3     103   104.9   107.8
   114.1   117.8   125.3   140.4     145   163.7   164.5   182.3     183   184.5
   203.3   203.9   219.3   227.8   228.9   243.3   244.2   250.9   263.3   279.3
   296.4   306.9   311.3   315.1   323.6   329.7   335.2   335.8   353.5   355.8
   363.2   373.2   396.6   397.4   410.1   417.5   420.2   430.5   431.1   438.4
   450.2   452.4   457.6   460.2   472.2   475.6   478.8   486.7   498.5   499.8
   502.9   507.4
  1131.8  1131.5  1130.7  1129.9  1129.4  1129.3  1129.3  1129.3  1129.3  1129.5
  1129.4  1129.2  1129.2    1129  1128.9  1128.1    1128  1128.1  1128.1  1128.1
    1128    1128  1127.7  1127.6  1127.6  1127.6  1127.6  1127.2  1127.2  1127.2
  1127.4  1127.4  1127.4  1127.4  1127.4  1127.4  1127.5  1127.6    1128    1128
    1128    1128    1128  1128.1  1128.2  1128.3  1128.2  1128.2  1128.5  1128.5
  1128.7  1128.7  1128.8  1128.8  1128.7  1129.2  1129.4  1129.6  1129.6  1129.9
  1130.1  1130.2  1130.5  1130.5  1130.6  1131.1  1131.2  1131.4  1131.8    1132
    1132  1132.3
                                                                                
                                                                                
                                                                                
                                                                  1125.8  1125.8
                                                                                
                                                                                
                                                                                
                
   -10.3    -8.5    -5.7      .7    10.2    11.4    12.1    13.4    19.1    24.8
    26.6    34.4    35.5    40.7    45.2    53.6    56.8    70.4    74.4    76.3
    79.3    85.6    89.3    96.8   111.9   116.5   135.2     136   139.7   153.7
   154.4     156   172.1   174.7   175.3   190.8     195   199.3   200.4     210
   215.7   222.4   234.8   250.8   267.9   278.3   282.8   286.6   295.1   301.2
   306.7   307.3   321.7     325   327.3   334.7   344.7   368.1   368.9   384.7
     389   391.6     402   402.6   409.9   421.7   423.9   429.1   431.7   443.7
   447.1   450.3   458.2     470   471.3   474.4   478.9
  1131.8  1131.5  1130.7  1129.9  1129.4  1129.3  1129.3  1129.3  1129.3  1129.5
  1129.4  1129.2  1129.2    1129  1128.9  1128.1    1128    1128  1128.1  1128.1
  1128.1    1128    1128  1127.7  1127.6  1127.6  1127.6  1127.6  1127.2  1127.2
  1127.2  1127.2  1127.3  1127.4  1127.4  1127.4  1127.5  1127.4  1127.4  1127.5
  1127.5  1127.6    1128    1128    1128    1128    1128  1128.1  1128.2  1128.3
  1128.2  1128.2  1128.3  1128.5  1128.5  1128.7  1128.7  1128.8  1128.8  1128.9
  1129.2  1129.4  1129.6  1129.6  1129.9  1130.1  1130.2  1130.5  1130.5  1130.6
  1131.1  1131.2  1131.4  1131.8    1132    1132  1132.3
                                                                                
                                                                                
                                                                                
                                                                                
                  1125.8  1125.8
                                                                                
                                                                                
                                                        
Pier Skew, UpSta & Num, DnSta & Num=  ,274.26, 2 ,245.75, 2 , 0 , 0 , 0 ,,
       1       1
  1117.8  1126.3
       1       1
  1117.8  1126.3
BR Coef=-1 , 1 , 0 ,1.25, 0 ,,,0.8,0,2,0,
WSPro=,,,, 1 ,,,, 0 ,,,, 0 ,,,,-1 ,-1 ,-1 , 0 , 0 , 0 , 0 , 0
BC Design=,, 0 ,, 0 ,,,,,,

Type RM Length L Ch R = 1 ,2142.198,174.44,159.49,145.46
BEGIN DESCRIPTION:
Down stream xs of Bridge 37111-0130
END DESCRIPTION:
XS GIS Cut Line= 3
  1137841.754941   711162.448184  1138013.904071   711326.810548
  1138208.586665   711503.309482
#Sta/Elev= 30
       0  1129.8    16.2  1128.1    33.9  1126.9    81.9    1125   102.5  1124.5
   116.4  1124.7   132.5  1124.1   153.7  1124.1   160.2  1123.3   174.5  1123.4
   195.6  1122.7  230.37  1123.1   231.5  1122.8  235.89 1119.73  236.71  1118.1
  248.71  1118.1  249.48 1119.64  255.05 1124.06   257.3  1124.7   280.8  1124.3
   300.8  1124.8   305.5  1125.2     347  1126.7   361.1  1126.9   388.3  1128.2
   404.8  1129.5   421.4  1130.4   441.7  1132.2   462.9  1133.6   500.8  1135.4
#Mann= 3 , 0 , 0
       0     .08       0  230.37     .05       0  255.05     .08       0
#XS Ineff= 2 , 0
       0   217.8    1124   267.7       0    1124
Permanent Ineff=
       F       F
Bank Sta=230.37,255.05
Exp/Cntr=0.5,0.3

Type RM Length L Ch R = 1 ,1982.705,329.83,340.39,342.73
XS GIS Cut Line= 3
  1137622.689378   711380.443661  1138015.839277   711494.997226
  1138197.224604   711560.119711
#Sta/Elev= 30
       0 1157.34    14.1 1153.05   29.71 1149.75   38.08 1147.07   56.92 1142.44
  100.64 1128.05  123.15 1124.56  155.96 1122.41  175.58  1122.1   192.8 1121.02
  243.44 1120.85     276 1119.63  286.88 1120.21     328 1121.09  339.28 1121.89
  344.31 1121.02  344.88  1117.5  356.88  1117.5  357.45 1121.02  362.47 1121.89
  376.87 1122.97  383.28 1121.97  442.07 1123.03   450.6 1123.48  463.79 1125.08
  483.96 1126.65  501.39 1128.98  512.75 1129.98  533.12 1131.22  602.22  1133.3
#Mann= 3 , 0 , 0
       0     .08       0  339.28     .05       0  362.47     .08       0
Bank Sta=339.28,362.47
Exp/Cntr=0.3,0.1

Type RM Length L Ch R = 1 ,1642.317,299.32,300,311.36
XS GIS Cut Line= 3
  1137499.974962   711549.254329  1137828.708431   711789.383892
  1138223.528508   711941.520585
#Sta/Elev= 30
       0 1188.27   52.46 1172.88    90.7 1162.85  102.44 1159.11  123.03 1154.23
  143.25 1148.05  185.25 1136.35  215.51 1128.84  252.82 1123.25   304.7 1119.54
  336.85  1118.3  357.68  1118.7     366 1118.16  388.86 1118.52  395.83 1119.46
  400.82 1118.56  401.38    1117  413.38    1117  413.97 1118.62  418.93 1119.46
  450.81 1119.65   482.7 1118.78  537.72 1119.44  568.21 1121.62  623.96 1127.44
  666.58 1130.24  746.48 1133.73  779.73 1134.24  785.55 1133.86  830.21 1135.18
#Mann= 3 , 0 , 0
       0     .08       0  395.83     .05       0  418.93     .08       0
Bank Sta=395.83,418.93
Exp/Cntr=0.3,0.1

Type RM Length L Ch R = 1 ,1342.317,302.93,300,292.9
XS GIS Cut Line= 3
  1137370.299144   711794.766656  1137701.659333   712032.216052
   1138008.85146   712321.166393
#Sta/Elev= 30
       0 1181.43   42.76 1169.72   83.16 1156.25  103.69 1147.51  118.78 1142.42
  125.75 1139.33  188.95 1124.41  210.58 1121.56  233.49 1119.24  254.65 1117.98
  299.39 1117.77   318.2 1116.32  384.65 1115.15  395.88 1117.04  400.94 1116.22
  401.53  1113.5  413.53  1113.5  414.11  1116.2  419.18 1117.05  444.31 1118.09
  487.75 1117.15  508.14 1117.65  531.58 1117.52  555.94 1118.36  628.37 1124.21
  634.16  1124.1  684.65 1126.23  722.87 1128.35  810.34 1135.34  829.39 1137.27
#Mann= 3 , 0 , 0
       0     .09       0  395.88     .05       0  419.18      .1       0
Bank Sta=395.88,419.18
Exp/Cntr=0.3,0.1

Type RM Length L Ch R = 1 ,1042.317,151.3,150.86,150.41
XS GIS Cut Line= 3
  1137196.894064   712088.027006  1137551.993005   712291.975498
  1137907.091947   712495.924028
#Sta/Elev= 30
       0 1174.79   12.23 1172.69   39.82 1167.07   85.83 1154.21  100.15 1149.74
  109.24  1145.8  150.08 1126.28  155.76 1122.59  177.37 1115.69  219.71 1113.88
  256.78 1113.53  288.12  1113.9  334.47 1113.45  375.41 1113.49  397.66 1114.29
  402.94  1113.4   403.5    1110   415.5    1110  416.06  1113.4  421.33 1114.29
  447.36 1114.33  468.03 1113.77  530.92 1114.46  585.33 1116.57  637.71 1120.72
  659.42 1122.82  689.09 1124.44  731.04 1128.43  782.56 1134.72     819 1138.25
#Mann= 3 , 0 , 0
       0     .09       0  397.66     .05       0  421.33     .09       0
Bank Sta=397.66,421.33
Exp/Cntr=0.5,0.3

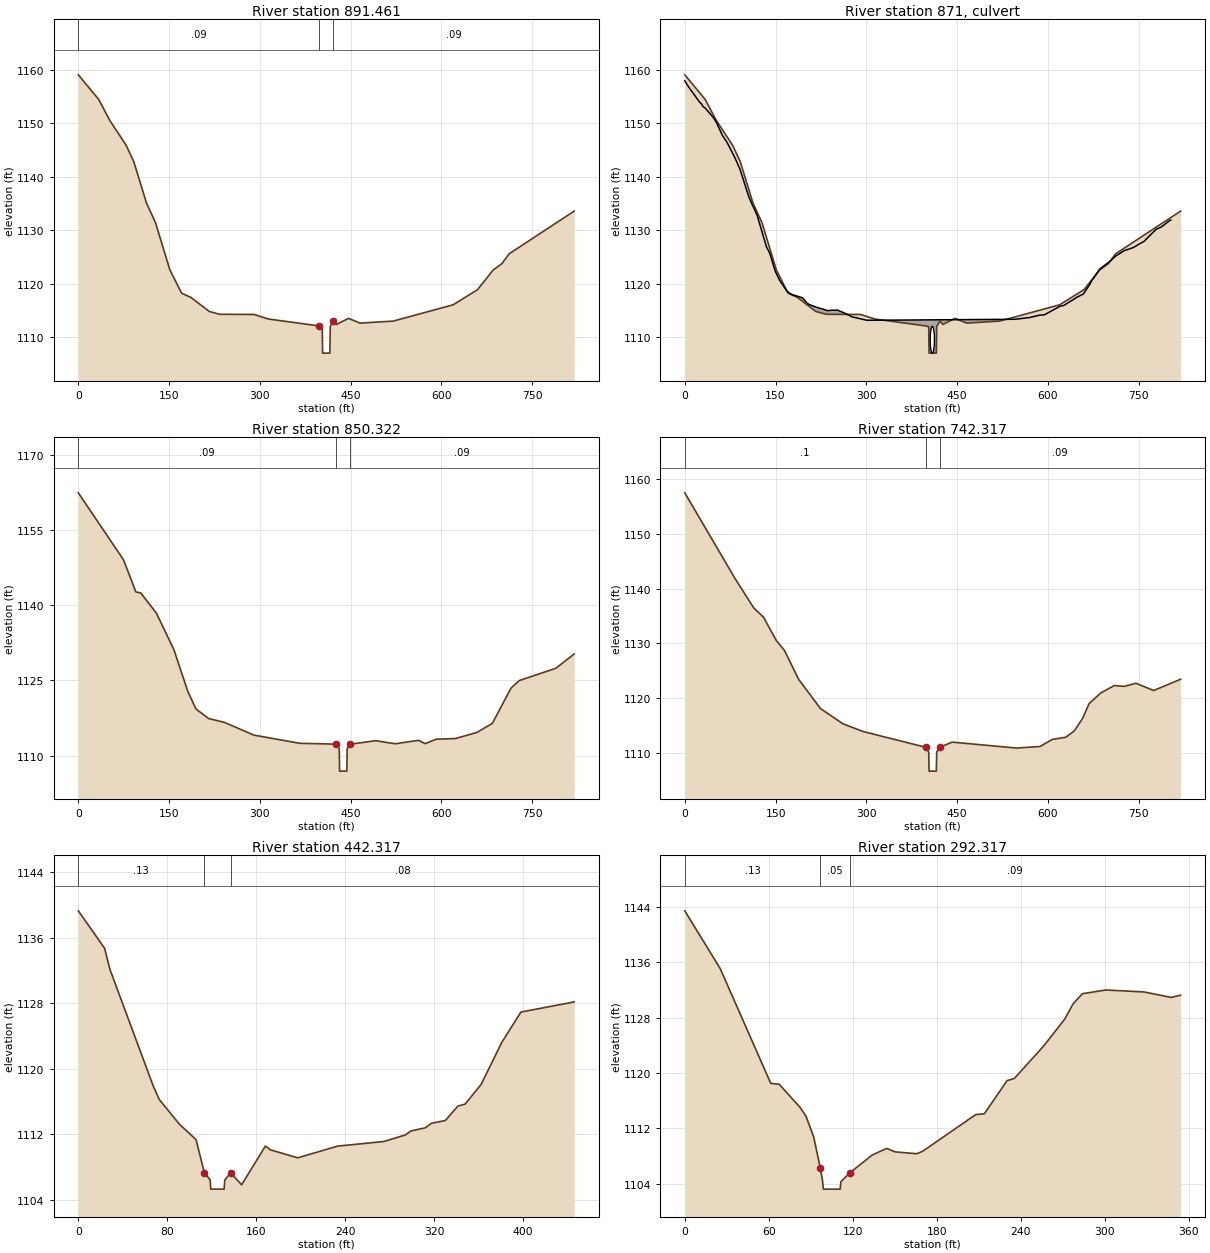
Type RM Length L Ch R = 1 ,891.461 ,41.09,41.14,41.19
BEGIN DESCRIPTION:
u/s section culvert 37111-0127
END DESCRIPTION:
XS GIS Cut Line= 4
  1137107.051417   712253.406513  1137440.653568   712402.615686
  1137514.191606   712443.393372   1137852.26832   712593.131052
#Sta/Elev= 30
       0 1159.03   33.67 1154.43   51.85 1150.54   78.94 1145.87   91.61  1142.8
   112.7 1135.03  127.53 1131.39  151.25 1122.57  170.61 1118.21  186.03 1117.42
  216.38 1114.79  233.82 1114.26  290.51 1114.23  313.96 1113.38  397.75 1112.09
  403.05 1111.92  403.65    1107  415.65    1107   416.3 1112.02  421.54 1112.96
  426.52 1112.36  446.43  1113.5  465.64 1112.61  520.39 1112.99  619.51 1116.04
  659.67 1118.87   685.4 1122.54  699.82 1123.72  711.86 1125.57  819.29 1133.55
#Mann= 3 , 0 , 0
       0     .09       0  397.75     .05       0  421.54     .09       0
Bank Sta=397.75,421.54
Exp/Cntr=0.5,0.3

Type RM Length L Ch R = 2 ,871     ,,,
BEGIN DESCRIPTION:
Culvert - 37111-0127
END DESCRIPTION:
Bridge Culvert--1,0,-1,-1, 0
Deck Dist Width WeirC Skew NumUp NumDn MinLoCord MaxHiCord MaxSubmerge Is_Ogee
12,16,2.6,0, 73, 73, , , 0.95, 0, 0.5,0.5,,
       0    6.81   23.34   28.25   29.94   33.79    47.1   52.29   61.85   70.17
   82.56   91.04  105.34  111.16  114.45  119.55  134.79  140.49  149.43  156.71
  168.15  173.59  178.69  194.51  202.43  205.55  210.97  221.71  227.88  235.92
   245.8  248.97  251.67   264.5  276.51  281.04  300.62   300.8  300.84  545.44
  545.54  545.64  548.34  567.15   568.5  585.99   594.3  605.61  620.37     626
  644.44  645.47  646.56   658.5   669.8  672.18  674.57  685.47  696.08  698.45
  703.04  712.14  716.68  726.07   738.7  742.18  752.47  758.92  768.71  778.81
  787.34  801.94  802.98
 1157.89 1156.69 1154.09  1153.5  1153.1 1152.81 1151.05 1150.12 1147.76 1146.33
 1143.58 1141.43 1136.37  1134.8 1134.06 1132.76 1126.91 1125.64 1122.32 1120.61
 1118.68 1118.16  1117.9 1117.35 1116.32 1116.08 1115.86 1115.43 1115.24 1114.94
 1115.06    1115 1115.07 1114.47 1113.77 1113.66 1113.15 1113.14 1113.14 1113.33
 1113.33 1113.33 1113.36 1113.62 1113.62 1114.09 1114.17 1114.87 1115.79  1115.9
 1117.19 1117.27 1117.37 1118.05 1119.96 1120.55 1120.88  1122.7 1123.62 1123.82
 1124.21 1125.17 1125.48 1126.16 1126.64 1126.81  1127.5  1127.9 1129.03 1130.14
 1130.58 1131.85 1131.85
                                                                                
                                                                                
                                                                                
                                                                                
                                                                                
                                                                                
                                                                                
                        
       0    6.81   23.34   28.25   29.94   33.79    47.1   52.29   61.85   70.17
   82.56   91.04  105.34  111.16  114.45  119.55  134.79  140.49  149.43  156.71
  168.15  173.59  178.69  194.51  202.43  205.55  210.97  221.71  227.88  235.92
   245.8  248.97  251.67   264.5  276.51  281.04  300.62   300.8  300.84  545.44
  545.54  545.64  548.34  567.15   568.5  585.99   594.3  605.61  620.37     626
  644.44  645.47  646.56   658.5   669.8  672.18  674.57  685.47  696.08  698.45
  703.04  712.14  716.68  726.07   738.7  742.18  752.47  758.92  768.71  778.81
  787.34  801.94  802.98
 1157.89 1156.69 1154.09  1153.5  1153.1 1152.81 1151.05 1150.12 1147.76 1146.33
 1143.58 1141.43 1136.37  1134.8 1134.06 1132.76 1126.91 1125.64 1122.32 1120.61
 1118.68 1118.16  1117.9 1117.35 1116.32 1116.08 1115.86 1115.43 1115.24 1114.94
 1115.06    1115 1115.07 1114.47 1113.77 1113.66 1113.15 1113.14 1113.14 1113.33
 1113.33 1113.33 1113.36 1113.62 1113.62 1114.09 1114.17 1114.87 1115.79  1115.9
 1117.19 1117.27 1117.37 1118.05 1119.96 1120.55 1120.88  1122.7 1123.62 1123.82
 1124.21 1125.17 1125.48 1126.16 1126.64 1126.81  1127.5  1127.9 1129.03 1130.14
 1130.58 1131.85 1131.85
                                                                                
                                                                                
                                                                                
                                                                                
                                                                                
                                                                                
                                                                                
                        
BR Coef=-1 , 0 , 0 ,, 0 ,,,0.8,-1,,0,
WSPro=,,,, 1 ,,,, 0 ,,,, 0 ,,,,-1 ,-1 ,-1 , 0 , 0 , 0 , 0 , 0
Culvert=4,5,7,21,0.024,0.5,1,29,1,1107,409,1106.9,438,Culvert #1  , 0 ,10
Culvert Bottom n=0.024
BC Design=,, 0 ,, 0 ,,,,,,

Type RM Length L Ch R = 1 ,850.322 ,108.91,108,107.11
BEGIN DESCRIPTION:
d/s section culvert - 37111-0127
END DESCRIPTION:
XS GIS Cut Line= 4
  1137062.845625   712282.877093  1137421.301436   712438.693577
  1137494.563039   712479.471224  1137808.062528   712622.601632
#Sta/Elev= 30
       0 1162.41   74.66 1149.05    95.1 1142.64  103.18 1142.44  129.02 1138.41
  157.85 1131.15  180.64  1122.9  194.36 1119.29  215.45 1117.38  241.13 1116.64
  290.16 1114.08  365.84 1112.45  425.81 1112.28  431.17 1111.38  431.71  1106.9
  443.71  1106.9  444.25 1111.38   449.6 1112.27  491.25 1112.97  523.67 1112.36
  562.13 1113.04  573.19 1112.38   591.5 1113.27  623.13  1113.4   658.8 1114.62
  684.12 1116.42  714.97 1123.45  728.65 1124.97  789.24 1127.42  819.33 1130.27
#Mann= 3 , 0 , 0
       0     .09       0  425.81     .05       0   449.6     .09       0
Bank Sta=425.81,449.6
Exp/Cntr=0.5,0.3

Type RM Length L Ch R = 1 ,742.317 ,297.27,300,303.35
XS GIS Cut Line= 3
  1137052.196929   712370.435857  1137415.737257   712558.926335
  1137779.277623   712747.416852
#Sta/Elev= 30
       0 1157.45   82.78 1141.86  113.88 1136.47  130.13 1134.76  150.87 1130.57
  164.72 1128.69  188.09 1123.43  224.21  1118.1  261.35 1115.32  294.97 1113.91
  397.63 1111.06  402.95 1110.16   403.5  1106.7   415.5  1106.7  416.06 1110.17
  421.36 1111.06  441.59 1111.99  547.74 1110.91  586.63 1111.19  606.96 1112.48
  629.33 1112.88  643.44 1114.05   657.1 1116.31  667.78    1119  687.06 1120.95
  709.44 1122.31  725.79 1122.15  745.22 1122.72  774.56  1121.4     819 1123.46
#Mann= 3 , 0 , 0
       0      .1       0  397.63     .05       0  421.36     .09       0
Bank Sta=397.63,421.36
Exp/Cntr=0.3,0.1

Type RM Length L Ch R = 1 ,442.317 ,146.78,150,148.99
XS GIS Cut Line= 3
  1137174.516375   712758.779841  1137280.096256   712826.208176
  1137546.674052   713004.727512
#Sta/Elev= 30
       0 1139.29   23.63 1134.72   28.44 1132.14   67.16 1117.99   72.83 1116.26
      91 1113.24  105.93 1111.36  113.38 1107.32  118.62 1106.44  119.18 1105.32
  131.18 1105.32  131.73 1106.42  136.97 1107.31  146.92 1105.85  168.35 1110.58
  172.96 1110.11  197.39 1109.14  233.32 1110.57  274.71 1111.13  293.98 1111.92
  299.45 1112.43  312.09  1112.8  317.55 1113.35  330.25  1113.7  341.52 1115.46
  347.94 1115.69   362.3 1118.08  381.12 1123.26  398.18 1126.93  446.11 1128.17
#Mann= 3 , 0 , 0
       0     .13       0  113.38     .05       0  136.97     .08       0
Bank Sta=113.38,136.97
Exp/Cntr=0.3,0.1

Type RM Length L Ch R = 1 ,292.317 ,136.99,150.52,167.03
XS GIS Cut Line= 3
  1137112.220434   712884.180805  1137195.154042   712948.488524
   1137407.51944   713079.159055
#Sta/Elev= 30
       0 1143.42   25.38 1135.05   61.41 1118.51   67.41 1118.39   82.23 1115.08
   86.61 1113.76   92.12 1110.77   96.75 1106.35   98.37 1104.54   99.02 1103.24
  111.02 1103.24  111.56 1104.31  117.92 1105.59  133.89 1108.16  144.25 1109.12
  150.33 1108.62  165.71 1108.35  170.07 1108.72  207.89    1114  214.05 1114.12
  230.25  1118.9  235.48 1119.22  256.21 1123.85  271.33 1127.74  277.51    1130
  284.04 1131.45  300.77 1131.99  328.06 1131.71  347.55 1130.92  354.29 1131.24
#Mann= 3 , 0 , 0
       0     .13       0   96.75     .05       0  117.92     .09       0
Bank Sta=96.75,117.92
Exp/Cntr=0.3,0.1

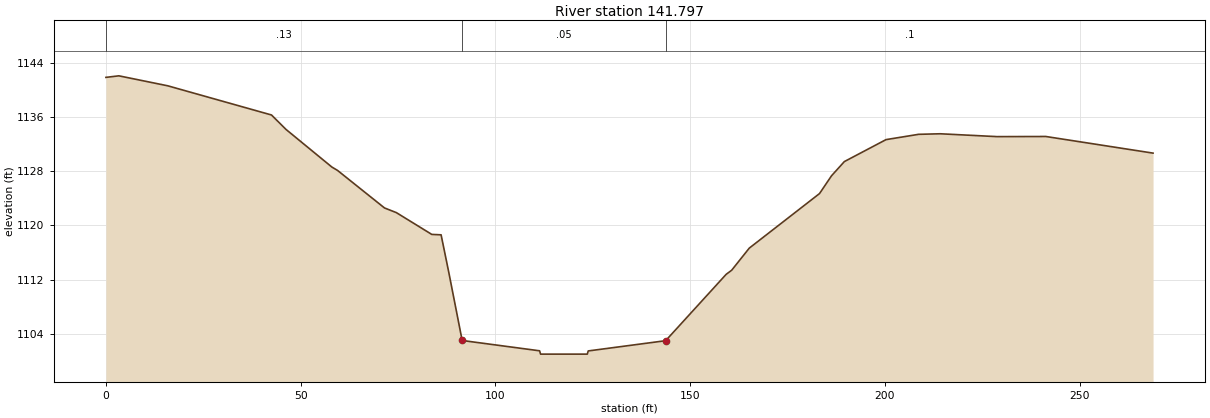
Type RM Length L Ch R = 1 ,141.797 ,170.68,141.8,173.69
XS GIS Cut Line= 3
  1137085.522141   712940.004443  1137080.667923   713014.435986
   1137167.23503   713188.379241
#Sta/Elev= 30
       0 1141.81    3.32 1142.04   15.88 1140.57   42.52 1136.27   46.23 1134.15
   58.02  1128.6   59.48  1128.1   71.54 1122.57   74.59 1121.88   83.68 1118.67
   86.07 1118.61   88.08 1112.98   91.48 1103.04  111.36 1101.52  111.61 1101.03
  123.61 1101.03  123.85  1101.5  143.73 1103.01  159.27 1112.79  160.68 1113.39
   165.2 1116.65  183.24 1124.69  186.32 1127.31  189.61  1129.4  200.32 1132.64
  208.69 1133.42  214.24  1133.5  228.82 1133.08  241.34  1133.1  268.88 1130.65
#Mann= 3 , 0 , 0
       0     .13       0   91.48     .05       0  143.73      .1       0
Bank Sta=91.48,143.73
Exp/Cntr=0.3,0.1

Chan Stop Cuts=-1
Use User Specified Reach Order=0
User Specified Reach Order=WaltonCrowley   ,Main